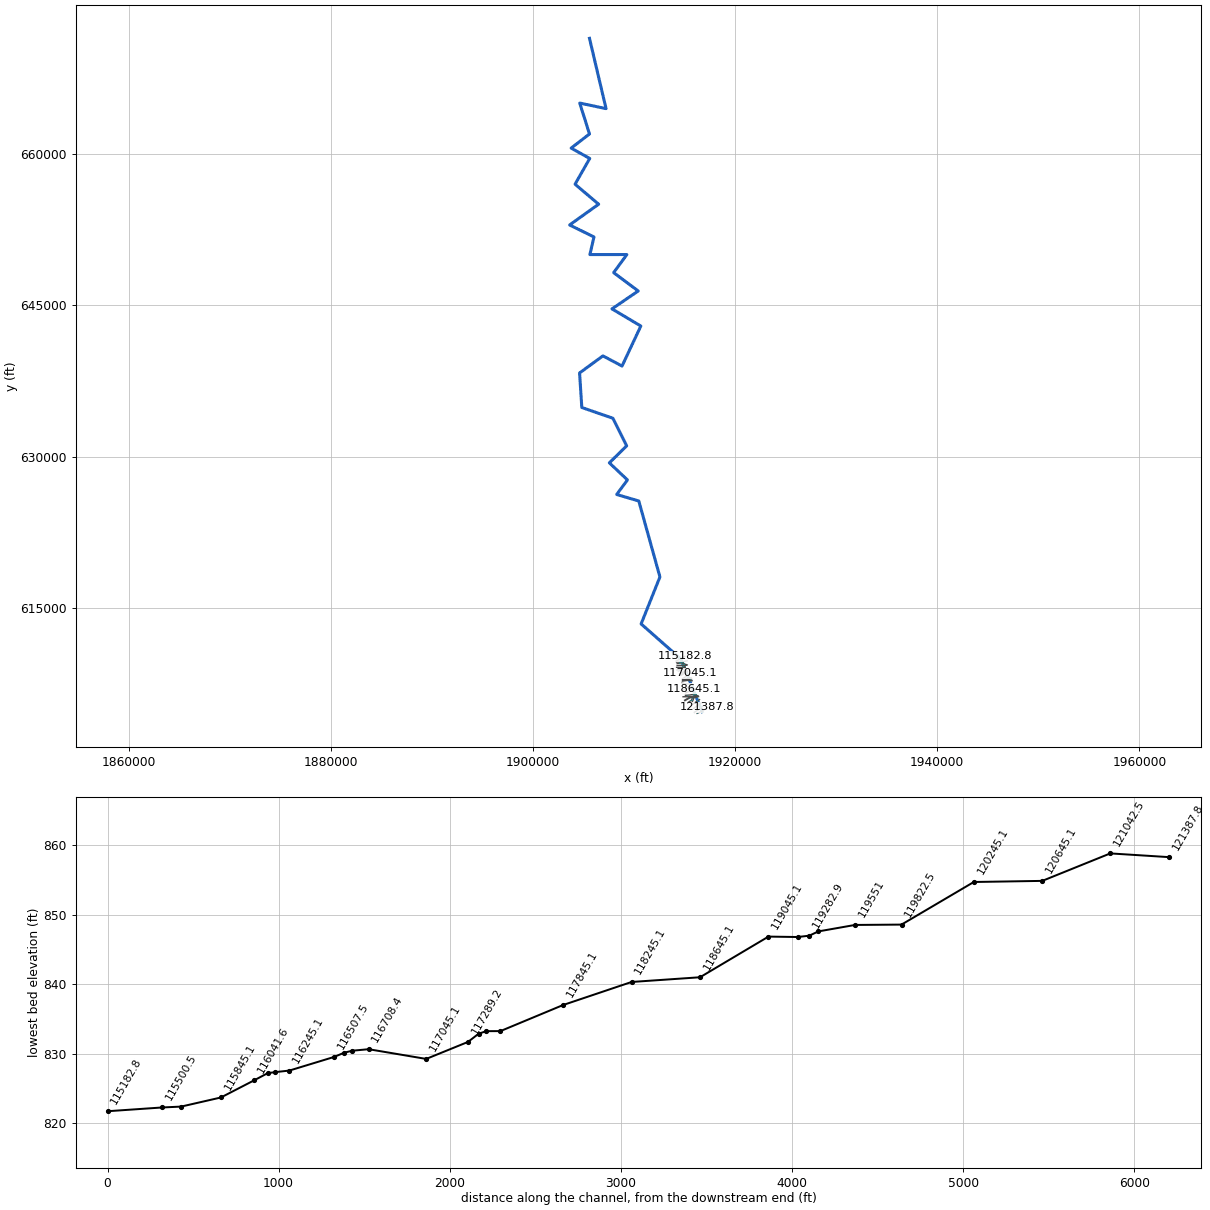
--- HenryFork.prj (project) ---

Proj Title=HenryFork
Current Plan=p01
Default Exp/Contr=0,0
English Units
Geom File=g01
Flow File=f01
Plan File=p01
BEGIN DESCRIPTION:
AMEC Environment & Infrastructure, 2013
Projection: NAD 1983 State Plane West Virginia South FIPS 4702 (US Feet)
Vertical Datum: NAVD 1988
END DESCRIPTION:
DSS Export Rating Curves= 0
DSS Export Rating Curve Sorted= 0
DSS Export Volume Flow Curves= 0
DXF OffsetX= 0
DXF OffsetY= 0
DXF ScaleX= 0
DXF ScaleY= 0

--- HenryFork.p01 (plan) ---

Plan Title=Floodplain
Program Version=4.00
Geom File=g01
Flow File=f01
K Sum by GR=0
Std Step Tol=0.01
Critical Tol=0.01
Num of Std Step Trials=20
Max Error Tol=0.3
Flow Tol Ratio=0.001
Split Flow NTrial=30
Split Flow Tol=0.02
Split Flow Ratio=0.02
Log Output Level=0
Friction Slope Method=1
Unsteady Friction Slope Method=2
Unsteady Bridges Friction Slope Method=1
Global Log Level=0
CheckData=False
Run HTab=0
Run UNet=0
Run PostProcess=0
UNET Theta=0
UNET Theta Warmup=0
UNET ZTol=0
UNET ZSATol=0
UNET MxIter=0
UNET MaxInSteps=0
UNET DtIC=0
UNET DtMin=0
UNET MaxCRTS=0
UNET WFStab=0
UNET SFStab=0
UNET WFX=0
UNET SFX=0
UNET DSS MLevel=0
UNET DZMax Abort=0
UNET Convert EG Bridges=0
UNET Use Existing IB Tables=0
UNET Froude Limit=0
UNET Froude Power=0
Write IC File=0
Echo Input=False
Echo Output=False
Write Detailed=0

--- HenryFork.f01 (steady flow) ---

Flow Title=NFF Regression Equation
Program Version=4.10
Number of Profiles= 1
Profile Names=P100yr
River Rch & RM=HenryFork,Main            ,121387.8
936.0025
River Rch & RM=HenryFork,Main            ,120645.1
959.2291
River Rch & RM=HenryFork,Main            ,119045.1
 1044.03
River Rch & RM=HenryFork,Main            ,115613.2
 1133.62
River Rch & RM=HenryFork,Main            ,115182.8
1337.951
River Rch & RM=HenryFork,Main            ,111789.1
1444.058
River Rch & RM=HenryFork,Main            ,111527.2
 2319.07
River Rch & RM=HenryFork,Main            ,104737.5
2439.967
River Rch & RM=HenryFork,Main            ,104254.4
 2502.06
River Rch & RM=HenryFork,Main            ,102820.7
2525.605
River Rch & RM=HenryFork,Main            ,102264.3
 2734.71
River Rch & RM=HenryFork,Main            ,98536.9
2783.191
River Rch & RM=HenryFork,Main            ,98068.6
 3718.06
River Rch & RM=HenryFork,Main            ,95581.6
3736.025
River Rch & RM=HenryFork,Main            ,95260.5
3945.542
River Rch & RM=HenryFork,Main            ,91667.3
4016.595
River Rch & RM=HenryFork,Main            ,91380.3
4230.441
River Rch & RM=HenryFork,Main            ,89237.5
4241.698
River Rch & RM=HenryFork,Main            ,88657.1
4683.571
River Rch & RM=HenryFork,Main            ,85477.3
4707.668
River Rch & RM=HenryFork,Main            ,85115.7
 4771.64
River Rch & RM=HenryFork,Main            ,70844.5
5058.436
River Rch & RM=HenryFork,Main            ,70508.6
5858.977
River Rch & RM=HenryFork,Main            ,64169.2
5952.439
River Rch & RM=HenryFork,Main            ,63676.4
6616.445
River Rch & RM=HenryFork,Main            ,46530
7080.474
River Rch & RM=HenryFork,Main            ,46079.4
9594.899
River Rch & RM=HenryFork,Main            ,36119.6
9666.781
River Rch & RM=HenryFork,Main            ,35915.5
9970.385
River Rch & RM=HenryFork,Main            ,23417.8
10313.55
River Rch & RM=HenryFork,Main            ,22721.3
10998.09
River Rch & RM=HenryFork,Main            ,14242
11240.72
River Rch & RM=HenryFork,Main            ,13634.5
11397.31
River Rch & RM=HenryFork,Main            ,1334.3
11544.19
River Rch & RM=HenryFork,Main            ,1153.3
11629.82
River Rch & RM=HenryFork,Main            ,181.1
11643.63
Boundary for River Rch & Prof#=HenryFork,Main            , 1
Up Type= 0
Dn Type= 3
Dn Slope=0.00047
DSS Import GetInterval= 0
DSS Import GetPeak= 0
DSS Import FillOption= 0

--- HenryFork.g01 (geometry) ---

Geom Title=USGS 3m DEM
Program Version=4.10

River Reach=HenryFork       ,Main
Reach XY= 30
     1916742.306      604787.765     1914620.927       610009.15
     1910701.387      613469.229     1912561.969      618118.587
     1910471.047      625631.459      1908280.56      626278.339
      1909348.62      627715.525     1907557.554      629408.805
     1909270.375      631089.156     1907909.122      633820.158
      1904831.26      634884.319     1904611.151      638301.794
     1906921.138      639991.677     1908812.087      638987.024
     1910672.477      642946.884     1907815.458      644642.312
     1910414.035      646413.885     1907981.056       648228.82
     1909291.546      650019.807     1905631.315      650017.524
     1906035.058      651758.644     1903624.352      652945.356
     1906497.369        654999.9     1904163.521       656977.57
     1905615.852      659529.454     1903776.348      660551.385
      1905591.85        661951.3     1904625.665      665010.164
     1907231.935      664457.739     1905591.528      671414.576

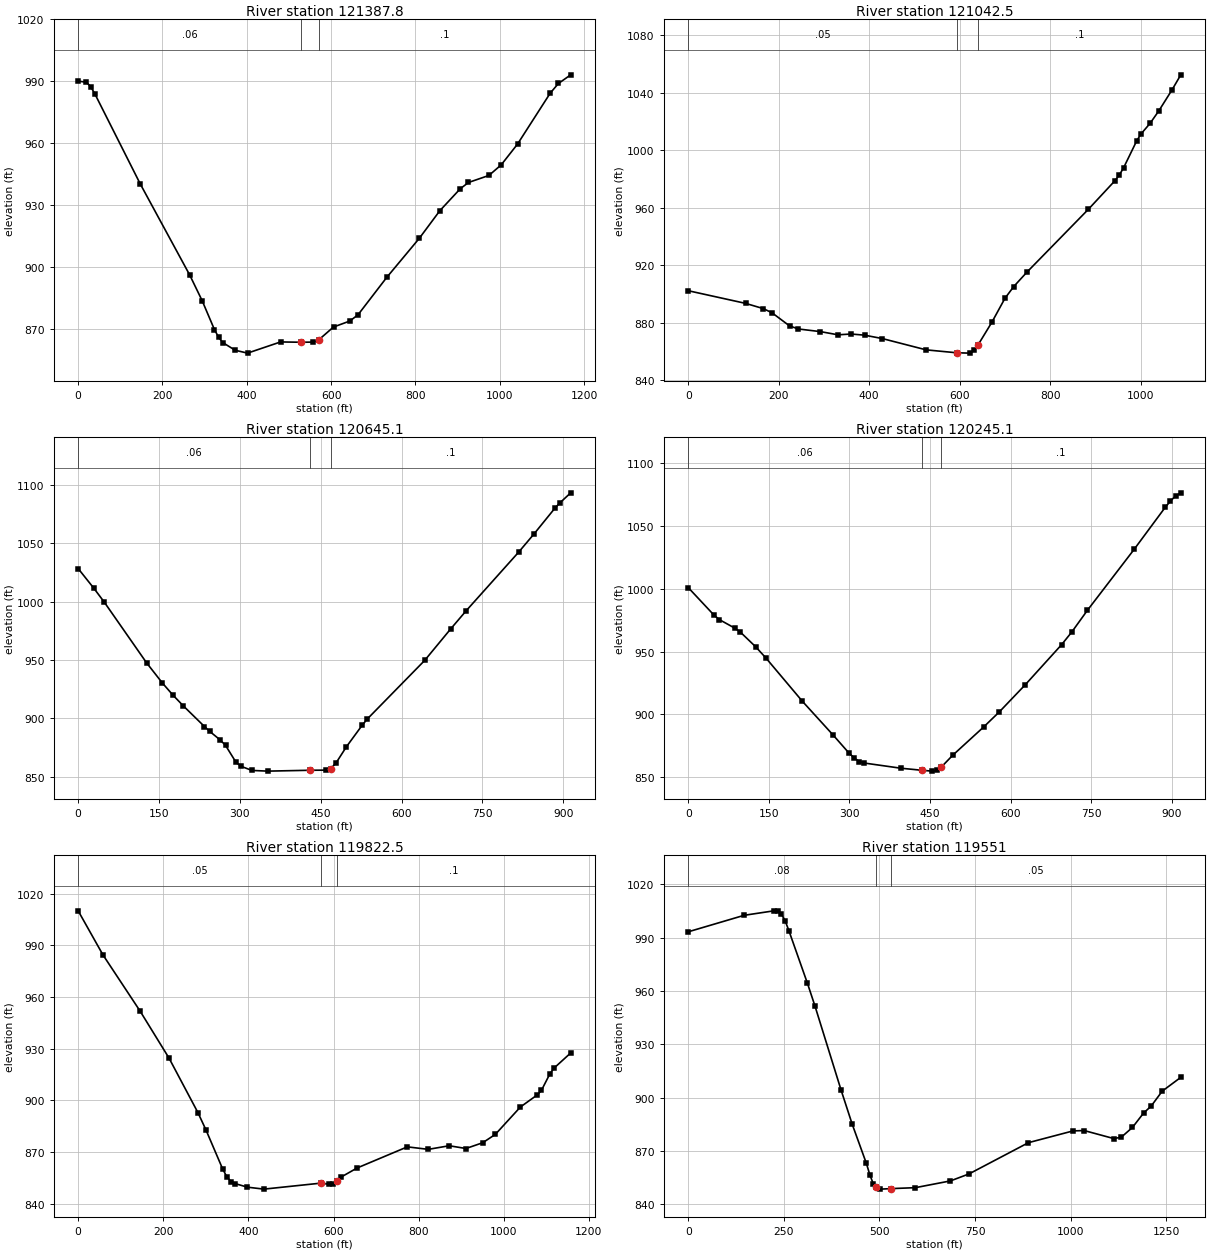
Type RM Length L Ch R = 1 ,121387.8,339,345.4,351.6
XS GIS Cut Line= 4
     1916242.983      604616.928     1916714.771      604833.942
      1916784.65      604865.192     1917249.927      605198.525
#Sta/Elev= 30
       0  990.04    19.6  989.53    29.4  987.43    39.2  984.04     147  940.36
   264.6  896.14     294  883.75   323.3  869.68   333.1  866.02   342.9  863.44
   372.3  859.72   401.7  858.32   480.1  863.74   528.9  863.59   557.6  863.66
   570.7  864.77   605.6  870.97   644.4  873.87   663.8   876.9   731.7  894.95
   809.3  913.97   857.8  927.29   906.3  937.93   925.7  940.96   974.2  944.37
  1003.3  949.48  1042.1  959.56  1119.7  984.25  1139.1  988.91  1168.2   993.1
#Mann= 3 , 0 , 0
       0     .06       0   528.9    .045       0   570.7      .1       0
Bank Sta=528.9,570.7
XS Rating Curve= 0 ,0
Exp/Cntr=0.3,0.1

Type RM Length L Ch R = 1 ,121042.5,399.1,397.4,395
XS GIS Cut Line= 4
     1915964.337      604723.265     1916438.204      605012.398
     1916535.084      605092.188     1916831.522      605372.624
#Sta/Elev= 30
       0  902.29   126.6   893.5   165.6  889.87     185  886.97     224  877.79
   243.5  875.66   292.2  873.83   331.1  871.61   360.3  872.16   389.6  871.36
   428.5  869.03   525.9  861.13   593.7  859.09   622.7  858.86   632.4  860.78
   640.1  864.33     671  880.29     700     897   719.5  905.21   748.6  915.22
   884.6  959.03     943  978.81   952.7  982.78   962.4  987.93   991.5 1006.77
  1001.2 1011.58  1020.7 1018.74  1040.1 1027.46  1069.3 1042.08  1088.7 1052.56
#Mann= 3 , 0 , 0
       0     .05       0   593.7    .045       0   640.1      .1       0
Bank Sta=593.7,640.1
XS Rating Curve= 0 ,0
Exp/Cntr=0.3,0.1

Type RM Length L Ch R = 1 ,120645.1,399,400,398.6
XS GIS Cut Line= 3
     1915910.232      605123.868     1916286.801      605386.167
     1916656.456      605651.058
#Sta/Elev= 30
       0  1028.3    29.3 1011.32    48.8  999.32   126.9  947.62   156.2  930.35
   175.8  919.98   195.3  910.65   234.3  893.08   244.1   888.9   263.6  881.54
   273.4  876.91   292.9  862.39   302.7  858.94   322.2   855.5   351.5   854.9
   429.6  855.63   458.9  855.75   468.6  857.07   478.3  861.84   497.6  875.74
   526.6  894.01   536.3   899.5   642.8  949.66   691.1  976.66   720.2   992.4
   816.9 1042.23     846 1058.13   884.7 1080.16   894.3 1084.82   913.7 1093.13
#Mann= 3 , 0 , 0
       0     .06       0   429.6    .045       0   468.6      .1       0
Bank Sta=429.6,468.6
XS Rating Curve= 0 ,0
Exp/Cntr=0.3,0.1

Type RM Length L Ch R = 1 ,120245.1,405.2,422.6,441.4
XS GIS Cut Line= 3
     1915724.238      605456.484      1916095.25      605733.686
      1916478.53      605976.246
#Sta/Elev= 30
       0 1000.91    48.2  978.87    57.9  975.43    86.8  968.59    96.5  965.67
   125.4  953.81   144.7  944.78   212.3  910.43   270.2   883.2   299.1  869.16
   308.8  865.23   318.4  862.34     328  861.16   395.6  857.06   434.2  855.45
   453.5  854.74   463.1  855.26   470.6  857.81   492.1  867.33     550  889.98
   578.9  901.89   627.2  923.52   694.8  955.44     714  965.65     743   982.9
   829.9  1031.4   887.8 1064.89   897.4 1069.84   907.1 1073.96   916.7 1076.41
#Mann= 3 , 0 , 0
       0     .06       0   434.2    .045       0   470.6      .1       0
Bank Sta=434.2,470.6
XS Rating Curve= 0 ,0
Exp/Cntr=0.3,0.1

Type RM Length L Ch R = 1 ,119822.5,277.6,271.5,265.4
XS GIS Cut Line= 4
     1915658.906      605539.348     1915873.191      606006.685
     1915898.799      606145.574     1916383.174      606277.084
#Sta/Elev= 30
       0 1009.99    58.2  984.46   145.5  951.85   213.4  924.62   281.3  893.02
   300.7   882.7   339.5  860.29   349.2  855.81   358.9     853   368.6  851.82
   397.7  849.73   436.5   848.6   570.6  852.08   589.4  851.45   598.9   851.8
   608.3  853.34   617.7  855.58   655.4  860.86   773.4  873.11   822.7  871.67
   871.9  873.75   911.2  872.16   950.6  875.51   980.1  880.32  1039.2  896.24
  1078.5   903.2  1088.4  905.81  1108.1  915.32  1117.9  918.73  1157.3  927.57
#Mann= 3 , 0 , 0
       0     .05       0   570.6    .045       0   608.3      .1       0
Bank Sta=570.6,608.3
XS Rating Curve= 0 ,0
Exp/Cntr=0.3,0.1

Type RM Length L Ch R = 1 ,119551  ,236.5,213.9,191.6
XS GIS Cut Line= 5
     1915321.108      605671.616     1915678.747      605925.088
     1915729.094      606032.727     1915770.761      606143.838
     1916357.566      606317.449
#Sta/Elev= 30
       0  993.21   146.1 1002.48     224    1005   233.8 1004.83   243.5 1003.17
   253.3  999.37     263  993.92   311.7   964.2   331.2  951.56   399.4  904.36
   428.6  885.08   465.8  862.96   474.9  856.53   484.1  851.35   490.6  849.61
   502.3  848.55   529.8  848.83   593.7  849.37   685.6  853.18   734.1   857.1
   889.6  874.68  1006.1  881.28  1035.2  881.48    1113  876.95  1132.4  877.77
  1161.5  883.25  1190.7  891.37  1210.1  895.16  1239.2  903.62  1287.8  911.39
#Mann= 3 , 0 , 0
       0     .08       0   490.6    .045       0   529.8     .05       0
Bank Sta=490.6,529.8
XS Rating Curve= 0 ,0
Exp/Cntr=0.3,0.1

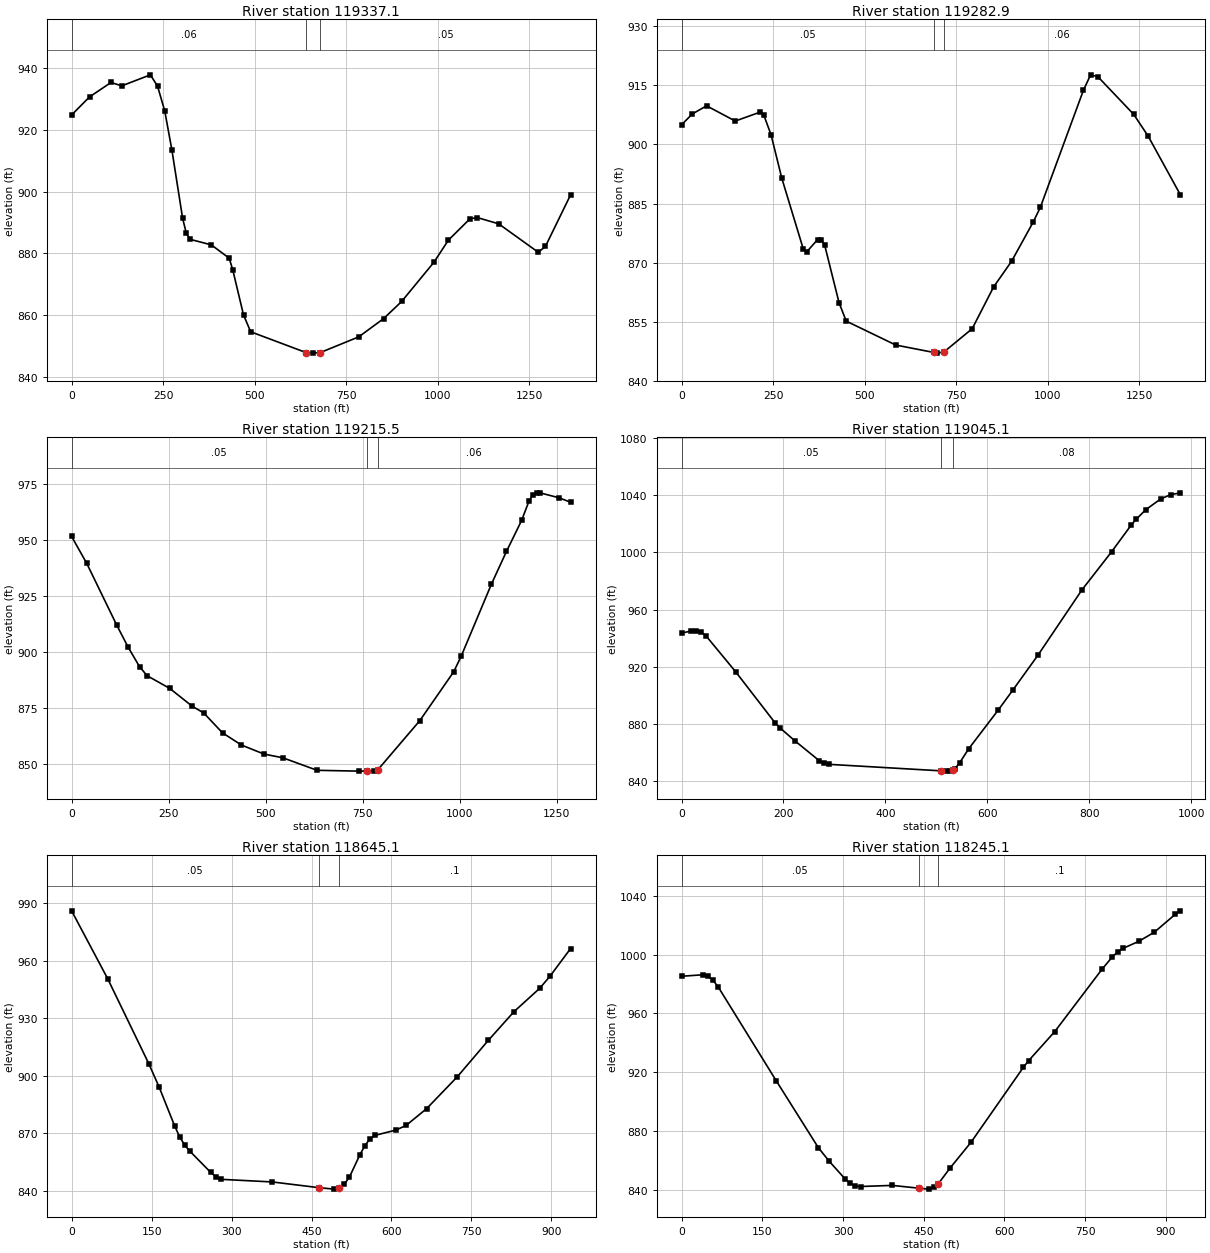
Type RM Length L Ch R = 1 ,119337.1,54.2,54.1,53.8
XS GIS Cut Line= 5
     1915036.386      605871.268     1915508.608      606149.046
     1915694.372      606175.088     1915857.566      606206.338
     1916303.747      606324.393
#Sta/Elev= 30
       0  924.83    48.9  930.68   107.6  935.36     137  934.26   215.2  937.84
   234.8  934.16   254.4  926.13   273.9  913.52   303.3   891.3   313.1   886.6
   322.8  884.54   381.6  882.72   430.5   878.4   440.2  874.63   469.6  860.02
   489.2  854.54   641.6  847.75   658.2  847.62   679.2   847.8   784.3  852.88
   852.7  858.84   901.6  864.36     990  877.11  1029.3  884.24  1088.2  891.16
  1107.8  891.58  1166.7  889.54  1274.8  880.32  1294.4  882.21  1363.1  898.92
#Mann= 3 , 0 , 0
       0     .06       0   641.6    .045       0   679.2     .05       0
Bank Sta=641.6,679.2
XS Rating Curve= 0 ,0
Exp/Cntr=0.3,0.1

Type RM Length L Ch R = 1 ,119282.9,68.5,67.4,66.3
XS GIS Cut Line= 5
       1915003.4      605919.879     1915475.622      606197.657
     1915661.386      606223.699      1915824.58      606254.949
     1916270.761      606373.004
#Sta/Elev= 30
       0  904.98    29.4  907.74    68.5  909.81   146.8  905.94   215.2  908.22
     225  907.41   244.6  902.46   273.9  891.44   332.6  873.46   342.4  872.75
   371.8  875.85   381.6  875.84   391.3  874.35   430.5  859.76     450  855.13
   585.4  849.05   688.6  847.18   697.9     847   716.7  847.28   794.1   853.2
   852.7  863.82   901.6  870.31   960.5  880.24   980.2  884.01    1098  913.77
  1117.6  917.68  1137.3  917.22  1235.5  907.62  1274.8  902.11  1363.1  887.17
#Mann= 3 , 0 , 0
       0     .05       0   688.6    .045       0   716.7     .06       0
Bank Sta=688.6,716.7
XS Rating Curve= 0 ,0
Exp/Cntr=0.3,0.1

Type RM Length L Ch R = 1 ,119215.5,166.2,170.5,174.6
XS GIS Cut Line= 4
     1914848.886      606261.893     1915383.608      606263.629
     1915744.719      606296.616     1916104.094      606444.185
#Sta/Elev= 30
       0  951.51    38.9  939.52   116.7   911.8   145.8  902.06     175  893.43
   194.4   889.4   252.8  883.72   311.1  875.72   340.3  872.79   388.9  863.88
   437.5  858.46   495.8  854.42   544.5  852.75   632.7  847.17   740.5  846.81
   760.1  846.84   779.7  846.85   789.5  847.48   897.3  869.33   984.8  891.18
  1004.2  898.18  1081.9  930.26  1120.7  944.87  1159.6  958.65    1179  967.42
  1188.7  970.14  1198.4  970.98  1208.1  970.92  1256.7  968.74  1285.8  966.78
#Mann= 3 , 0 , 0
       0     .05       0   760.1    .045       0   789.5     .06       0
Bank Sta=760.1,789.5
XS Rating Curve= 0 ,0
Exp/Cntr=0.3,0.1

Type RM Length L Ch R = 1 ,119045.1,396.1,400,404.6
XS GIS Cut Line= 4
     1915088.469      606402.518      1915550.98      606436.439
     1915647.497      606463.282     1916042.608      606591.192
#Sta/Elev= 30
       0  943.47    19.3   945.1      29   945.3    38.6   944.3    48.3  941.52
   106.3  916.43   183.6  880.69   193.2  877.15   222.2  868.18   270.5  854.12
   280.2  852.38   289.8  851.62   509.3  847.07   518.4  846.87   527.5  846.97
     532   847.8   536.6  848.65   545.7  852.62   563.9  862.66   621.9  889.81
   650.9  903.96   699.2  927.91   786.1  973.94     844 1000.48   882.6 1019.23
   892.3 1023.31   911.6  1030.1   940.6 1037.54   959.9 1040.48   979.2 1041.78
#Mann= 3 , 0 , 0
       0     .05       0   509.3    .045       0     532     .08       0
Bank Sta=509.3,532
XS Rating Curve= 0 ,0
Exp/Cntr=0.3,0.1

Type RM Length L Ch R = 1 ,118645.1,398.2,400,402.5
XS GIS Cut Line= 3
     1915089.337      606634.723     1915526.443      606839.332
     1915928.331      607049.027
#Sta/Elev= 30
       0  985.99    67.6  950.66   144.8  906.34   164.1  894.21     193  874.12
   202.7  868.22   212.4  863.79     222  860.72   260.6  849.82   270.3  847.51
   279.9  846.12   376.4  844.75   463.3  841.79   492.3  841.01   501.9  841.65
   511.6  843.62   521.2  847.33   540.5  858.79   550.1  863.65   559.8  867.27
   569.4  869.04     608  871.76   627.3  874.16   665.9  882.94   723.7  899.61
   781.6   918.5   829.8  933.47   878.1  945.64   897.4  951.96   935.9  966.32
#Mann= 3 , 0 , 0
       0     .05       0   463.3    .045       0   501.9      .1       0
Bank Sta=463.3,501.9
XS Rating Curve= 0 ,0
Exp/Cntr=0.3,0.1

Type RM Length L Ch R = 1 ,118245.1,415.1,400,386.5
XS GIS Cut Line= 3
     1914907.045      606945.053     1915315.253      607177.365
     1915694.296      607433.145
#Sta/Elev= 30
       0  985.35    39.1  986.34    48.9  985.32    58.7  982.57    68.5  977.87
   176.1  914.08   254.4  868.46     274  859.51   303.3  847.52   313.1  844.19
   322.9  842.45   332.7  842.12   391.4  842.87   440.3  840.99   459.9  840.33
   469.7  841.47   477.2  844.04   498.9  854.68   537.8  872.21   635.1  923.29
   644.8   927.8   693.4  947.65     781  990.01   800.5  998.61   810.2 1001.92
   819.9 1004.29   849.1 1009.07   878.3 1015.32   917.2  1027.5     927 1029.93
#Mann= 3 , 0 , 0
       0     .05       0   440.3    .045       0   477.2      .1       0
Bank Sta=440.3,477.2
XS Rating Curve= 0 ,0
Exp/Cntr=0.3,0.1

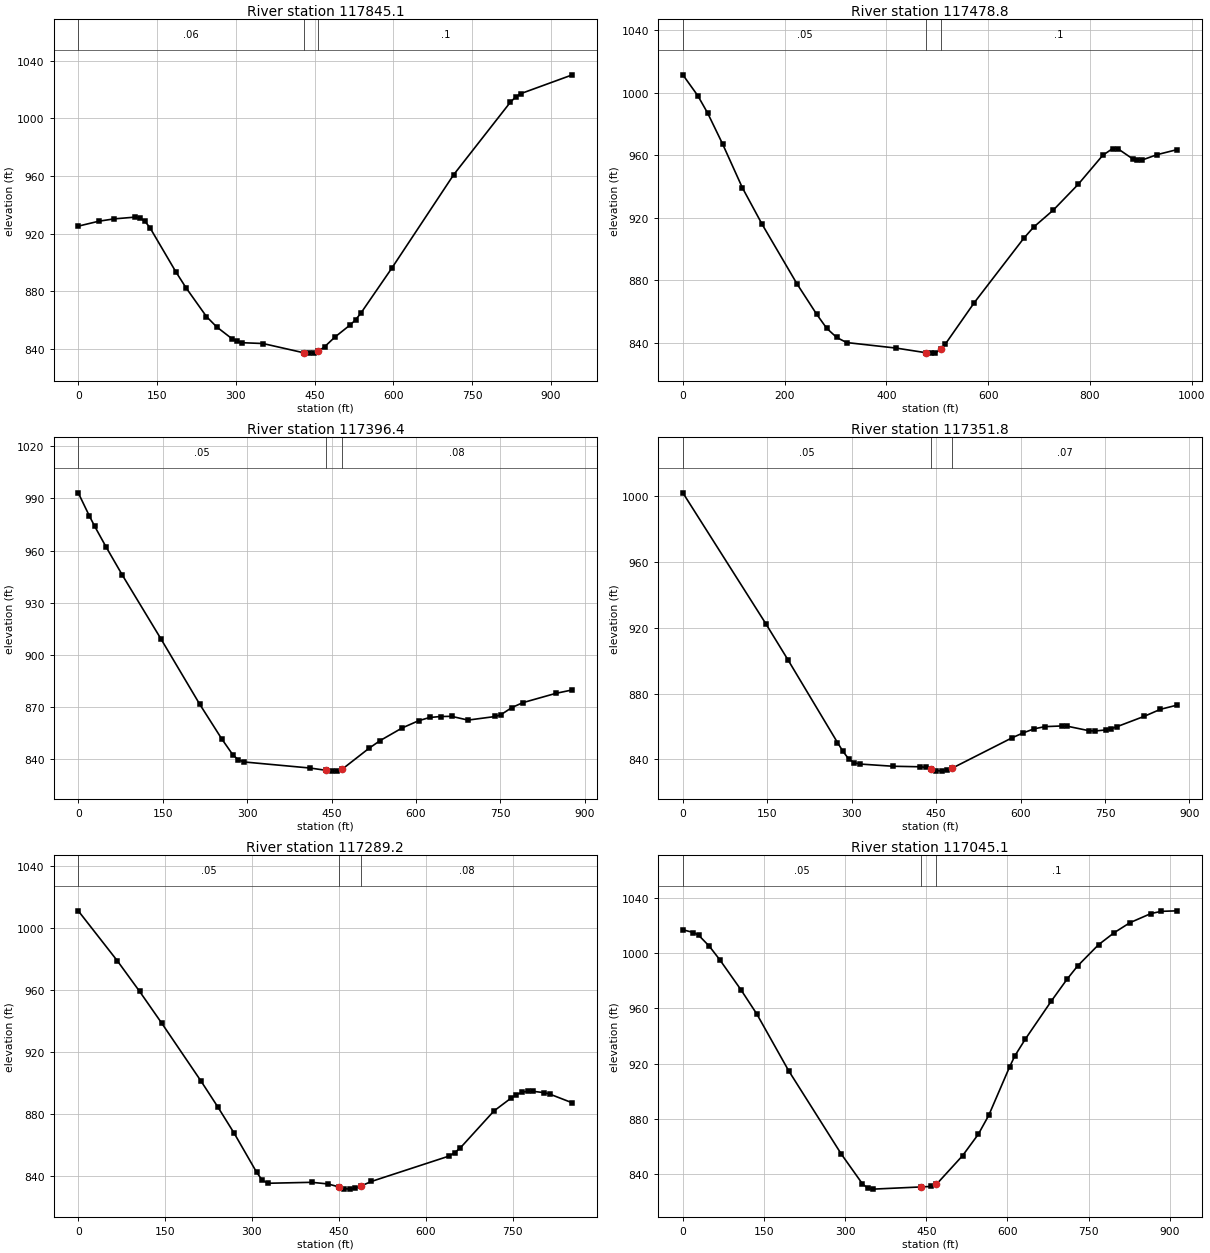
Type RM Length L Ch R = 1 ,117845.1,362.9,366.3,364.8
XS GIS Cut Line= 3
     1914720.282       607597.27     1915164.098      607527.932
     1915655.606      607538.653
#Sta/Elev= 30
       0  925.11    39.1  928.54    68.4  930.16   107.4  931.35   117.2  930.85
     127   928.5   136.7  923.92   185.5  893.63   205.1   882.4   244.1  862.39
   263.7  855.16     293  846.92   302.7   845.1   312.5  844.23   351.6  843.68
   429.7  837.22   439.4  837.01   449.2   837.2   456.7  838.18   468.9  841.38
   488.5   848.1     518  856.65   527.9  860.11   537.7  864.54   596.7  895.81
   714.7  960.77   822.8 1011.14   832.7 1014.71   842.5 1017.05   940.8 1030.11
#Mann= 3 , 0 , 0
       0     .06       0   429.7    .045       0   456.7      .1       0
Bank Sta=429.7,456.7
XS Rating Curve= 0 ,0
Exp/Cntr=0.3,0.1

Type RM Length L Ch R = 1 ,117478.8,72.7,82.4,92.1
XS GIS Cut Line= 4
     1914781.177        607807.9     1915244.608       607874.05
     1915329.788      607872.136     1915746.812      607845.389
#Sta/Elev= 30
       0 1011.46    29.3  998.14    48.8  986.93      78  967.27     117  939.13
     156  915.62   224.3  877.63   263.3     858   282.8  849.14   302.3   843.3
   321.8  840.03   419.4  836.47   477.6  833.52   487.1  833.25   496.5   833.5
   507.3  835.61   515.5  838.86   572.8  865.58     670  906.78   689.4  913.92
   728.3   924.9   776.8  941.26   825.4  959.96   844.9  964.27   854.6  964.23
   883.8  957.72   893.5   956.8   903.2  956.98   932.3  960.36   971.2  963.56
#Mann= 3 , 0 , 0
       0     .05       0   477.6    .045       0   507.3      .1       0
Bank Sta=477.6,507.3
XS Rating Curve= 0 ,0
Exp/Cntr=0.3,0.1

Type RM Length L Ch R = 1 ,117396.4,44.4,44.6,44.9
XS GIS Cut Line= 4
      1914824.58      607887.761     1915242.983      607941.581
     1915312.427      607971.095     1915689.163      608024.914
#Sta/Elev= 30
       0  993.17    19.6  979.98    29.4  973.83      49  962.32    78.5   945.8
   147.2  909.08   215.8  871.68   255.1  851.69   274.7   842.6   284.5   839.7
   294.3  838.52     412  835.01   440.7  833.69   450.2  833.24   459.6  833.34
     469  834.37   516.8  846.41   536.3  850.78   575.4  858.04   604.6  862.19
   624.2  864.06   643.7  864.63   663.2  864.73   692.5  862.57   741.3  864.65
     751  865.68   770.5   869.8     790   872.6   848.6  877.94   877.9  879.92
#Mann= 3 , 0 , 0
       0     .05       0   440.7    .045       0     469     .08       0
Bank Sta=440.7,469
XS Rating Curve= 0 ,0
Exp/Cntr=0.3,0.1

Type RM Length L Ch R = 1 ,117351.8,67.2,62.5,57.9
XS GIS Cut Line= 4
     1914814.163      607929.428     1915232.566      607983.247
     1915302.011      608012.761     1915678.747      608066.581
#Sta/Elev= 30
       0    1002   147.2  922.58   186.4  900.71   274.7  850.27   284.5  844.85
   294.3  840.46   304.1  838.01   313.9  837.21   372.8  835.85   421.8  835.52
   431.3  835.18   440.7  834.29   450.2  833.26   459.6  832.88     469  833.37
   478.4  834.65   585.1  853.16   604.6  856.11   624.2   858.6   643.7  859.93
     673  860.32   682.7   860.2   721.7  857.43   731.5  857.26     751  857.88
   760.8  858.61   770.5  859.79   819.3  866.13   848.6  870.46   877.9  872.98
#Mann= 3 , 0 , 0
       0     .05       0   440.7    .045       0   478.4     .07       0
Bank Sta=440.7,478.4
XS Rating Curve= 0 ,0
Exp/Cntr=0.3,0.1

Type RM Length L Ch R = 1 ,117289.2,236.8,244.2,254.1
XS GIS Cut Line= 4
     1914802.011      607965.886     1915150.969      608037.067
     1915343.677      608078.734      1915637.08      608141.234
#Sta/Elev= 30
       0  1011.1    67.4  978.92   105.9  959.18   144.4  938.54   211.8  901.45
   240.6  884.92   269.5  867.57     308  842.59   317.6  837.48   327.3  835.47
   403.1  836.08   431.2  835.04     450  833.12   459.4  832.03   468.8  831.69
   478.2   832.2   487.6  833.61   506.4  836.66   640.4  853.01   650.1  855.23
   659.8  858.27   717.8  882.06   746.8  890.19   756.5  892.55   766.2  894.14
   775.9  894.78   785.6  894.74   804.9  893.87   814.6   892.9   853.3   887.3
#Mann= 3 , 0 , 0
       0     .05       0     450    .045       0   487.6     .08       0
Bank Sta=450,487.6
XS Rating Curve= 0 ,0
Exp/Cntr=0.3,0.1

Type RM Length L Ch R = 1 ,117045.1,337.1,336.7,333.6
XS GIS Cut Line= 3
     1914789.253      608054.004     1915183.501      608289.029
     1915544.029      608565.444
#Sta/Elev= 30
       0  1016.8    19.5 1014.83    29.3  1012.8    48.8 1004.97    68.4  995.04
   107.4  973.41   136.7  955.88   195.3  915.03     293   854.5     332  833.02
   341.8  829.92   351.6  829.24   439.4  830.81     459  831.19   468.6  832.68
     517  853.43     546  868.89   565.3  882.54     604  917.71   613.6  925.59
     633  937.75   681.3   965.4   710.3  981.16   729.6  990.63   768.3 1006.01
   797.3 1014.72   826.3 1021.92     865 1028.52   884.3 1030.14   913.3 1030.51
#Mann= 3 , 0 , 0
       0     .05       0   439.4    .045       0   468.6      .1       0
Bank Sta=439.4,468.6
XS Rating Curve= 0 ,0
Exp/Cntr=0.3,0.1

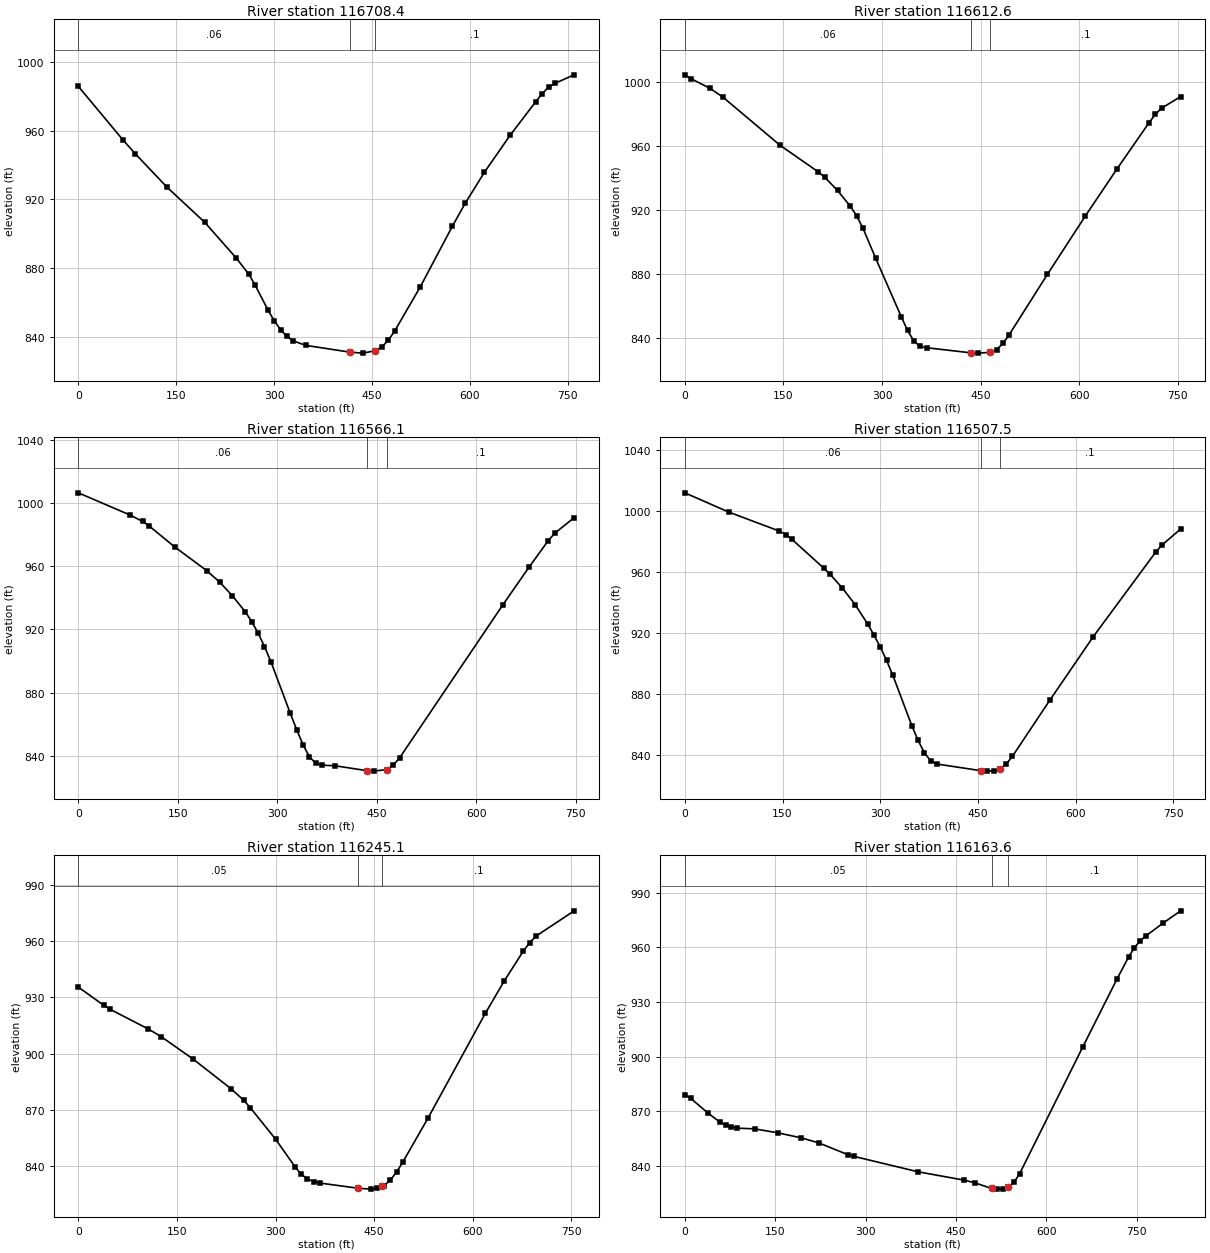
Type RM Length L Ch R = 1 ,116708.4,95.8,95.8,95.8
XS GIS Cut Line= 3
     1914631.655      608360.194     1915026.701      608585.946
       1915291.1      608737.039
#Sta/Elev= 30
       0  985.64    67.8  954.77    87.1  946.54   135.5  927.19   193.6  906.66
     242  885.85   261.4  876.35   271.1  869.97   290.4  855.74   300.1  849.45
   309.8  844.26   319.5  840.35   329.2  837.74   348.5  835.14   416.3   831.2
   435.6  830.64     455  832.05   464.8  834.14   474.6  838.06   484.5  843.44
   523.8  869.14   572.9  904.34   592.5  917.65     622  935.72   661.3  957.17
   700.6  976.71   710.4  981.36   720.2  985.16   730.1  987.41   759.5  992.35
#Mann= 3 , 0 , 0
       0     .06       0   416.3    .045       0     455      .1       0
Bank Sta=416.3,455
XS Rating Curve= 0 ,0
Exp/Cntr=0.3,0.1

Type RM Length L Ch R = 1 ,116612.6,46.5,46.5,46.5
XS GIS Cut Line= 3
     1914570.023      608435.281     1914965.069      608661.033
     1915224.828      608809.474
#Sta/Elev= 30
       0 1004.54     9.7 1002.08    38.7     996    58.1  990.54   145.2  960.37
   203.3  943.75     213  940.38   232.3  932.18   251.7  922.38   261.4  916.35
   271.1  908.46   290.4  889.73   329.2  853.23   338.8  844.64   348.5  837.92
   358.2  834.59   367.9  833.79   435.6  830.59   445.3  830.42   464.6  830.91
   474.3  832.63     484  836.46   493.6  842.04   551.5  879.65   609.4   916.3
   657.7  945.85   705.9  974.43   715.6  979.73   725.2  983.69   754.2  990.89
#Mann= 3 , 0 , 0
       0     .06       0   435.6    .045       0   464.6      .1       0
Bank Sta=435.6,464.6
XS Rating Curve= 0 ,0
Exp/Cntr=0.3,0.1

Type RM Length L Ch R = 1 ,116566.1,58.6,58.6,58.6
XS GIS Cut Line= 3
      1914549.19      608476.948     1914944.236      608702.699
     1915198.323      608847.899
#Sta/Elev= 30
       0 1006.66    77.4  992.68    96.8  988.55   106.5  985.74   145.2  972.37
   193.6   957.3     213  950.06   232.3  941.36   251.7   931.2   261.4     925
   271.1  917.67   280.7  909.17   290.4  899.52   319.5  866.89   329.2  856.48
   338.8  846.86   348.5  839.18   358.2  835.03   367.9  833.91   387.2  833.53
   435.6  830.41   445.3  830.14   464.8   831.1   474.5  833.78   484.3  838.48
   640.3  935.75   679.4   959.4   708.6  976.38   718.4  981.02   747.6  990.94
#Mann= 3 , 0 , 0
       0     .06       0   435.6    .045       0   464.8      .1       0
Bank Sta=435.6,464.8
XS Rating Curve= 0 ,0
Exp/Cntr=0.3,0.1

Type RM Length L Ch R = 1 ,116507.5,264,262.4,260.8
XS GIS Cut Line= 3
     1914504.051      608518.614     1914899.097      608744.366
     1915164.946      608896.288
#Sta/Elev= 30
       0 1011.72    67.8  999.06   145.2  986.67   154.9  984.41   164.6  981.23
     213  962.54   222.7  958.56     242  949.36   261.4  938.57   280.7   925.9
   290.4  918.59   300.1  910.83   309.8  901.96   319.5  892.14   348.5  859.32
   358.2  849.63   367.9  841.49   377.6   836.2   387.2  834.17     455   829.8
   464.6  829.53   474.1  829.74   483.7  830.88   493.3  834.07   502.8  839.11
   560.2  875.84   627.2  917.63   722.9  972.89   732.5  977.52   761.2     988
#Mann= 3 , 0 , 0
       0     .06       0     455    .045       0   483.7      .1       0
Bank Sta=455,483.7
XS Rating Curve= 0 ,0
Exp/Cntr=0.3,0.1

Type RM Length L Ch R = 1 ,116245.1,85.7,81.5,76.9
XS GIS Cut Line= 3
     1914381.599       608787.32     1914791.551      608984.715
     1915061.037      609114.475
#Sta/Elev= 30
       0  935.54    38.7  925.78    48.4  923.65   106.5  913.13   125.8   909.1
   174.3  897.14   232.3  881.19   251.7  875.02   261.4  871.13   300.1  854.21
   329.2  839.65   338.8  835.52   348.5  833.02   358.2  831.59   367.9  830.78
     426  828.02   445.3  827.56     455  827.99   462.5  829.11   464.6  829.42
   474.3  832.24     484  836.67   493.6  842.08   532.2  865.75     619  921.52
     648  938.95   676.9  954.85   686.6  959.31   696.2   962.8   754.1   976.3
#Mann= 3 , 0 , 0
       0     .05       0     426    .045       0   462.5      .1       0
Bank Sta=426,462.5
XS Rating Curve= 0 ,0
Exp/Cntr=0.3,0.1

Type RM Length L Ch R = 1 ,116163.6,44.9,44.8,44.9
XS GIS Cut Line= 4
     1914258.608      608896.442     1914661.386      609033.595
     1914814.163      609073.525     1915041.594      609148.178
#Sta/Elev= 30
       0  879.21     9.7   877.2    38.7  869.03      58  864.21    67.7  862.54
    77.4  861.41      87  860.82     116  860.41   154.7  858.23   193.4  855.47
   222.4  852.73   270.8  846.22   280.4  845.35   386.8  836.87   462.6  832.33
   481.2  830.82   509.1   827.7   518.4  827.34   527.7  827.54     537  828.48
   546.2  831.05   555.5  835.73     660  905.11   717.4  942.82   736.6  954.84
   746.2  959.94   755.7  963.68   765.3  966.37     794  973.46   822.8  980.12
#Mann= 3 , 0 , 0
       0     .05       0   509.1    .045       0     537      .1       0
Bank Sta=509.1,537
XS Rating Curve= 0 ,0
Exp/Cntr=0.3,0.1

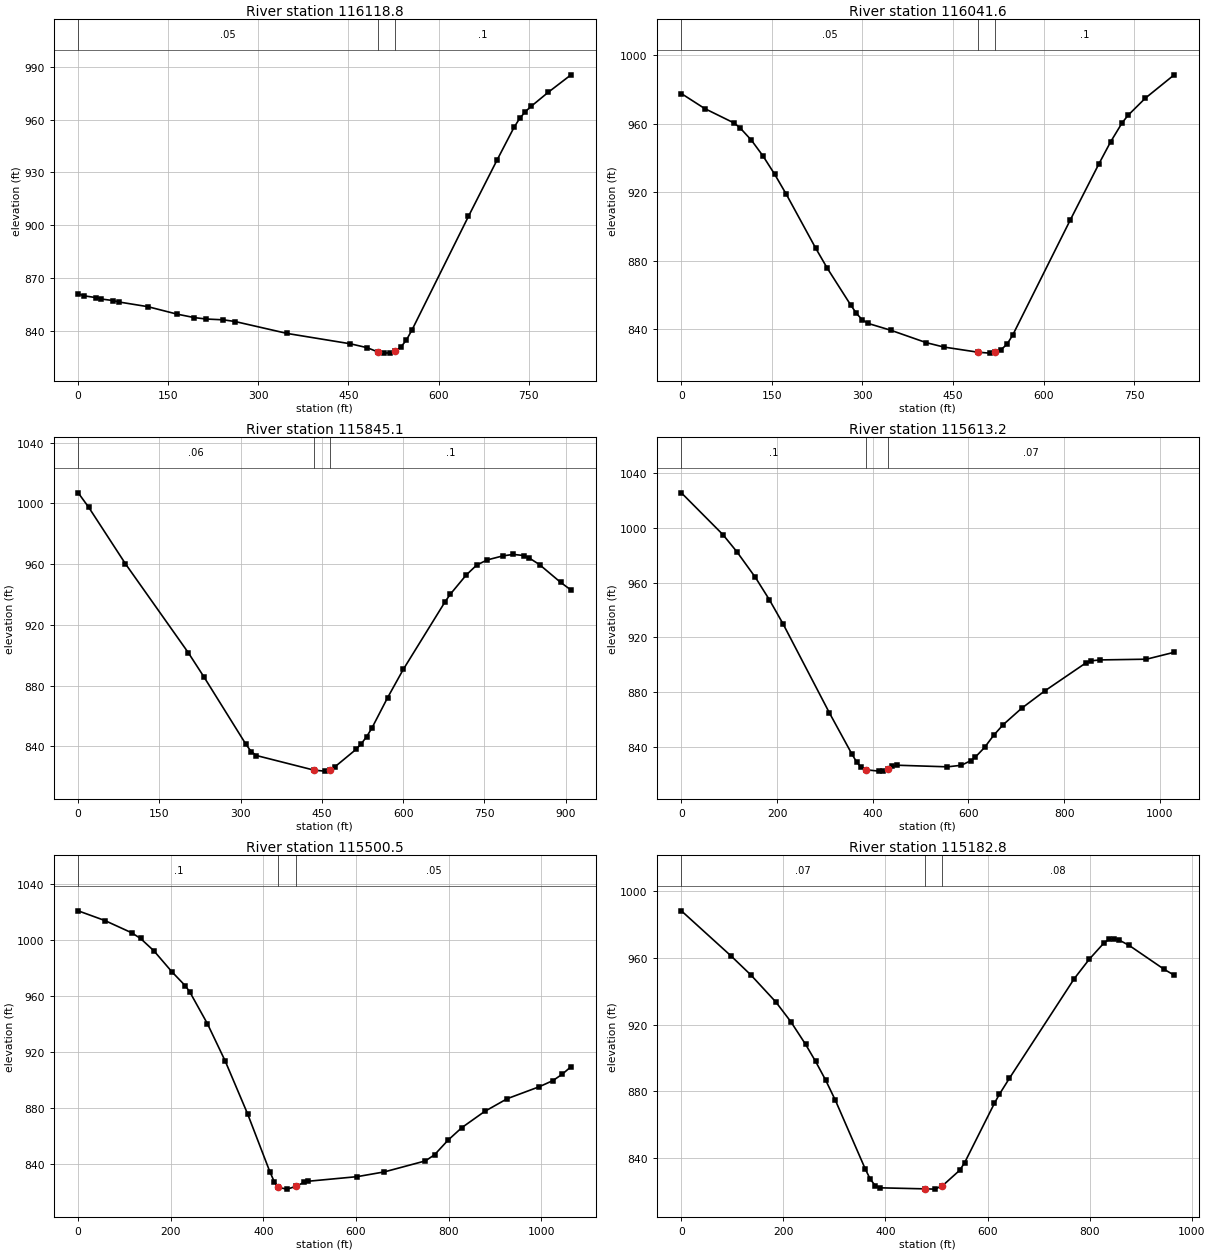
Type RM Length L Ch R = 1 ,116118.8,80.9,77.2,73.5
XS GIS Cut Line= 4
     1914249.927      608939.845     1914652.705      609076.997
     1914805.483      609116.928     1915031.177      609189.845
#Sta/Elev= 30
       0  860.93     9.7   859.8      29   858.8    38.7  857.96      58   857.1
    67.7  856.29     116  853.62   164.4  849.39   193.4   847.4   212.7   846.6
   241.8  846.13   261.1  845.18   348.1  838.37   453.4  832.49   481.2  830.28
   499.8  827.76   509.1  827.19   518.4  827.34   527.7  828.29     537  830.52
   546.2  834.51   555.5  840.16   649.8  904.98   697.2  936.88   725.7  955.62
   735.2  960.76   744.7  964.61   754.2  967.58   782.6  975.56   820.6  985.51
#Mann= 3 , 0 , 0
       0     .05       0   499.8    .045       0   527.7      .1       0
Bank Sta=499.8,527.7
XS Rating Curve= 0 ,0
Exp/Cntr=0.3,0.1

Type RM Length L Ch R = 1 ,116041.6,197.9,196.5,194.8
XS GIS Cut Line= 4
     1914209.997      609169.011     1914635.344      609165.539
     1914786.386      609179.428     1915021.465      609224.354
#Sta/Elev= 30
       0  977.55    38.7   968.8      87  960.44    96.7  957.75     116  950.37
   135.3  941.13   154.7  930.41     174  918.72   222.4  887.46   241.7   875.7
   280.4  854.31     290  849.36   299.7  845.59   309.4   843.5     348   839.4
     406  832.25   434.8  829.73   491.7   826.7   510.7  826.18   520.2   826.8
   529.6  828.25   539.1  831.22   548.6  836.51     644  903.66   691.9  936.71
   711.1  949.42   730.2  960.52   739.8  964.81   768.5  974.84   816.4  988.48
#Mann= 3 , 0 , 0
       0     .05       0   491.7    .045       0   520.2      .1       0
Bank Sta=491.7,520.2
XS Rating Curve= 0 ,0
Exp/Cntr=0.3,0.1

Type RM Length L Ch R = 1 ,115845.1,232.6,231.9,231.6
XS GIS Cut Line= 3
     1914262.518      609354.597     1914717.364      609369.412
     1915172.299      609376.112
#Sta/Elev= 30
       0 1006.98    19.4  997.46    87.1  960.33   203.3   901.7   232.4  885.65
   309.8  841.32   319.5  836.56   329.2  833.95   435.7  824.31   455.1  823.68
   464.8  824.45   474.4  826.61   513.2  838.03   522.8  841.71   532.5  846.29
   542.2  851.91   571.2  871.95   600.3  890.65   677.7  935.32   687.4   940.3
   716.5  952.82   735.8  959.36   755.2  962.78   784.2  965.44   803.6  966.43
     823  965.66   832.6  964.12     852  959.68   890.7  948.07   910.1  942.94
#Mann= 3 , 0 , 0
       0     .06       0   435.7    .045       0   464.8      .1       0
Bank Sta=435.7,464.8
XS Rating Curve= 0 ,0
Exp/Cntr=0.3,0.1

Type RM Length L Ch R = 1 ,115613.2,111.1,112.7,114.3
XS GIS Cut Line= 4
     1914270.761      609550.956     1914586.733      609596.095
     1914746.455      609596.095     1915265.552      609410.331
#Sta/Elev= 30
       0 1025.48      87  994.92   116.1  982.45   154.8  963.72   183.8  947.56
   212.8  929.69   309.5  864.85   356.8  834.61   366.2  829.16   375.6  825.18
     385  823.37   413.1  822.37   422.5   822.7   431.9  824.06   441.3  825.97
   450.7  826.68   556.3  825.51   585.3  826.64   604.6  829.94   614.3   832.5
   633.7  839.63     653  848.59   672.4  856.16     711  868.16   759.4  880.84
   846.5  901.57   856.1  902.86   875.5  903.53   972.2  904.06  1030.2  909.11
#Mann= 3 , 0 , 0
       0      .1       0     385    .045       0   431.9     .07       0
Bank Sta=385,431.9
XS Rating Curve= 0 ,0
Exp/Cntr=0.3,0.1

Type RM Length L Ch R = 1 ,115500.5,309.3,317.7,326
XS GIS Cut Line= 4
     1914206.907      609693.623     1914630.136       609705.47
     1914749.927       609714.15     1915260.344      609818.317
#Sta/Elev= 30
       0 1021.18    57.7 1014.23   115.5 1005.49   134.7 1001.41   163.6  992.55
   202.1  977.71   230.9  967.75   240.6  963.44   279.1  940.49   317.6  913.75
   365.7   876.2   413.8  834.81   423.4  827.57   432.6  823.45   451.1  822.24
   469.6  824.12   488.1  827.17   497.3  827.89   602.5  831.16   661.4  834.57
   749.9  842.43   769.6  846.79     799  857.31   828.5  866.18   877.7  877.74
   926.8  886.92   995.6   895.4  1025.1   899.8  1044.8  904.21  1064.4  909.76
#Mann= 3 , 0 , 0
       0      .1       0   432.6    .045       0   469.6     .05       0
Bank Sta=432.6,469.6
XS Rating Curve= 0 ,0
Exp/Cntr=0.3,0.1

Type RM Length L Ch R = 1 ,115182.8,269.7,282.6,295.6
XS GIS Cut Line= 4
      1914161.17      609794.639     1914527.705      609976.303
     1914694.372      610056.164     1915010.344      610252.345
#Sta/Elev= 30
       0  987.88    97.4  960.93   136.4  949.52   185.1  933.47   214.3  921.77
   243.5  908.11     263  897.98   282.5  886.94   301.9  874.68   360.4  833.72
   370.1  827.68   379.9  823.78   389.6  822.48   477.2  821.86   496.5   821.7
   511.5  823.66   545.3  832.92     555  837.43   613.5  872.96   623.3  878.38
   642.8  887.86   770.1  947.45   799.4  958.99   828.8  968.91   838.6  970.88
   848.4  971.21   858.2  970.38   877.7   967.2   946.2  952.93   965.8  949.44
#Mann= 3 , 0 , 0
       0     .07       0   477.2    .045       0   511.5     .08       0
Bank Sta=477.2,511.5
XS Rating Curve= 0 ,0
Exp/Cntr=0.3,0.1