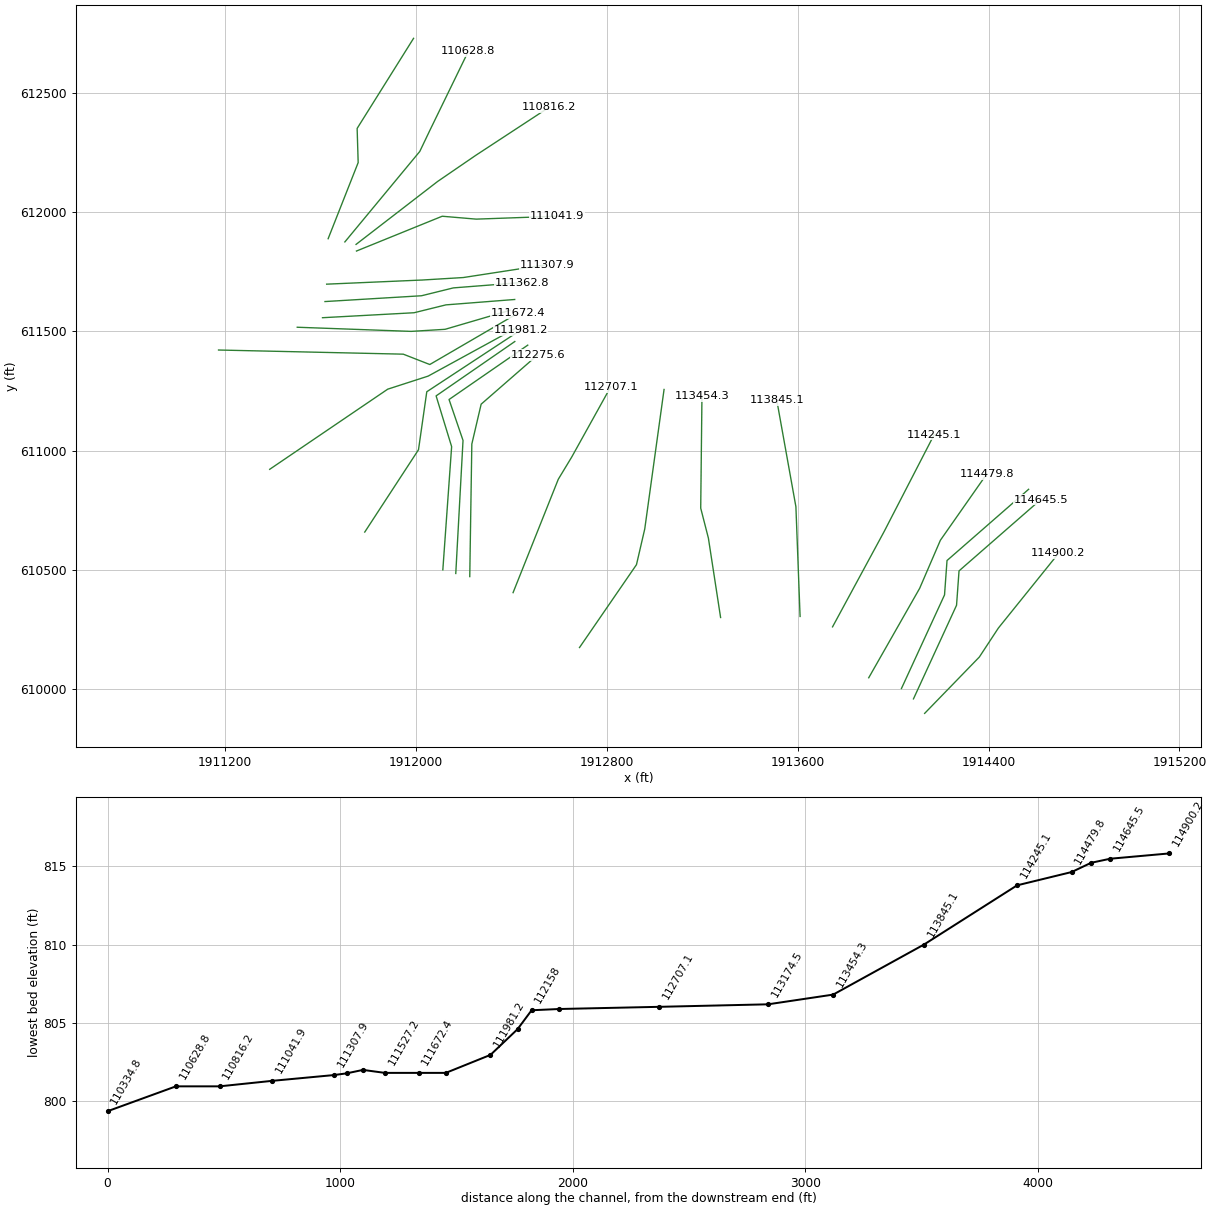
HEC-RAS study HenryFork.prj: HenryFork

--- HenryFork.g01 (geometry) --- (continued)

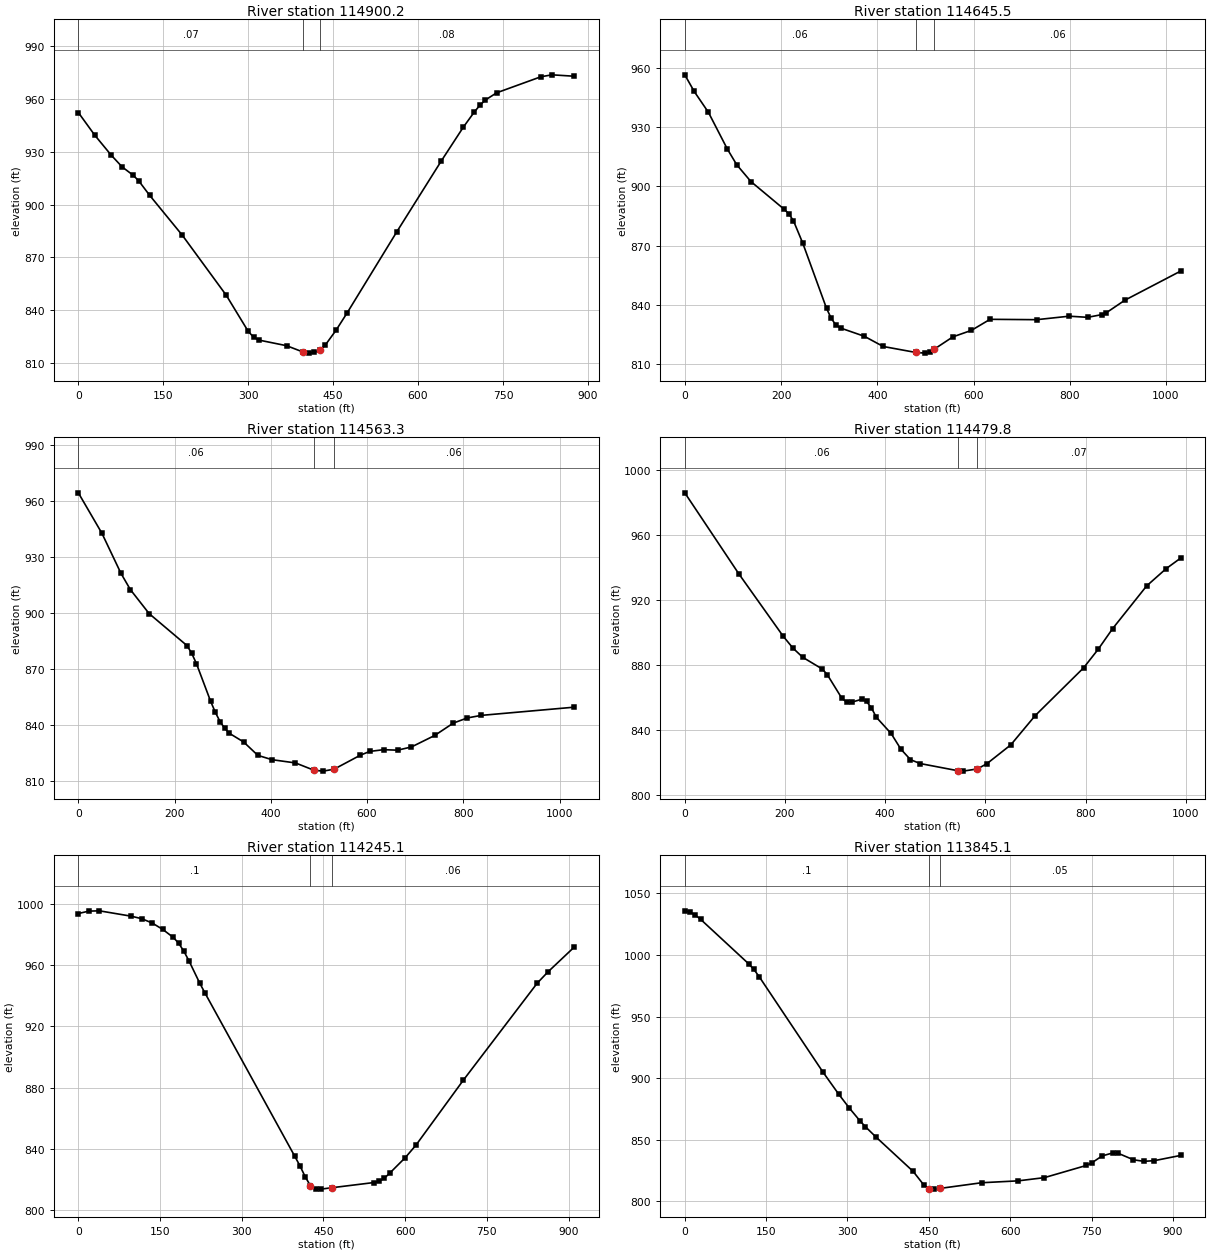
Type RM Length L Ch R = 1 ,114900.2,237.1,254.7,273.2
XS GIS Cut Line= 4
     1914131.872      609898.178     1914361.038      610134.289
       1914440.9      610255.817     1914692.636      610568.317
#Sta/Elev= 30
       0  952.13      29  939.29    58.1  927.96    77.4  921.31    96.8   916.6
   106.4  913.53   125.8  905.28   183.9   882.5   261.3  848.58     300  828.18
   309.7  824.79   319.4  823.18   367.8  820.03   396.9  816.45   406.6  815.82
   416.3  816.25     426  817.34   435.7  820.18   455.1  828.76   474.5  838.48
   562.5  884.58   640.8  924.57     680  943.86   699.6  952.52   709.4  956.31
   719.1  959.26   738.7  963.28     817  972.39   836.6  973.48   875.7  972.69
#Mann= 3 , 0 , 0
       0     .07       0   396.9    .045       0     426     .08       0
Bank Sta=396.9,426
XS Rating Curve= 0 ,0
Exp/Cntr=0.3,0.1

Type RM Length L Ch R = 1 ,114645.5,82.8,82.2,79.8
XS GIS Cut Line= 4
     1914084.997      609958.942     1914265.552      610351.303
     1914275.969        610495.4     1914617.983      610794.011
#Sta/Elev= 30
       0  956.63    19.6  948.18    49.1   937.6    88.4  918.99     108     911
   137.4   902.5   206.1  888.52     216   886.2   225.8  882.61   245.4   871.1
   294.5  838.21   304.3  833.12   314.1  829.69   323.9  828.19     373  824.04
   412.3  818.85   480.1  815.82   499.3  815.48     509  815.97   518.6  817.52
   557.1  823.73   595.7  827.03   634.4  832.63     731  832.44   798.6  834.21
   837.2  833.64   866.2  834.99   875.8  835.93   914.5  842.32  1030.4  857.08
#Mann= 3 , 0 , 0
       0     .06       0   480.1    .045       0   518.6     .06       0
Bank Sta=480.1,518.6
XS Rating Curve= 0 ,0
Exp/Cntr=0.3,0.1

Type RM Length L Ch R = 1 ,114563.3,96.7,83.5,71
XS GIS Cut Line= 4
      1914034.65      610002.345     1914215.205      610394.706
     1914225.622      610538.803     1914567.636      610837.414
#Sta/Elev= 30
       0   964.2    49.1   942.5    88.4  921.19     108  912.44   147.2  899.53
   225.8  882.42   235.6  878.31   245.4  872.79   274.8  852.68   284.7   846.7
   294.5  841.74   304.3  838.09   314.1  835.43   343.6  830.81     373  823.67
   402.5  821.34   451.2  819.61   489.7   815.7     509  815.22   531.6  816.27
     586  823.74   605.4  825.76   634.4   826.7   663.3  826.43   692.3  828.16
   740.6  834.31   779.2  840.93   808.2  843.68   837.2  845.06  1030.4  849.45
#Mann= 3 , 0 , 0
       0     .06       0   489.7    .045       0   531.6     .06       0
Bank Sta=489.7,531.6
XS Rating Curve= 0 ,0
Exp/Cntr=0.3,0.1

Type RM Length L Ch R = 1 ,114479.8,237,234.7,232.9
XS GIS Cut Line= 4
     1913897.497      610047.484     1914111.038      610422.484
     1914197.844      610623.872     1914392.288       610901.65
#Sta/Elev= 30
       0  986.03   107.9  936.12   196.2  897.81   215.8  890.43   235.4  884.75
   274.6  877.49   284.4  874.08   313.8  859.38   323.6  857.09   333.5  857.12
   353.1  858.87   362.9  857.55   372.7  853.48   382.5  847.77   411.9  837.81
   431.5  828.11   450.6  821.69   469.7  819.31     546  814.83   555.5  814.63
   584.1  815.98   603.2  819.22   650.8   830.8   699.3  848.74   796.2  878.25
   825.2  889.63   854.3  902.46   922.1  928.71   960.8  939.28   989.9  945.82
#Mann= 3 , 0 , 0
       0     .06       0     546    .045       0   584.1     .07       0
Bank Sta=546,584.1
XS Rating Curve= 0 ,0
Exp/Cntr=0.3,0.1

Type RM Length L Ch R = 1 ,114245.1,387.8,400,414.6
XS GIS Cut Line= 3
     1913745.858      610260.833     1913962.494      610661.072
     1914171.157      611065.383
#Sta/Elev= 30
       0  993.54    19.4  995.11    38.7   995.3    96.8  991.82   116.2  990.19
   135.6  987.35   154.9  983.18   174.3  977.96     184  974.25   193.7  968.96
   203.4  962.45   222.7  948.22   232.4  941.73     397  835.38   406.7  829.04
   416.4  821.87   426.1  815.95   435.7  813.92   445.4  813.78   464.8  814.67
   542.2  818.06   551.9  818.88   561.6  820.89   571.3   824.1   600.3   834.4
   619.7  842.46   706.8   884.9   842.3  948.12   861.7  955.36   910.1   971.6
#Mann= 3 , 0 , 0
       0      .1       0   426.1    .045       0   464.8     .06       0
Bank Sta=426.1,464.8
XS Rating Curve= 0 ,0
Exp/Cntr=0.3,0.1

Type RM Length L Ch R = 1 ,113845.1,386.1,390.8,392.4
XS GIS Cut Line= 3
     1913609.773      610304.477     1913592.233      610764.378
     1913512.003       611211.31
#Sta/Elev= 30
       0  1035.8     9.8 1034.83    19.6 1032.31    29.4 1028.81   117.5  992.93
   127.3   988.3   137.1  982.42   254.6  905.06     284  886.92   303.6  875.66
   323.1  865.35   332.9   860.7   352.5  852.28   421.1  824.37   440.6  813.46
   450.4  810.37   460.2     810   469.9  810.54   547.2  815.18   614.8  816.72
   663.1  819.33   740.4  829.21   750.1  831.19   769.4  836.91   788.7  839.32
   798.4  839.21   827.4   833.8   846.7  832.54     866  833.11   914.3  837.34
#Mann= 3 , 0 , 0
       0      .1       0   450.4    .045       0   469.9     .05       0
Bank Sta=450.4,469.9
XS Rating Curve= 0 ,0
Exp/Cntr=0.3,0.1

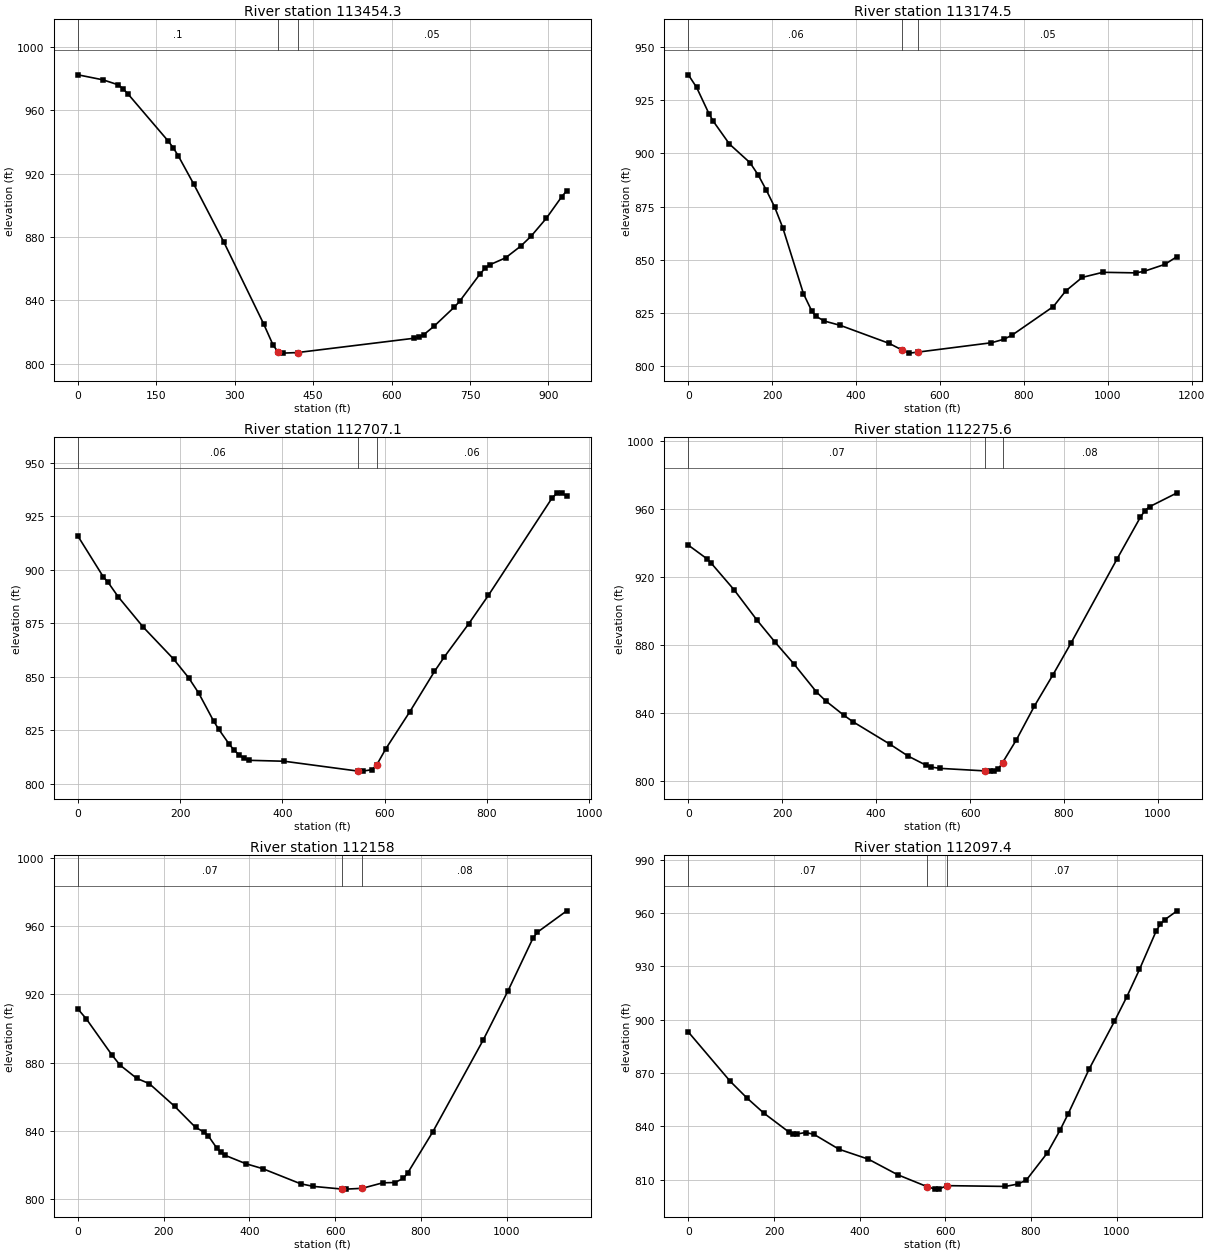
Type RM Length L Ch R = 1 ,113454.3,290.3,279.9,268.6
XS GIS Cut Line= 4
     1913276.577      610300.088     1913225.443      610632.704
     1913193.243      610758.421     1913198.452      611227.171
#Sta/Elev= 30
       0  982.32    48.1  979.14    76.9  976.03    86.5  973.48    96.2  970.04
   173.1  940.36   182.7  936.07   192.3  930.98   221.1  913.62   278.8     877
   355.1  825.31   373.6  811.63   382.9  807.56   392.1   806.8     420  807.16
   642.1  816.15   651.9  816.88   661.6  818.48   681.2  823.76   720.2  835.91
     730  839.44     769  856.66   778.8  860.32   788.6  862.64   817.9  866.87
   847.2  874.34   866.7   880.5     896  891.84   925.3  905.37   935.1  909.28
#Mann= 3 , 0 , 0
       0      .1       0   382.9    .045       0     420     .05       0
Bank Sta=382.9,420
XS Rating Curve= 0 ,0
Exp/Cntr=0.3,0.1

Type RM Length L Ch R = 1 ,113174.5,474.3,467.3,460.3
XS GIS Cut Line= 4
     1912685.257       610174.22     1912923.972      610521.442
     1912958.695      610671.182     1913039.597      611255.817
#Sta/Elev= 30
       0  936.92    19.6  931.04      49  918.71    58.8  915.28      98  904.39
     147  895.63   166.6  889.83   186.2  882.62   205.8  874.78   225.4  864.92
   274.4  834.09     294  826.05   303.8  823.56   323.4   821.3   362.6   819.2
     479  810.74   510.1  807.58     527  806.18   546.3  806.63   722.6  811.06
   752.1  812.68   771.8  814.64   870.2  828.06   899.7  835.39     939  841.76
   988.2  844.15  1066.9  843.88  1086.6  844.62  1135.8  847.87  1165.3  851.55
#Mann= 3 , 0 , 0
       0     .06       0   510.1    .045       0   546.3     .05       0
Bank Sta=510.1,546.3
XS Rating Curve= 0 ,0
Exp/Cntr=0.3,0.1

Type RM Length L Ch R = 1 ,112707.1,423.6,431.5,439.2
XS GIS Cut Line= 4
     1912406.785      610404.254     1912596.281      610879.515
     1912652.705      610972.831     1912815.639      611266.234
#Sta/Elev= 30
       0   915.7    49.2  896.86      59  894.12    78.7  887.42   127.9  873.19
     187  858.36   216.5  849.62   236.1  842.49   265.7  829.26   275.5  825.53
   295.2  818.82     305  815.91   314.9   813.7   324.7  811.98   334.5  811.07
   403.4  810.64     548  806.03   557.1  806.02   575.3   806.7   584.2  808.83
   602.5  816.54   649.5  833.86   697.4  852.55   716.6   859.3   764.5  874.84
   802.9  888.07   927.5  933.53   937.1  935.76   946.7  935.96   956.3  934.25
#Mann= 3 , 0 , 0
       0     .06       0     548    .045       0   584.2     .06       0
Bank Sta=548,584.2
XS Rating Curve= 0 ,0
Exp/Cntr=0.3,0.1

Type RM Length L Ch R = 1 ,112275.6,110.1,117.6,118.1
XS GIS Cut Line= 4
     1912225.188      610471.529     1912233.868      611027.084
     1912272.931      611194.185     1912509.476      611400.348
#Sta/Elev= 30
       0  938.61      39  930.72    48.7  928.02    97.5  912.34   146.2  894.56
   185.2  881.45   224.2  869.04   272.9  852.35   292.4  847.17   331.4  838.65
   350.9  834.83   428.9  821.76   467.9  814.74   506.9  809.25   516.6  808.27
   536.1   807.5   631.9  806.01   641.4  805.88     651  805.96   660.5  807.35
   669.3  810.93   698.6  824.26     737   844.1   776.3  862.37   815.5  881.39
   913.5  930.76   962.6  954.99   972.4  958.89   982.2  961.19    1041  969.35
#Mann= 3 , 0 , 0
       0     .07       0   631.9    .045       0   669.3     .08       0
Bank Sta=631.9,669.3
XS Rating Curve= 0 ,0
Exp/Cntr=0.3,0.1

Type RM Length L Ch R = 1 ,112158  ,56.4,60.6,71.2
XS GIS Cut Line= 4
     1912166.594       610484.55     1912196.976      611042.275
     1912138.382      611213.716     1912468.243      611441.581
#Sta/Elev= 30
       0  911.42    19.6  905.62    78.4  884.78      98  878.59   137.2  870.78
   166.6  867.65   225.4  854.42   274.4     842     294  839.34   303.8  837.15
   323.4  830.08   333.2  827.36     343  825.66     392  820.69   431.2   817.8
   519.4  808.95   548.8  807.42   615.8  805.84   625.3   805.8   663.4  806.28
   711.1   809.5   739.7  809.68   759.3  812.13   769.1  815.16   827.7  839.29
   945.1  893.04  1003.8   922.3  1062.4  953.38  1072.2  956.56  1140.6  969.07
#Mann= 3 , 0 , 0
       0     .07       0   615.8    .045       0   663.4     .08       0
Bank Sta=615.8,663.4
XS Rating Curve= 0 ,0
Exp/Cntr=0.3,0.1

Type RM Length L Ch R = 1 ,112097.4,124.2,116.2,107.9
XS GIS Cut Line= 4
      1912112.34      610499.741     1912149.233      611016.234
     1912084.129      611228.907      1912413.99      611456.772
#Sta/Elev= 30
       0  893.08    97.7  865.33   136.8  855.92   175.9  847.46   234.5  836.79
   244.2  835.87     254  835.66   273.6  836.48   293.1  835.47   351.7  827.05
   420.1  821.48   488.5  812.71   556.5  806.06   575.8  804.59   585.5  804.79
   604.8  806.55   740.2  806.11   769.6  807.48   789.1  809.71     838  824.98
   867.3  837.63   886.9  847.11   935.8  872.27   994.5  899.01  1023.8  913.03
  1053.1   928.3  1092.2  950.01    1102  953.91  1111.8  956.28  1141.1  961.34
#Mann= 3 , 0 , 0
       0     .07       0   556.5    .045       0   604.8     .07       0
Bank Sta=556.5,604.8
XS Rating Curve= 0 ,0
Exp/Cntr=0.3,0.1

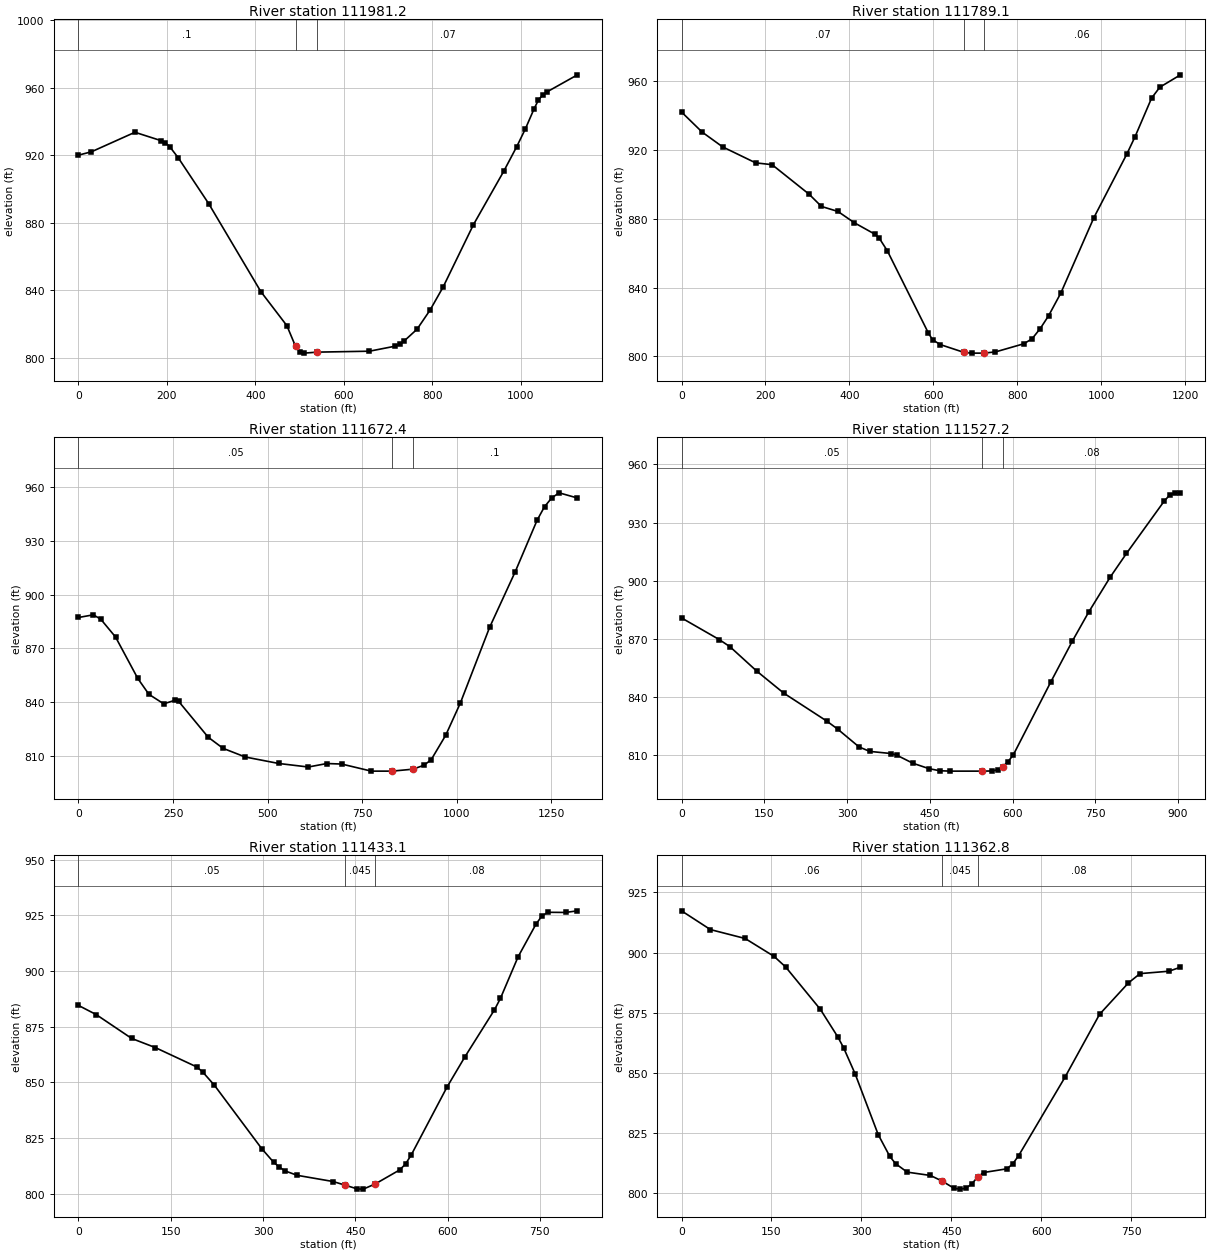
Type RM Length L Ch R = 1 ,111981.2,219.1,192.1,165
XS GIS Cut Line= 4
     1911785.084      610658.161     1912010.344      611003.213
     1912045.066      611246.268     1912437.861      611504.515
#Sta/Elev= 30
       0  920.07    29.4  922.07   127.6   933.6   186.4  928.66   196.2  927.38
     206  925.14   225.7  918.41   294.3  891.37   412.1  839.36     471  819.19
   490.6  806.94   500.5  803.61   510.3  802.95   539.7  803.54   657.6  804.09
   716.4   807.1   726.2  808.13   735.9  810.09   765.3  817.13   794.7  828.45
   824.1  842.04   892.6  878.92   961.2  910.57   990.6  925.15  1010.2   935.7
  1029.8  947.54  1039.5  952.66  1049.3  955.74  1059.1  957.52  1127.7  967.58
#Mann= 3 , 0 , 0
       0      .1       0   490.6    .045       0   539.7     .07       0
Bank Sta=490.6,539.7
XS Rating Curve= 0 ,0
Exp/Cntr=0.3,0.1

Type RM Length L Ch R = 1 ,111789.1,130.1,116.7,101.2
XS GIS Cut Line= 4
     1911386.646      610921.182     1911881.438      611257.119
     1912050.709      611311.807     1912412.688      611509.723
#Sta/Elev= 30
       0   942.2      49  930.54      98  921.89   176.5   912.6   215.7  911.54
   303.9  894.34   333.3  887.22   372.6   884.3   411.8   877.7   460.8  871.03
   470.6  868.89   490.2  861.41   588.2  813.43   598.1  809.54   616.8  806.74
     673  802.21   691.7   801.8   719.8   801.8   747.9  802.51   815.2  807.24
   834.9  810.12   854.5  816.11   874.2  823.48   903.6  836.83   982.2  880.67
  1060.8  917.76  1080.4  927.88  1119.7   950.3  1139.4  956.67  1188.5  963.86
#Mann= 3 , 0 , 0
       0     .07       0     673    .045       0   719.8     .06       0
Bank Sta=673,719.8
XS Rating Curve= 0 ,0
Exp/Cntr=0.3,0.1

Type RM Length L Ch R = 1 ,111672.4,137.6,145.2,154.6
XS GIS Cut Line= 4
     1911172.236      611421.182     1911946.542       611403.82
     1912057.653      611360.418     1912425.709      611574.827
#Sta/Elev= 30
       0  887.22    39.2   888.7    58.8   886.3      98  876.37   156.9  853.31
   186.3   844.5   225.5  839.21   254.9  841.19   264.7  840.64   343.1  820.65
   382.4  814.47   441.2  809.65   529.4  806.06   607.8  804.09   656.8  806.02
   696.1  805.74   774.5   801.8   829.6   801.8   884.6  802.88   913.2  805.03
   932.5  808.02   971.2  821.71    1010  839.66  1087.4  881.74  1155.2  912.68
  1213.2  941.39  1232.6  948.81    1252  953.77  1271.3  956.53  1319.7  953.65
#Mann= 3 , 0 , 0
       0     .05       0   829.6    .045       0   884.6      .1       0
Bank Sta=829.6,884.6
XS Rating Curve= 0 ,0
Exp/Cntr=0.3,0.1

Type RM Length L Ch R = 1 ,111527.2,89.7,94.1,99.4
XS GIS Cut Line= 4
     1911502.097      611516.668     1911979.528      611499.307
     1912121.889      611507.987     1912394.459      611587.848
#Sta/Elev= 30
       0  880.83    68.2  869.69    87.8  865.98   136.5  853.36   185.2  842.05
   263.2  827.63   282.8  823.53   321.8  814.28   341.2  811.98   380.2  810.86
     390  810.05   419.2  805.89   448.5  803.08     468     802   487.2   801.8
   544.3   801.8   563.3  801.88   572.8  802.52   582.3  804.16   591.8  806.67
   601.4  810.19   669.3  847.77   708.5   868.9   737.9  883.77   777.1  901.89
   806.5  914.08     875  941.11   884.8  944.17   894.6  945.35   904.4  945.34
#Mann= 3 , 0 , 0
       0     .05       0   544.3    .045       0   582.3     .08       0
Bank Sta=544.3,582.3
XS Rating Curve= 0 ,0
Exp/Cntr=0.3,0.1

Type RM Length L Ch R = 1 ,111433.1,69.4,70.3,69.6
XS GIS Cut Line= 4
        1911608.      611556.598     1911991.681      611577.432
     1912125.361      611610.418     1912413.556      611632.987
#Sta/Elev= 30
       0  884.57    28.8  880.46    86.5  869.72   124.9  865.62   192.1  856.94
   201.7  854.71   220.9   848.7   297.8   820.2     317  814.12   326.6  811.85
   336.2  810.14   355.4   808.2   413.8  805.41   433.4  803.77   453.1  802.09
   462.9  801.99   482.6  804.36   521.9   810.6   531.6  813.27   541.2  817.53
     599  847.87   627.9  861.37   676.1  882.58   685.8  887.72   714.6  906.47
   743.6   921.1   753.2  924.77   762.8  926.44   791.7  926.37     811   927.1
#Mann= 3 , 0 , 0
       0     .05       0   433.4    .045       0   482.6     .08       0
Bank Sta=433.4,482.6
XS Rating Curve= 0 ,0
Exp/Cntr=0.3,0.1

Type RM Length L Ch R = 1 ,111362.8,59.9,54.9,50.3
XS GIS Cut Line= 4
     1911618.417      611624.307     1912022.931      611648.612
     1912156.611      611681.598     1912444.806      611704.168
#Sta/Elev= 30
       0  917.33    48.2  909.54   106.1  905.84   154.4   898.4   173.7     894
   231.6  876.39   260.5  865.02   270.2  860.51   289.5  849.64     328   824.4
   347.4  815.32     357  812.34   376.3  808.83   415.1  807.44   434.8  805.08
   454.4  802.12   464.2  801.77   474.1   802.1   483.9  803.91   493.8   806.8
   503.6  808.66   542.9  810.22   552.6  812.35   562.2   815.7   639.3  848.18
   697.1  874.36   745.3  887.42   764.6  891.26   812.7  892.25     832  893.92
#Mann= 3 , 0 , 0
       0     .06       0   434.8    .045       0   493.8     .08       0
Bank Sta=434.8,493.8
XS Rating Curve= 0 ,0
Exp/Cntr=0.3,0.1

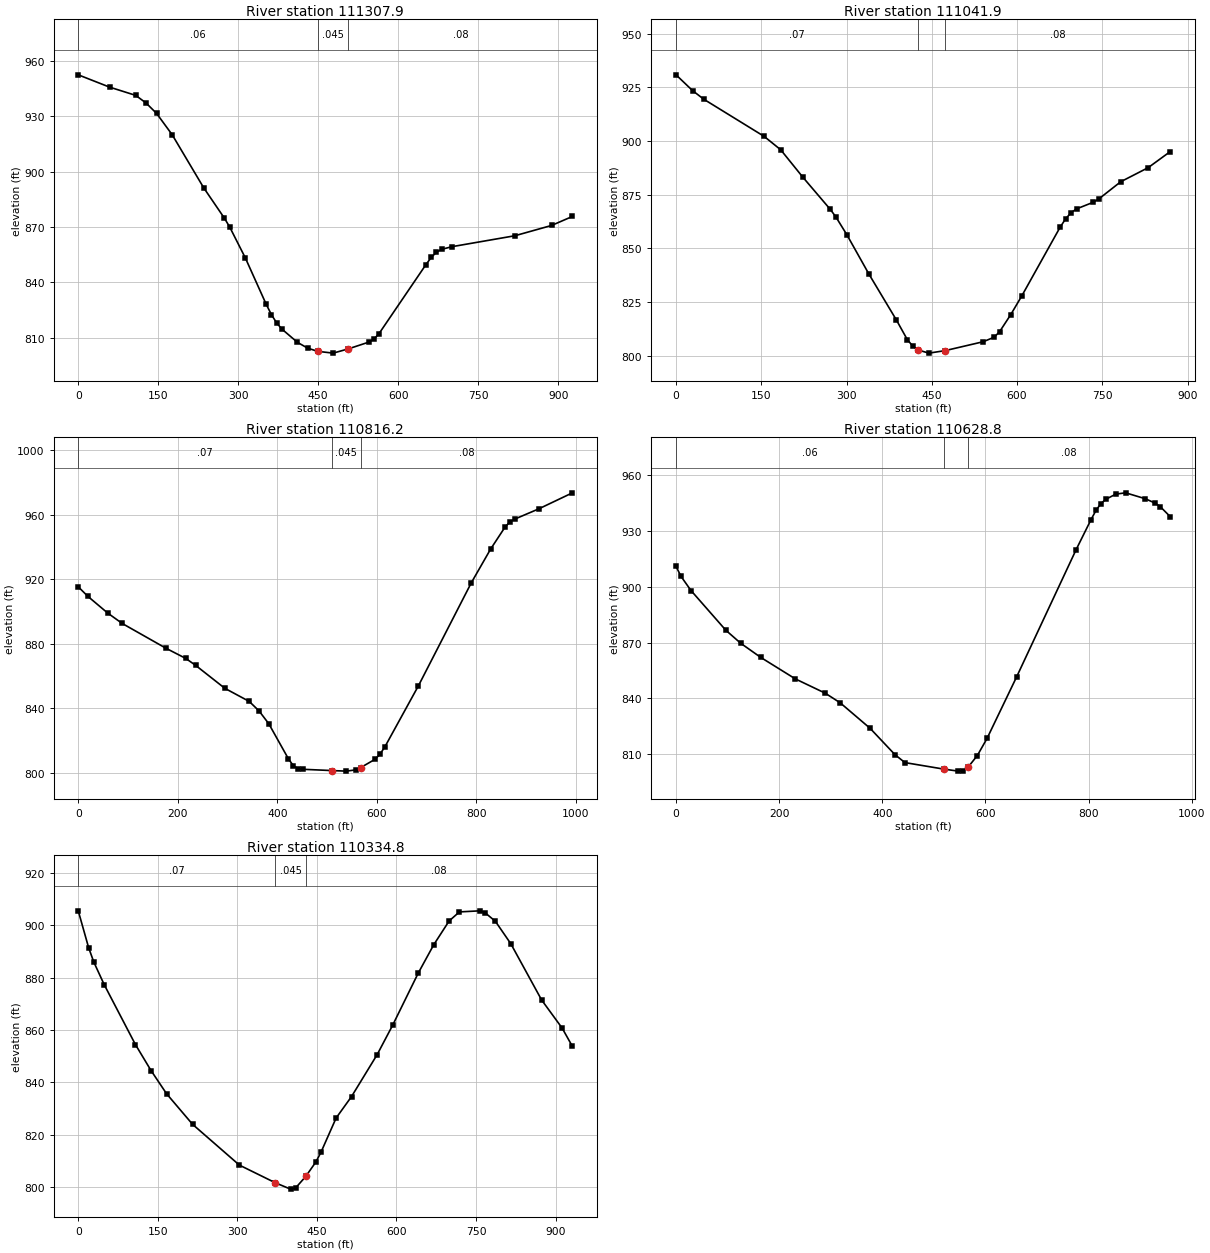
Type RM Length L Ch R = 1 ,111307.9,269.3,266,262.7
XS GIS Cut Line= 4
     1911625.361      611697.223     1912026.403      611714.584
     1912198.278      611725.001     1912547.236       611778.82
#Sta/Elev= 30
       0  952.49    58.7  945.83   107.7  941.36   127.3  937.19   146.9  931.57
   176.2     920     235  891.38   274.1  874.78   283.9  870.06   313.3  853.28
   352.5  828.09   362.2  822.56     372  818.04   381.8  814.71     411  807.51
   430.1  804.37   449.2  802.62     478  801.66   506.6  803.98   544.9  807.63
   554.5  809.24     564  812.23   652.1  849.68   661.9  853.52   671.7  856.37
   681.5  857.92   701.1  859.37   818.8  865.28   887.5  870.85   926.7  875.74
#Mann= 3 , 0 , 0
       0     .06       0   449.2    .045       0   506.6     .08       0
Bank Sta=449.2,506.6
XS Rating Curve= 0 ,0
Exp/Cntr=0.3,0.1

Type RM Length L Ch R = 1 ,111041.9,210.3,225.7,241.2
XS GIS Cut Line= 4
     1911750.361      611836.112     1912109.736      611981.945
     1912252.097      611969.793     1912590.639      611981.945
#Sta/Elev= 30
       0  930.78    29.1  923.44    48.5  919.48   155.1  902.12   184.2   895.9
     223  883.19   271.5  868.14   281.2  864.68   300.6  856.36   339.4  838.06
   387.8  816.67   406.9  807.59   416.4  804.58   425.9  802.73     445  801.29
   473.6  802.46   540.4  806.59   559.8   808.7   569.4  811.31   588.8  819.15
   608.2  827.84   675.9  859.93   685.6  863.83   695.3   866.7   704.9  868.42
     734  871.48   743.6  872.97   782.4  881.03   830.8   887.6   869.5  895.06
#Mann= 3 , 0 , 0
       0     .07       0   425.9    .045       0   473.6     .08       0
Bank Sta=425.9,473.6
XS Rating Curve= 0 ,0
Exp/Cntr=0.3,0.1

Type RM Length L Ch R = 1 ,110816.2,175.4,187.4,199.2
XS GIS Cut Line= 4
     1911748.625       611863.89     1912090.639      612127.779
     1912250.361      612237.154     1912557.653      612438.543
#Sta/Elev= 30
       0  915.23    19.6  909.24    58.9  899.03    88.4  892.49   176.7  877.06
     216  870.83   235.6  866.59   294.5   852.3   343.6  844.16   363.3  838.27
   382.9  830.31   422.2  808.63     432  804.36   441.7   802.5   451.3  802.08
   509.4  801.29   538.5  800.94   557.8  801.71   567.5  803.13   596.5   808.3
   606.2  811.42   615.9  815.86   683.6  853.89   789.9  917.79   828.6  938.63
   857.6  952.27   867.3  955.45     877  957.21   925.3  963.56     993  973.51
#Mann= 3 , 0 , 0
       0     .07       0   509.4    .045       0   567.5     .08       0
Bank Sta=509.4,567.5
XS Rating Curve= 0 ,0
Exp/Cntr=0.3,0.1

Type RM Length L Ch R = 1 ,110628.8,284.2,294,304.3
XS GIS Cut Line= 4
      1911701.75      611874.307     1912015.631      612253.371
     1912059.389      612344.793     1912219.111      612672.918
#Sta/Elev= 30
       0  910.87     9.6  905.52      29  897.91    96.5   876.6   125.4   869.6
     164  862.05   231.6  850.43   289.5  842.77   318.4  837.61   376.4  823.92
   424.6  809.78   443.9  805.52   519.8     802   547.4  800.94   556.6  801.21
   565.9   802.9   584.3   809.3   603.1  818.46   660.7  851.64     776   919.9
   804.8  935.96   814.4   940.9     824   944.6   833.6  946.88   852.8  949.67
     872  950.36   910.4  947.16   929.6  944.76   939.2  942.91   958.4  937.58
#Mann= 3 , 0 , 0
       0     .06       0   519.8    .045       0   565.9     .08       0
Bank Sta=519.8,565.9
XS Rating Curve= 0 ,0
Exp/Cntr=0.3,0.1

Type RM Length L Ch R = 1 ,110334.8,410.2,398.3,384.8
XS GIS Cut Line= 4
     1911631.611      611887.761     1911757.479      612206.772
     1911753.139      612350.001     1911989.684      612727.605
#Sta/Elev= 30
       0  905.42    19.6  891.36    29.4  885.87      49  877.26   107.8  854.46
   137.2  844.56   166.6  835.69   215.6  824.04   303.8  808.51   371.6  801.77
   400.3  799.35   409.8   799.8   428.9  804.17     448  809.69   457.6  813.38
   486.2  826.45   515.3  834.64   563.7  850.66   592.8  861.82   641.2  881.75
   670.3   892.5   699.3  901.57   718.7  905.02   757.5  905.43   767.2  904.68
   786.5  901.44   815.6  892.89   873.7  871.45   912.4  860.73   931.8  853.74
#Mann= 3 , 0 , 0
       0     .07       0   371.6    .045       0   428.9     .08       0
Bank Sta=371.6,428.9
XS Rating Curve= 0 ,0
Exp/Cntr=0.3,0.1