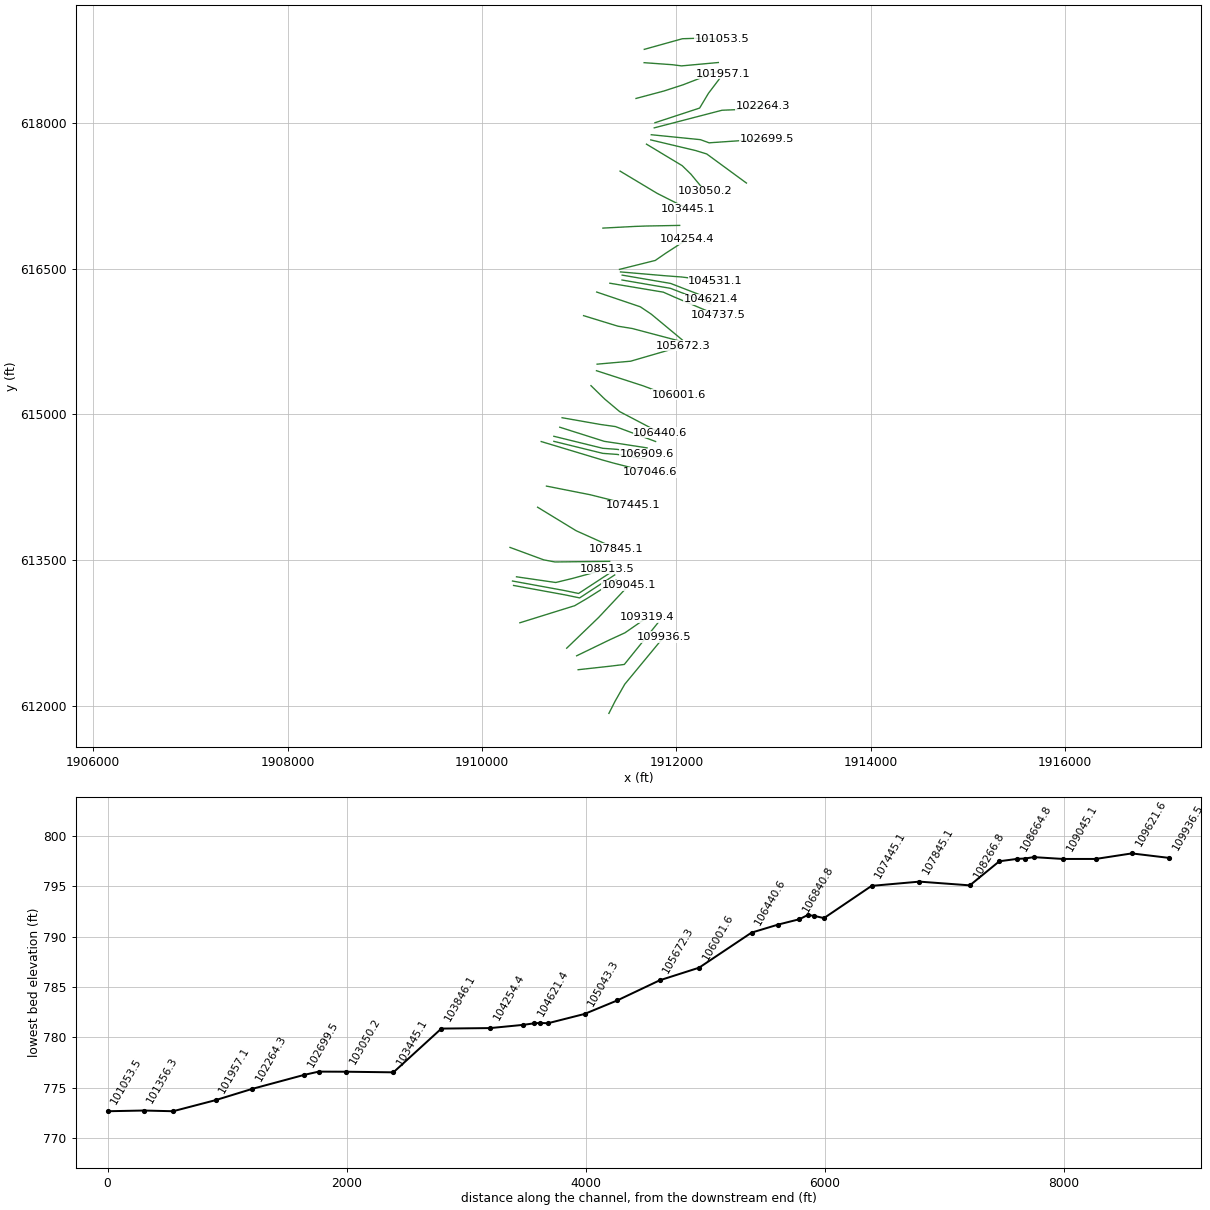
HEC-RAS study HenryFork.prj: HenryFork

--- HenryFork.g01 (geometry) --- (continued)

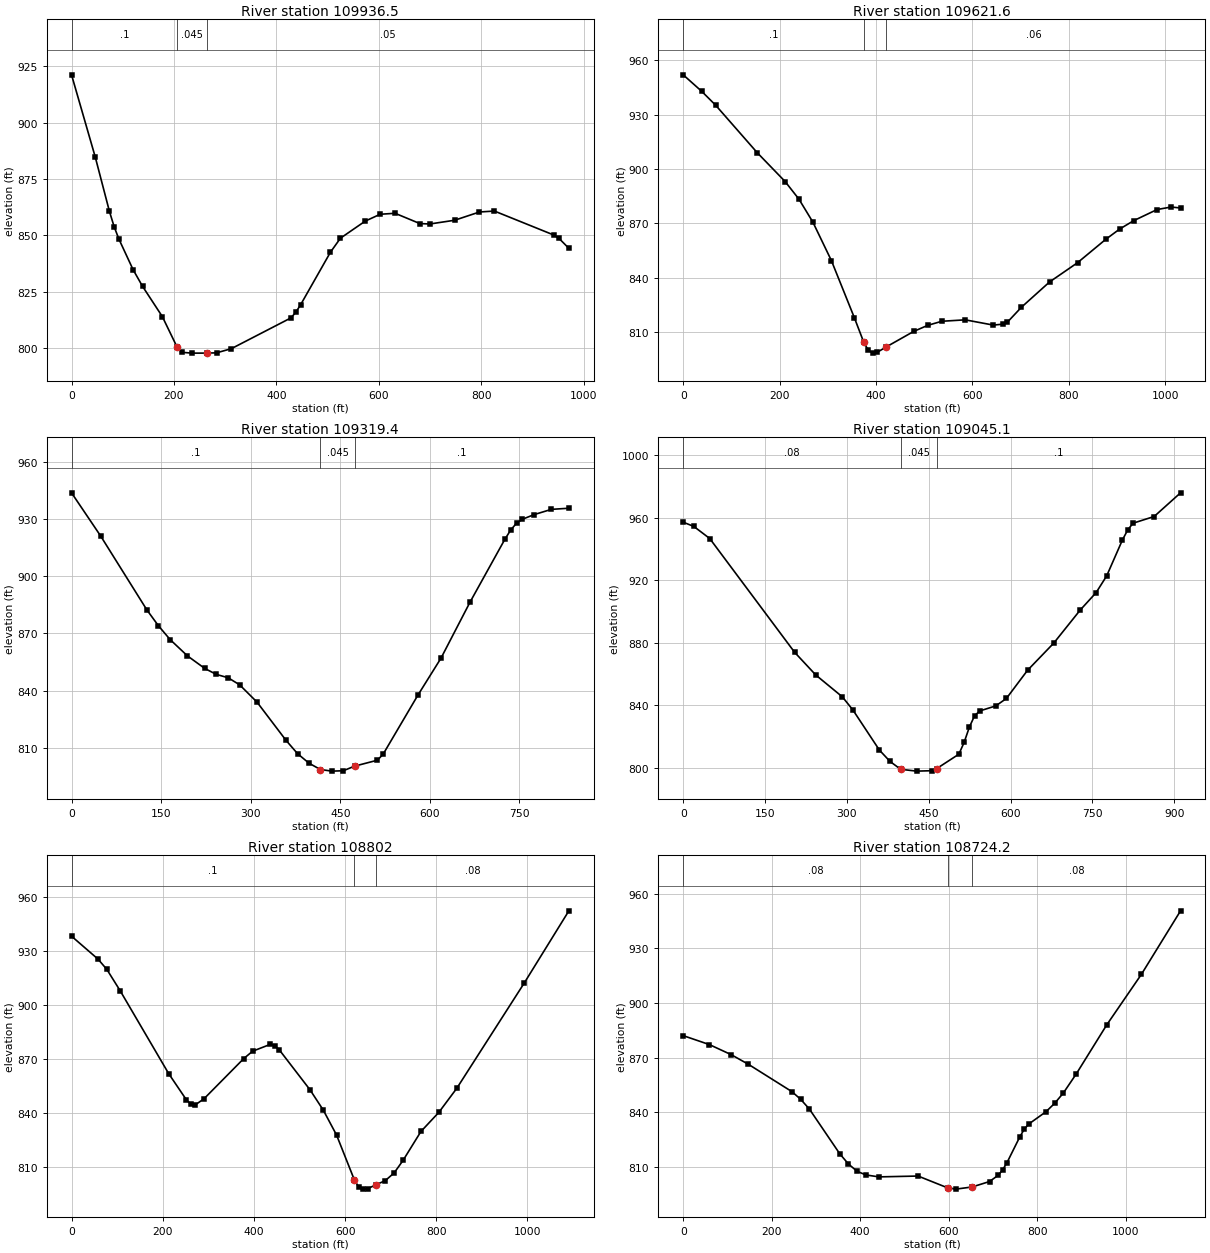
Type RM Length L Ch R = 1 ,109936.5,336.3,314.9,294.4
XS GIS Cut Line= 4
      1911306.09      611922.484     1911369.025      612046.182
     1911468.851      612221.963     1911870.327      612708.074
#Sta/Elev= 30
       0  921.28    46.3  884.83      74  860.71    83.3  853.84    92.5  848.41
   120.3   834.8   138.8   827.4   177.3  814.03   206.2  800.45   215.8  798.16
     235   797.8   263.9  797.81   283.2  797.93   312.1  799.77   428.2  813.39
   437.9  815.87   447.6  819.33   505.8  842.61   525.2  848.79   573.7  856.38
   602.8  859.41   631.9  859.85   680.4  855.28   699.8   855.1   748.3  856.76
   796.8  860.42   825.9  860.84   942.3  850.17     952  848.73   971.4   844.3
#Mann= 3 , 0 , 0
       0      .1       0   206.2    .045       0   263.9     .05       0
Bank Sta=206.2,263.9
XS Rating Curve= 0 ,0
Exp/Cntr=0.3,0.1

Type RM Length L Ch R = 1 ,109621.6,294.8,302.2,308.5
XS GIS Cut Line= 4
      1910989.25      612371.702     1911323.452      612408.595
     1911464.511      612425.956     1911812.393      612856.489
#Sta/Elev= 30
       0  951.99    38.4  942.87    67.2  935.23   153.7  908.94   211.4  893.06
   240.2  883.28     269  870.64   307.4  849.41   355.2  817.75   374.1   804.6
   383.6  799.92   393.1  798.25   402.6  798.73   421.5  801.71   478.4  810.27
   507.5  813.61   536.6  815.85   585.2  816.64   643.4  813.74   662.9  814.24
   672.6  815.34   701.7  823.59     760  837.54   818.2  848.21   876.5  861.07
   905.6   866.8   934.8  871.44   983.3  877.58  1012.4  878.96  1031.9  878.43
#Mann= 3 , 0 , 0
       0      .1       0   374.1    .045       0   421.5     .06       0
Bank Sta=374.1,421.5
XS Rating Curve= 0 ,0
Exp/Cntr=0.3,0.1

Type RM Length L Ch R = 1 ,109319.4,266.6,274.3,283.1
XS GIS Cut Line= 4
     1910974.059      612514.932     1911314.771      612679.862
     1911471.021      612751.477     1911703.226      612912.067
#Sta/Elev= 30
       0  943.75    48.5  921.22   126.2  882.28   145.6  873.94     165  866.76
   194.1  858.17   223.2  851.56   242.6  848.44   262.1  846.72   281.5  842.98
   310.6   833.9   359.1  813.86   378.5  806.84   397.6  801.87   416.7  798.54
   435.8   797.7   454.9  797.89     474  800.32   512.2  803.44   521.8  806.63
   579.6  837.41   618.6  856.99   667.2  886.38   725.6   919.4   735.4  924.28
   745.1  927.82   754.9  929.88   774.3   932.3   803.5  935.08   832.7  935.66
#Mann= 3 , 0 , 0
       0      .1       0   416.7    .045       0     474      .1       0
Bank Sta=416.7,474
XS Rating Curve= 0 ,0
Exp/Cntr=0.3,0.1

Type RM Length L Ch R = 1 ,109045.1,248.5,243.1,236.4
XS GIS Cut Line= 3
     1910871.748      612593.224     1911200.853      612910.066
     1911511.987      613241.617
#Sta/Elev= 30
       0  957.04    19.4  954.34    48.6   946.6   204.1   873.8     243  859.22
   291.6  845.27     311  836.85   359.6  811.15   379.1  803.89   398.5  798.88
   427.7   797.7   456.8  797.98   464.3  799.25   505.2  808.54   514.9  816.14
   524.6  826.01   534.2  833.27   543.9  836.28   572.9  839.45   592.3  844.21
     631  862.21   679.3  879.72   727.7  900.85   756.7  911.94   776.1  922.66
   805.1  945.78   814.8  952.15   824.4   956.4   863.1  960.68   911.5  975.84
#Mann= 3 , 0 , 0
       0     .08       0   398.5    .045       0   464.3      .1       0
Bank Sta=398.5,464.3
XS Rating Curve= 0 ,0
Exp/Cntr=0.3,0.1

Type RM Length L Ch R = 1 ,108802  ,103,77.8,48.5
XS GIS Cut Line= 4
     1910389.858      612854.775     1910954.094      613030.557
     1911079.962      613104.341     1911379.441      613293.143
#Sta/Elev= 30
       0  938.08    58.1  925.37    77.5  919.65   106.6  907.87   213.1   861.9
   251.9   847.4   261.6  844.99   271.3  844.57   290.6  847.96   377.8  870.26
   397.2  874.33     436  878.12   445.7  877.48   455.4  875.19   523.2   852.9
   552.2  841.68   581.3  827.88   620.2  803.11   629.9  799.01   639.6  797.88
   649.3   798.1   668.7  800.41   688.2  802.59   707.7  806.89   727.2  813.81
   766.4  829.83   805.7  840.44   845.1  853.79   992.6  911.96  1090.9  952.14
#Mann= 3 , 0 , 0
       0      .1       0   620.2    .045       0   668.7     .08       0
Bank Sta=620.2,668.7
XS Rating Curve= 0 ,0
Exp/Cntr=0.3,0.1

Type RM Length L Ch R = 1 ,108724.2,53.2,59.5,69.8
XS GIS Cut Line= 4
     1910324.754       613238.89     1910856.438      613141.668
     1911004.875      613110.852     1911365.994      613347.158
#Sta/Elev= 30
       0  882.07      59  877.17   108.1  871.66   147.4  866.31   245.7  851.29
   265.3  847.11     285  841.77   353.8  817.13   373.4  811.52   393.1  807.51
   412.8  805.53   442.2  804.47   530.7  804.93   597.4  798.45   616.3  797.74
   652.7  798.93   692.1  801.91   711.7  805.36   721.5  808.27   731.3  812.16
   760.8   826.6   770.6  830.67   780.4  833.44   819.6  840.26   839.2  844.88
   858.8  850.52   888.3  861.13   956.9  887.98  1035.4  915.81  1123.7  950.65
#Mann= 3 , 0 , 0
       0     .08       0   597.4    .045       0   652.7     .08       0
Bank Sta=597.4,652.7
XS Rating Curve= 0 ,0
Exp/Cntr=0.3,0.1

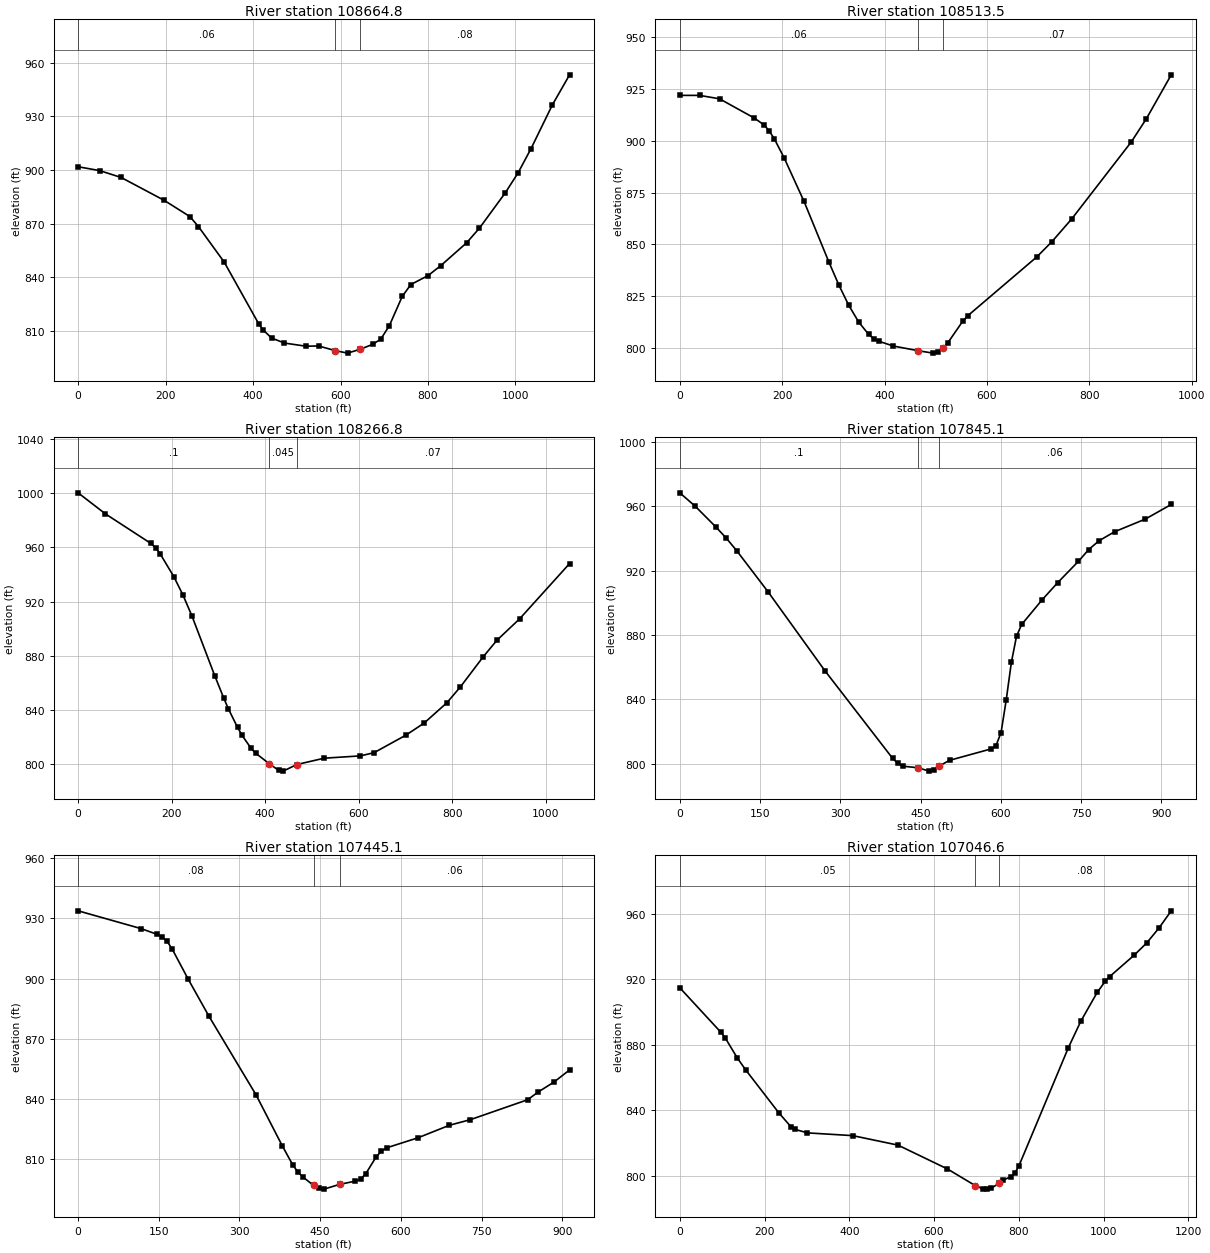
Type RM Length L Ch R = 1 ,108664.8,139.5,151.3,162.3
XS GIS Cut Line= 4
     1910313.903      613284.463     1910845.587      613187.241
     1910994.025      613156.425     1911355.143      613392.731
#Sta/Elev= 30
       0  901.84    49.1   899.7    98.3  895.86   196.6   883.1   255.5  874.02
   275.2  868.39   334.1  848.54   412.8  814.14   422.6  810.76   442.2  806.16
   471.7  803.34   520.8  801.58     550  801.71   587.9   799.1   616.3  797.71
   644.7  799.86   673.2  802.57   692.1  805.54   711.7  813.08   741.1  829.41
   760.8  836.04     800  841.01   829.4  846.63   888.3  859.35   917.7  867.57
   976.5   887.2    1006  898.44  1035.4  911.89  1084.4  936.42  1123.7   953.2
#Mann= 3 , 0 , 0
       0     .06       0   587.9    .045       0   644.7     .08       0
Bank Sta=587.9,644.7
XS Rating Curve= 0 ,0
Exp/Cntr=0.3,0.1

Type RM Length L Ch R = 1 ,108513.5,255.8,246.7,238.2
XS GIS Cut Line= 4
     1910355.136      613327.866     1910758.781      613269.272
     1910936.733      613312.675     1911292.636      613410.331
#Sta/Elev= 30
       0  921.91    38.8   921.9    77.7  920.25   145.7  910.95   165.1  907.54
   174.8  904.72   184.5  901.01   203.9  891.74   242.8  870.69   291.3  841.45
   310.8  830.33   330.2  820.51   349.6  812.46     369   806.5   378.7  804.52
   388.4  803.24   417.5  800.88   465.7  798.64   494.6  797.47   504.3   798.1
   513.9  799.72   523.6  802.44   552.5  812.77   562.1   815.4   697.9  844.02
     727  851.28   765.9  862.32   882.4  899.56   911.5  910.62   960.1  931.83
#Mann= 3 , 0 , 0
       0     .06       0   465.7    .045       0   513.9     .07       0
Bank Sta=465.7,513.9
XS Rating Curve= 0 ,0
Exp/Cntr=0.3,0.1

Type RM Length L Ch R = 1 ,108266.8,429.9,421.7,416.6
XS GIS Cut Line= 4
     1910288.295      613630.383     1910635.518      613502.345
     1910750.535      613480.643     1911314.284      613486.983
#Sta/Elev= 30
       0 1000.22    58.4  984.71   155.8  962.87   165.6  959.74   175.3  955.34
   204.5  938.52     224  925.04   243.5  909.37   292.2  865.37   311.6  848.77
   321.4  840.94   340.9  827.33   350.6  821.42   370.1  811.78   379.8  808.25
   409.1  800.45   428.6  795.71   438.4  795.08   467.6  799.93     526  804.61
   603.8  806.32   632.9  808.69     701  821.62   739.8  830.47   788.5  845.46
   817.6  857.24   866.2  879.34   895.4  891.49     944   907.3  1050.9  948.08
#Mann= 3 , 0 , 0
       0      .1       0   409.1    .045       0   467.6     .07       0
Bank Sta=409.1,467.6
XS Rating Curve= 0 ,0
Exp/Cntr=0.3,0.1

Type RM Length L Ch R = 1 ,107845.1,392,400,403.9
XS GIS Cut Line= 3
     1910572.517      614043.886     1910970.015      613801.431
     1911383.644        613616.4
#Sta/Elev= 30
       0   968.3    29.1   959.9    67.9  946.95    87.3  940.02   106.7  932.23
   164.9  906.88   271.6  857.67   397.7  803.46   407.4  800.24   417.1  798.52
   446.2  797.51   465.6  795.45   475.2  796.36   484.9  798.61   504.2  802.15
   581.3  809.19   590.9  811.09   600.6  819.44   610.2  839.58   619.9  863.13
   629.5  879.24   639.1  886.54   677.7  901.98   706.6  912.56   745.2  925.76
   764.5  933.09   783.8  938.54   812.7  944.11   870.5  952.03   918.7  961.07
#Mann= 3 , 0 , 0
       0      .1       0   446.2    .045       0   484.9     .06       0
Bank Sta=446.2,484.9
XS Rating Curve= 0 ,0
Exp/Cntr=0.3,0.1

Type RM Length L Ch R = 1 ,107445.1,400.1,398.5,398
XS GIS Cut Line= 3
     1910663.386      614261.404     1911111.934      614172.766
     1911554.797      614062.224
#Sta/Elev= 30
       0  933.78   116.7  924.94   145.9  922.16   155.6  920.83   165.4   918.6
   175.1  914.61   204.3  899.88   243.2  881.25   330.8  842.03   379.4  816.71
   398.8  807.23   408.6  803.53   418.3  800.99   437.8  796.88   447.5  795.41
   457.2  795.03   486.4  797.42   515.5  799.02   525.2  799.97   534.9  802.76
   554.3  811.19     564  813.99   573.8  815.64     632  820.64   690.3  826.87
   729.2  829.66     836  839.62   855.4  843.48   884.5  848.36   913.7  854.46
#Mann= 3 , 0 , 0
       0     .08       0   437.8    .045       0   486.4     .06       0
Bank Sta=437.8,486.4
XS Rating Curve= 0 ,0
Exp/Cntr=0.3,0.1

Type RM Length L Ch R = 1 ,107046.6,80.5,84.8,89.2
XS GIS Cut Line= 4
     1910609.476      614719.793     1911242.174      614529.321
     1911348.944      614499.527     1911724.927      614402.952
#Sta/Elev= 30
       0  914.87    97.2  887.62   106.9  884.38     136  871.88   155.5   864.7
   233.2  838.62   262.4  829.91   272.1  828.33   301.2   826.2   408.1  824.52
     515  818.72   631.6  804.16   697.7  793.92   716.2  791.91   725.4  791.83
   734.6  792.25   753.1  795.39   762.4  797.22   781.3  799.44     791  801.69
   800.7  806.26   917.2  878.35   946.3  894.37   985.1  912.04  1004.5  919.02
  1014.2  921.64  1072.4   934.8  1101.6  942.16  1130.7  951.32  1159.8  961.88
#Mann= 3 , 0 , 0
       0     .05       0   697.7    .045       0   753.1     .08       0
Bank Sta=697.7,753.1
XS Rating Curve= 0 ,0
Exp/Cntr=0.3,0.1

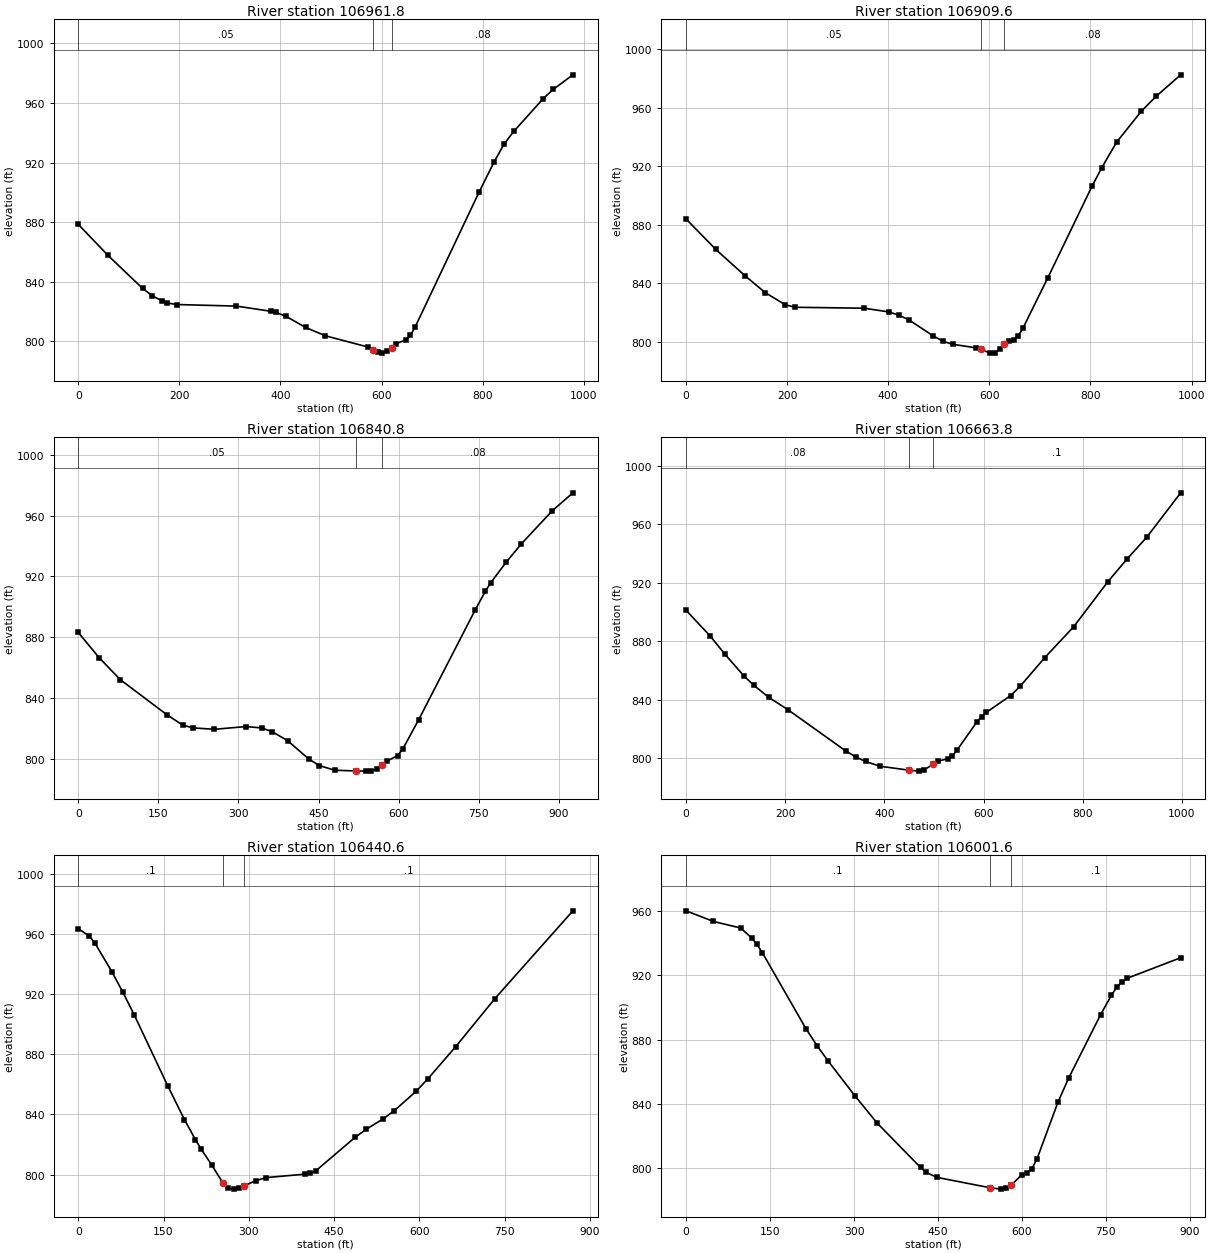
Type RM Length L Ch R = 1 ,106961.8,52.1,52.2,52
XS GIS Cut Line= 4
     1910739.684      614721.963     1911243.156      614598.265
     1911390.726      614587.414     1911698.886      614537.501
#Sta/Elev= 30
       0  878.52    58.7   857.7   127.2  835.53   146.7   830.5   166.3  826.99
   176.1  825.71   195.6  824.67     313  823.64   381.5  820.13   391.3  819.34
   410.8   816.8     450  809.27   489.1  803.68   573.9  796.09   583.2  794.49
   592.4  792.71   601.7  792.06   610.9  793.17   620.2  795.79   629.4  798.49
   647.9   800.9   657.2  803.97   666.4  809.53   793.2   900.3   822.5  920.24
     842  932.16   861.5  940.85   920.1  962.98   939.6   969.1   978.6  978.89
#Mann= 3 , 0 , 0
       0     .05       0   583.2    .045       0   620.2     .08       0
Bank Sta=583.2,620.2
XS Rating Curve= 0 ,0
Exp/Cntr=0.3,0.1

Type RM Length L Ch R = 1 ,106909.6,70.7,68.8,66.3
XS GIS Cut Line= 4
     1910739.684      614774.046     1911243.156      614650.348
     1911390.726      614639.497     1911698.886      614589.584
#Sta/Elev= 30
       0  883.87    58.7  863.09   117.4  844.81   156.5  833.55   195.6  825.32
   215.2  823.49   352.2  822.85   401.1  820.32   420.6  818.17   440.2  815.02
   489.1  803.87   508.7   800.2   527.7  798.16   573.9  795.76   583.2  794.74
   601.7  792.13   610.9  792.51   620.2  794.79   629.4  798.08   638.7   800.1
   647.9  801.02   657.2  803.79   666.4  809.11   715.2  843.27     803  906.14
   822.5  918.99   851.8  936.39   900.5  957.48   929.8   967.7   978.6  982.47
#Mann= 3 , 0 , 0
       0     .05       0   583.2    .045       0   629.4     .08       0
Bank Sta=583.2,629.4
XS Rating Curve= 0 ,0
Exp/Cntr=0.3,0.1

Type RM Length L Ch R = 1 ,106840.8,176.2,177,177.5
XS GIS Cut Line= 4
     1910800.448      614867.362     1911258.347      614721.963
     1911403.747      614700.261     1911698.886      614654.688
#Sta/Elev= 30
       0  883.09    39.2  866.43    78.4  852.08   166.7  828.68   196.1  821.93
   215.7   820.2   254.9  819.28   313.8   821.1   343.2  820.18   362.8  817.76
   392.2  811.75   431.4  799.75     451  795.42   480.4  792.29   519.6  791.86
   539.2  791.72     549  791.95   558.8  793.18   568.6  795.76   578.4  798.34
     598  802.01   607.8   806.4   637.1  825.43     743  897.81   762.3  910.28
   771.9  915.72   800.8  929.22   829.7  941.53   887.5  963.29   926.1  975.12
#Mann= 3 , 0 , 0
       0     .05       0   519.6    .045       0   568.6     .08       0
Bank Sta=519.6,568.6
XS Rating Curve= 0 ,0
Exp/Cntr=0.3,0.1

Type RM Length L Ch R = 1 ,106663.8,235.9,223.2,210.5
XS GIS Cut Line= 4
      1910824.32      614965.018     1911219.285      614895.574
     1911373.365      614873.872     1911786.531      614720.312
#Sta/Elev= 30
       0  901.15    48.9  883.46    78.2  871.18   117.4  855.98   136.9   849.8
   166.3  841.74   205.4  833.19   322.8  804.79   342.3  800.88   361.9  797.78
   391.2  794.52   449.6  791.83   469.1  791.19   478.8  791.73   498.3  795.95
     508  797.97   527.4   799.7   537.2  801.67   546.9  805.78     586  824.63
   595.8  828.46   605.6  831.38   654.6  842.88   674.2  849.39   723.1  868.72
   781.9  890.02   850.5  920.69   889.7  936.44   928.8  951.07   997.4  981.48
#Mann= 3 , 0 , 0
       0     .08       0   449.6    .045       0   498.3      .1       0
Bank Sta=449.6,498.3
XS Rating Curve= 0 ,0
Exp/Cntr=0.3,0.1

Type RM Length L Ch R = 1 ,106440.6,431.1,438.9,446.7
XS GIS Cut Line= 4
     1911121.629      615294.879     1911262.261      615157.653
     1911416.768      615027.952     1911834.604      614809.081
#Sta/Elev= 30
       0  963.43    19.6  958.37    29.5  953.67      59  934.85    78.6  921.05
    98.2   906.3   157.2  859.09   186.7   836.6   206.1  823.24   215.7  817.23
   234.9  806.33   254.1  794.63   263.7  790.81   273.3  790.39     283  791.07
   291.1  792.49   311.8  795.98     331  798.08   398.2  800.31     408  800.93
   417.9   802.6   486.7  824.73   506.3  830.09   535.8  836.96   555.4  842.37
   594.8  855.59   614.4  863.45   663.6  884.93   732.3  916.74   869.9  975.23
#Mann= 3 , 0 , 0
       0      .1       0   254.1    .045       0   291.1      .1       0
Bank Sta=254.1,291.1
XS Rating Curve= 0 ,0
Exp/Cntr=0.3,0.1

Type RM Length L Ch R = 1 ,106001.6,314.6,329.4,343.9
XS GIS Cut Line= 4
     1911178.052      615448.959     1911659.823      615292.709
     1911798.712      615240.626     1912024.406      615203.734
#Sta/Elev= 30
       0  960.18    48.7  953.59    97.4  949.48   116.9  943.44   126.6  939.28
   136.4  934.03   214.3   886.7   233.8  876.31   253.2  866.94   301.9  844.86
   340.9  828.19   418.8  800.39   428.6  797.36     448  794.24   543.6  787.72
   562.1  786.91   571.4  787.33   580.6  789.22   599.2  795.78   608.4  796.95
   617.7  799.62     627  805.85   664.3  841.06   683.4  856.06   740.6  895.61
   759.6   907.5   769.2  912.56   778.7  916.08   788.2  918.23   883.5  930.98
#Mann= 3 , 0 , 0
       0      .1       0   543.6    .045       0   580.6      .1       0
Bank Sta=543.6,580.6
XS Rating Curve= 0 ,0
Exp/Cntr=0.3,0.1

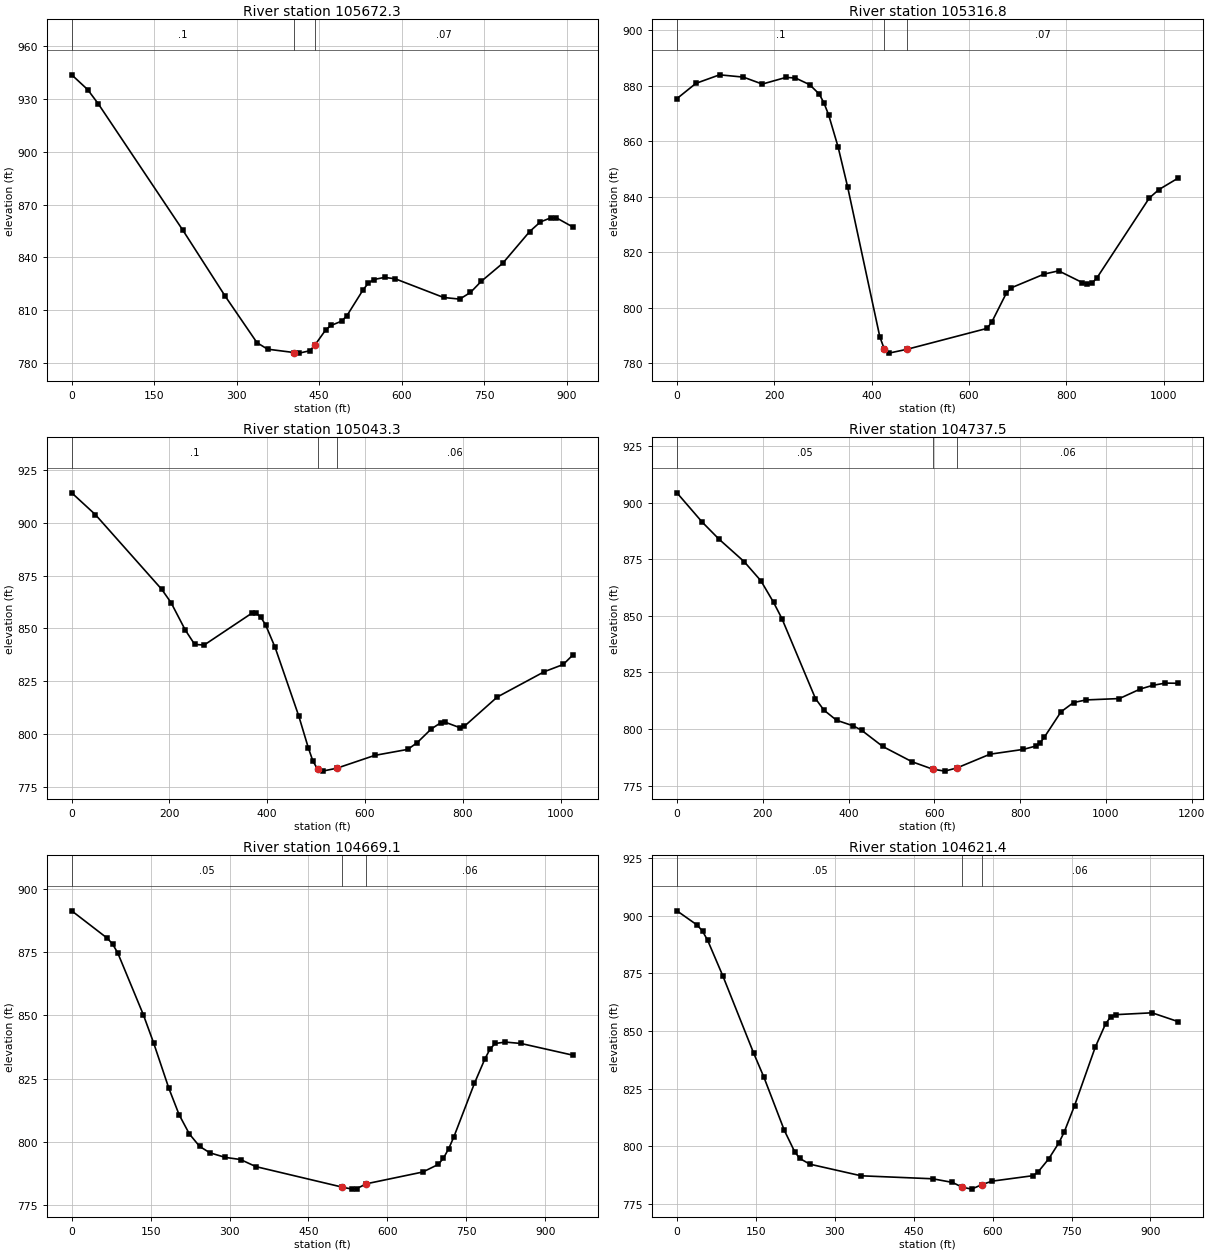
Type RM Length L Ch R = 1 ,105672.3,365.5,355.4,345.4
XS GIS Cut Line= 4
     1911184.563      615516.234     1911529.615      615546.616
     1911686.755      615592.256     1912071.596       615704.03
#Sta/Elev= 30
       0  943.59    28.9  935.24    48.1  927.23   202.1   855.4     279     818
   336.8  791.61     356  787.91   404.1     786   413.7  785.66     433  787.02
   442.6  790.43   461.9   798.9   471.5  801.35   490.8  803.83   500.4  806.93
   529.6   821.5   539.3  825.39   549.1   827.4   568.7  828.64   588.2  827.84
   676.2  817.24   705.5  816.31     725   820.1   744.6   826.4   783.7  836.67
   832.6  854.64   852.1  860.11   871.7  862.51   881.4   862.4   910.8   857.3
#Mann= 3 , 0 , 0
       0      .1       0   404.1    .045       0   442.6     .07       0
Bank Sta=404.1,442.6
XS Rating Curve= 0 ,0
Exp/Cntr=0.3,0.1

Type RM Length L Ch R = 1 ,105316.8,283.2,273.5,263.9
XS GIS Cut Line= 4
     1911045.674      616015.366     1911399.406      615906.859
     1911546.976      615882.987     1912039.597      615752.779
#Sta/Elev= 30
       0  875.34      39  880.84    87.6  883.91   136.3  883.09   175.3  880.58
     224  882.98   243.4  882.77   272.6  880.37   292.1  877.01   301.8  873.87
   311.6  869.47     331  857.95   350.5  843.62   416.7  789.57   426.1  785.04
   435.4  783.66   472.8  785.05   637.1  792.58   646.9  794.92   676.3  805.15
   686.1  807.14   754.7  812.16   784.1   813.3     833  809.05   842.8  808.43
   852.6  808.88   862.4  810.69   970.2  839.52   989.8  842.55    1029  846.66
#Mann= 3 , 0 , 0
       0      .1       0   426.1    .045       0   472.8     .07       0
Bank Sta=426.1,472.8
XS Rating Curve= 0 ,0
Exp/Cntr=0.3,0.1

Type RM Length L Ch R = 1 ,105043.3,301.9,305.9,309.6
XS GIS Cut Line= 4
     1911180.222      616258.421     1911629.441      616106.511
      1911742.28      616030.544     1912061.299        615765.8
#Sta/Elev= 30
       0  914.22    48.4  903.89   183.9  868.55   203.2  862.18   232.3   849.2
   251.6  842.36     271  842.09   367.8  857.07   377.4  857.22   387.1  855.16
   396.8  851.56   416.1  840.95   464.5  808.43   483.9  793.45   493.6  786.96
   503.4  783.15   513.1  782.32   542.2  783.69   619.9  789.78   687.4  792.62
   706.6  795.78   735.6  802.32   754.8  805.22   764.5  805.46   793.4  802.97
   803.1  803.54   870.5  817.44     967  829.47  1005.5  832.86  1024.8  837.28
#Mann= 3 , 0 , 0
       0      .1       0   503.4    .045       0   542.2     .06       0
Bank Sta=503.4,542.2
XS Rating Curve= 0 ,0
Exp/Cntr=0.3,0.1

Type RM Length L Ch R = 1 ,104737.5,67.5,68.4,69.4
XS GIS Cut Line= 4
     1911316.073      616349.133      1911866.42      616257.119
     1911987.948        616203.3     1912427.184      616017.536
#Sta/Elev= 30
       0  904.34    58.7  891.44    97.9   883.9   156.6  873.96   195.8  865.46
   225.2  855.96   244.7  848.79     323  813.43   342.6  808.35     372  803.89
   411.2  801.38   430.7  799.42   479.7   792.3   548.2  785.53     596  782.28
   624.4   781.4   652.9  782.82   729.8  788.88   807.7  791.01   836.9   792.5
   846.6  793.93   856.4  796.36   895.3   807.6   924.5  811.69   953.7  812.85
  1031.5  813.46  1080.2  817.68  1109.4   819.3  1138.6  820.29  1167.8  820.21
#Mann= 3 , 0 , 0
       0     .05       0     596    .045       0   652.9     .06       0
Bank Sta=596,652.9
XS Rating Curve= 0 ,0
Exp/Cntr=0.3,0.1

Type RM Length L Ch R = 1 ,104669.1,47.7,47.7,47.7
XS GIS Cut Line= 4
     1911441.073      616382.119     1911939.337      616296.616
     1911998.626      616273.674     1912355.791      616135.471
#Sta/Elev= 30
       0  891.32      68  880.44    77.8  878.16    87.5   874.7   136.1  850.32
   155.6  839.21   184.7   821.2   204.2  810.78   223.6  803.22     243  798.32
   262.5  795.78   291.7  793.97   320.8  793.12     350  790.32   514.6   782.2
   532.8  781.43   541.8  781.64     560  783.54   667.3  788.19   696.8  791.19
   706.6  793.69   716.4  797.36   726.2     802   765.5  823.25   785.2  832.81
     795  836.71   804.8  838.94   824.4  839.49   853.9  838.94   952.1  834.34
#Mann= 3 , 0 , 0
       0     .05       0   514.6    .045       0     560     .06       0
Bank Sta=514.6,560
XS Rating Curve= 0 ,0
Exp/Cntr=0.3,0.1

Type RM Length L Ch R = 1 ,104621.4,83.6,90.3,97
XS GIS Cut Line= 4
     1911442.809      616432.466     1911941.073      616346.963
     1912000.363      616324.021     1912357.527      616185.819
#Sta/Elev= 30
       0  902.18    38.9  895.93    48.6  893.36    58.3  889.41    87.5  873.78
   145.8  840.42   165.3  829.96   204.2  806.84   223.6   797.7   233.3   794.7
   252.8  792.21     350  787.18   486.1  785.88   523.7   784.3   541.9  782.26
     560  781.39   578.9  783.28   598.6  784.84   677.1  787.24     687  789.02
   706.6  794.52   726.2  801.59   736.1  806.21   755.7  817.62     795  842.97
   814.6   853.1   824.4  856.21   834.2  857.12     903  857.92   952.1  854.13
#Mann= 3 , 0 , 0
       0     .05       0   541.9    .045       0   578.9     .06       0
Bank Sta=541.9,578.9
XS Rating Curve= 0 ,0
Exp/Cntr=0.3,0.1

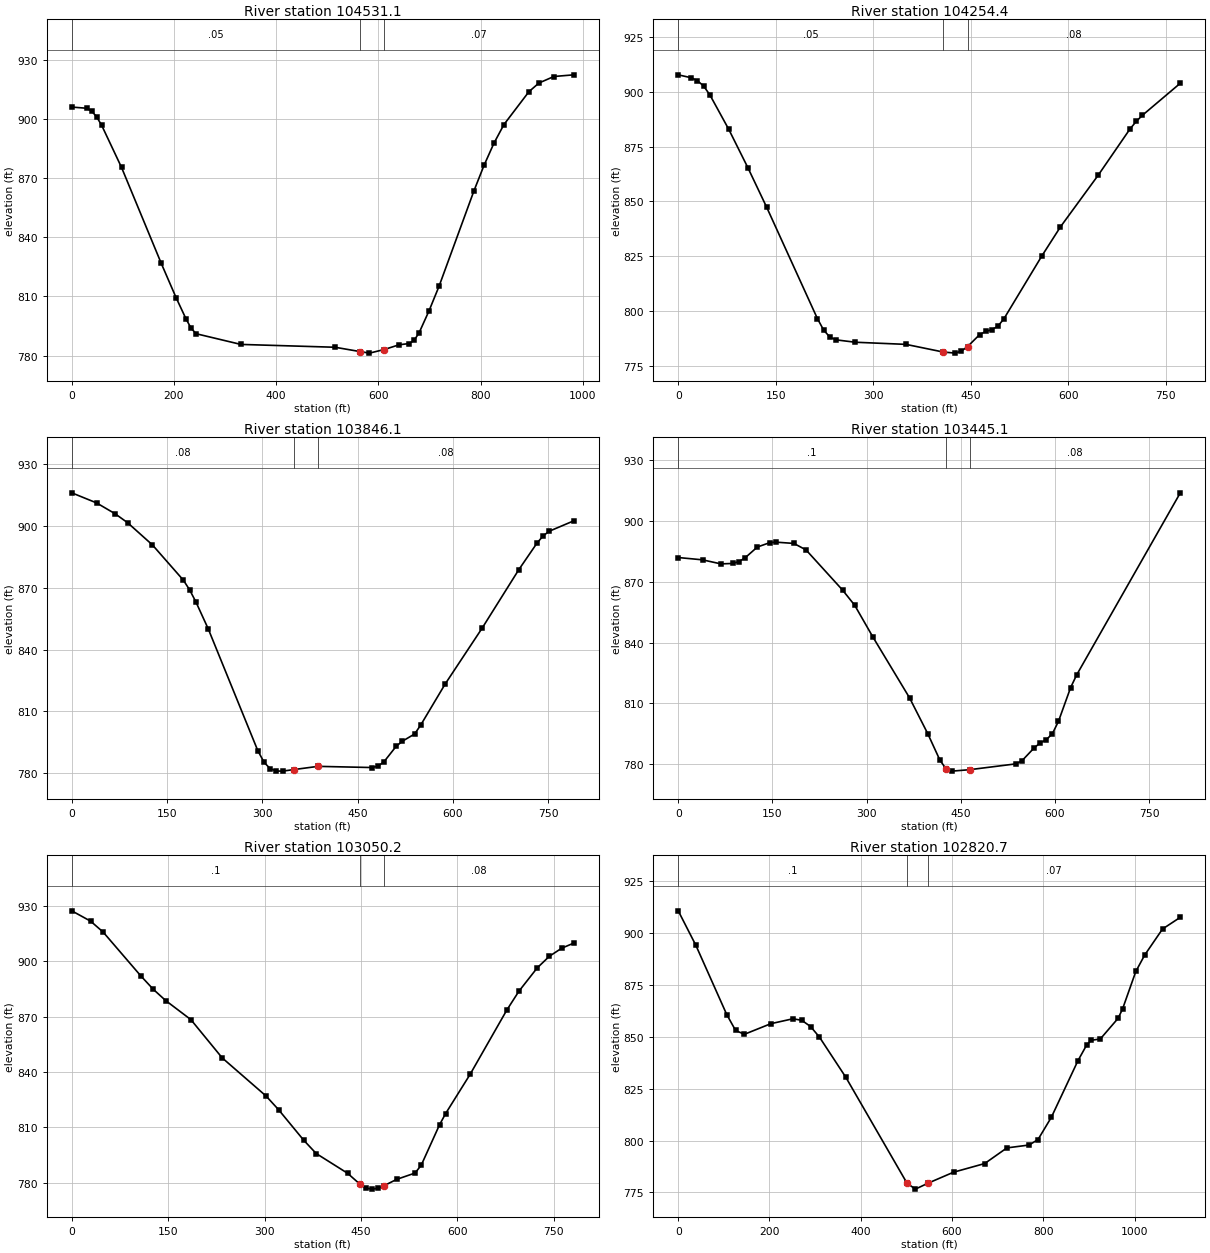
Type RM Length L Ch R = 1 ,104531.1,261.3,276.7,291.9
XS GIS Cut Line= 4
     1911425.448      616465.452     1911890.726      616425.522
      1912053.92      616413.369     1912402.879      616369.966
#Sta/Elev= 30
       0  906.09    29.2  905.49    38.9  904.06    48.6  901.14    58.4  896.88
    97.3   875.5   175.1  826.76   204.3  809.27   223.8  798.45   233.5  793.88
   243.2  791.09   330.8  785.66   515.1  784.22   563.2  782.06   582.5  781.24
   611.4  783.08   640.4  785.47   659.9   786.1   669.7  787.69   679.5  791.53
     699  802.73   718.6  815.19   786.9  863.62   806.5  876.47     826  887.77
   845.5  897.21   894.4  913.89   913.9  918.28   943.2   921.6   982.3  922.45
#Mann= 3 , 0 , 0
       0     .05       0   563.2    .045       0   611.4     .07       0
Bank Sta=563.2,611.4
XS Rating Curve= 0 ,0
Exp/Cntr=0.3,0.1

Type RM Length L Ch R = 1 ,104254.4,420.9,408.3,395.3
XS GIS Cut Line= 4
     1911415.031      616491.494     1911783.087      616583.508
     1911890.877      616657.881     1912110.778      616800.088
#Sta/Elev= 30
       0  907.71    19.5  906.41    29.2   905.1    38.9  902.66    48.6   898.6
    77.8  882.82     107  865.47   136.2  847.27     214  796.68   223.7   791.4
   233.5  788.14   243.2  786.95   272.4  785.88   350.2  784.91   407.4  781.43
   426.2  780.92   435.5  781.86   444.9  783.87   463.6  789.37   472.9   790.8
   482.3  791.62   491.6  793.15     501  796.61   558.8  824.99   587.9  838.46
   646.1  862.06   694.6  882.96   704.3  886.46     714   889.3   772.2  903.88
#Mann= 3 , 0 , 0
       0     .05       0   407.4    .045       0   444.9     .08       0
Bank Sta=407.4,444.9
XS Rating Curve= 0 ,0
Exp/Cntr=0.3,0.1

Type RM Length L Ch R = 1 ,103846.1,413.8,401.1,389.9
XS GIS Cut Line= 4
     1911244.459      616916.407     1911576.056      616933.768
     1911687.266      616937.739     1912034.389      616944.185
#Sta/Elev= 30
       0  916.19    39.1  911.28    68.4  905.98    87.9  901.66     127  890.86
   175.8  873.69   185.6  868.98   195.3  863.24   214.9  850.02     293  790.76
   302.8  785.15   312.5  782.02   322.3  780.92     332  780.87   350.6  781.66
   387.7  783.19   472.3  782.62   481.9  783.23   491.6  785.44   510.8  792.95
   520.5  795.41   539.8  798.93   549.4  803.27     588  823.28   645.9   850.3
   703.7  878.76   732.6   891.8   742.3  895.31   751.9  897.54   790.5  902.59
#Mann= 3 , 0 , 0
       0     .08       0   350.6    .045       0   387.7     .08       0
Bank Sta=350.6,387.7
XS Rating Curve= 0 ,0
Exp/Cntr=0.3,0.1

Type RM Length L Ch R = 1 ,103445.1,400.2,394.9,387.9
XS GIS Cut Line= 4
     1911421.033      617502.995     1911803.427       617273.57
      1911876.75      617236.571     1912119.459      617114.324
#Sta/Elev= 30
       0  881.94    38.8   880.8    67.9   878.8    87.2  879.02    96.9  879.97
   106.6  881.82     126  887.12   145.4  889.24   155.1  889.54   184.2   888.9
   203.6  885.69   261.8  865.87   281.1  858.38   310.2  842.66   368.4  812.74
   397.5  795.01   416.9  781.91   426.6  777.66   436.2  776.53   464.2  777.24
   537.8  780.11   547.5  781.63   566.9  787.98   576.6  790.48   586.3  792.04
     596     795   605.7   801.1   625.1  817.79   634.8  824.08   799.8  913.87
#Mann= 3 , 0 , 0
       0      .1       0   426.6    .045       0   464.2     .08       0
Bank Sta=426.6,464.2
XS Rating Curve= 0 ,0
Exp/Cntr=0.3,0.1

Type RM Length L Ch R = 1 ,103050.2,218.5,229.5,240.5
XS GIS Cut Line= 4
     1911692.771       617780.26     1912060.431      617558.768
     1912149.329      617472.138     1912294.806      617296.616
#Sta/Elev= 30
       0  927.43    29.3  921.83    48.8  915.92   107.3  892.22   126.8   884.9
   146.3  878.75   185.4  868.44   234.1  847.72   302.4  827.04   321.9  819.61
   360.9  803.11   380.4  795.88   429.2  785.19   448.3  779.31   457.9  777.11
   467.4  776.59     477  777.09   486.5  778.55   505.6  781.88   534.2  785.31
   543.8  789.55   572.4  811.54   581.8  817.57   619.8  838.76   676.8  873.54
   695.8  883.85   724.3   896.5   743.3  902.82   762.3  907.15   781.3  909.96
#Mann= 3 , 0 , 0
       0      .1       0   448.3    .045       0   486.5     .08       0
Bank Sta=448.3,486.5
XS Rating Curve= 0 ,0
Exp/Cntr=0.3,0.1

Type RM Length L Ch R = 1 ,102820.7,122.7,121.2,119.9
XS GIS Cut Line= 4
      1911737.08      617823.959     1912198.018      617714.584
     1912312.601      617679.428     1912721.455      617379.949
#Sta/Elev= 30
       0  910.77    38.7  894.11   106.4  860.72   125.7   853.1     145  851.25
     203  856.36   251.4  858.73   270.7     858     290  854.99   309.4  849.92
   367.4  830.49   501.4  779.46   519.8   776.6   547.5  779.47   603.3  784.75
   671.6  788.93   720.3  796.47     769  797.87   788.5   800.5   817.8  811.25
   876.2  838.59   895.7   846.3   905.5  848.38     925  848.98     964  858.94
   973.7  863.39  1002.9  881.55  1022.4  889.47  1061.4     902  1100.4  907.65
#Mann= 3 , 0 , 0
       0      .1       0   501.4    .045       0   547.5     .07       0
Bank Sta=501.4,547.5
XS Rating Curve= 0 ,0
Exp/Cntr=0.3,0.1

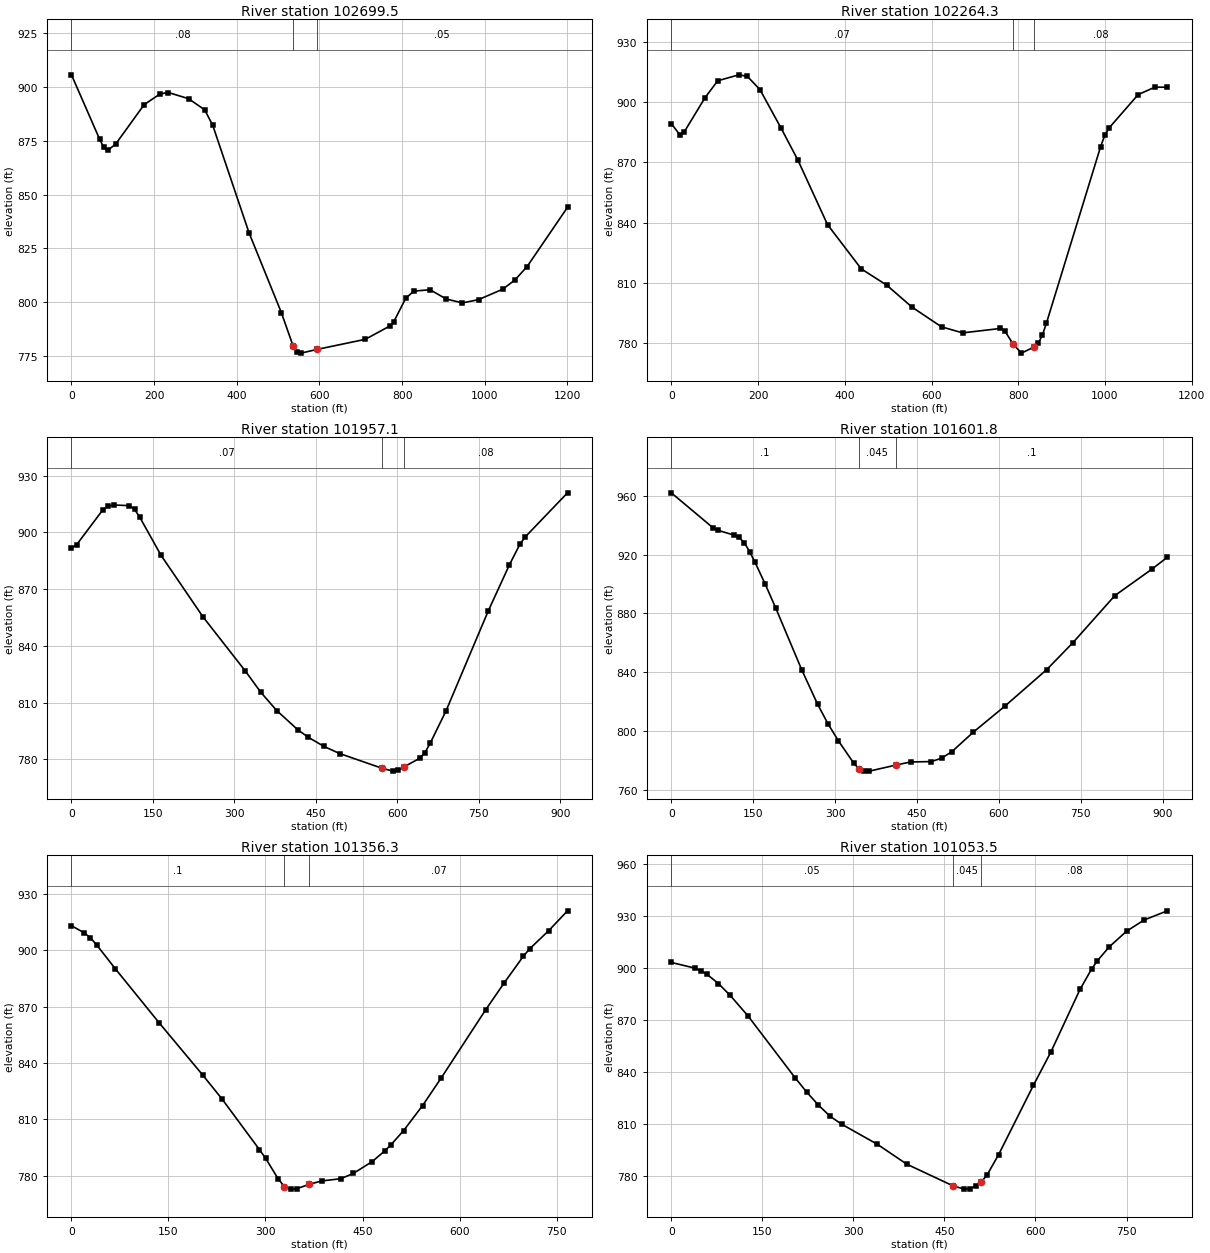
Type RM Length L Ch R = 1 ,102699.5,426.1,435.2,444
XS GIS Cut Line= 4
     1911742.222      617877.214     1912247.497      617826.563
      1912337.34      617794.011     1912932.827      617835.244
#Sta/Elev= 30
       0  905.69    68.4  875.63    78.1  871.97    87.9  870.55   107.4   873.6
   175.8  891.82   214.8  896.86   234.4  897.46   283.2  894.61   322.3  889.42
   341.8  882.23   429.7  832.21   507.8  795.16   536.5   779.5     546  776.93
   555.6  776.28   593.8  777.99     711   782.7   769.7  788.83   779.5  790.73
   808.9  801.81   828.4  805.11   867.6  805.76   906.7  801.46   945.9  799.63
     985  801.15  1043.7  806.02  1073.1  810.31  1102.4  816.49  1200.3   844.1
#Mann= 3 , 0 , 0
       0     .08       0   536.5    .045       0   593.8     .05       0
Bank Sta=536.5,593.8
XS Rating Curve= 0 ,0
Exp/Cntr=0.3,0.1

Type RM Length L Ch R = 1 ,102264.3,285.1,307.1,329.1
XS GIS Cut Line= 4
     1911772.973      617948.061     1912470.305      618129.298
     1912605.136      618134.723     1912890.726       618174.22
#Sta/Elev= 30
       0   889.4    19.5  883.82    29.2  885.01    77.9  902.36   107.1  910.75
   155.8  913.71   175.3  912.96   204.5  906.31   253.2  887.08   292.1  871.08
   360.2  838.99   438.1   816.9   496.6  808.82     555  797.84   623.1  787.99
   671.8  784.99     759   787.2   768.7  786.07     788  779.46   807.2  774.89
   836.2   777.9   845.8  779.76   855.4  783.72     865  789.86     990  877.95
   999.6  883.58  1009.2  887.15  1076.5  903.85  1114.9  907.54  1143.8  907.55
#Mann= 3 , 0 , 0
       0     .07       0     788    .045       0   836.2     .08       0
Bank Sta=788,836.2
XS Rating Curve= 0 ,0
Exp/Cntr=0.3,0.1

Type RM Length L Ch R = 1 ,101957.1,371.1,355.3,339.3
XS GIS Cut Line= 4
     1911779.615      618000.609     1912239.684       618151.65
     1912329.962      618302.692      1912482.74      618504.081
#Sta/Elev= 30
       0  891.73     9.7  893.57    58.1  912.05    67.8   913.9    77.5  914.48
   106.5  914.14   116.2  912.11   125.9  907.92   164.6  887.98   242.1  855.32
   319.6  826.85   348.6  815.42   377.7  805.82   416.4  795.68   435.8  791.68
   464.9   786.8     494  783.03   572.2  775.23   591.8  773.77   601.5  774.31
   611.3   775.9   640.6  780.51   650.4  783.48   660.2  788.51   689.4  805.63
   767.1  858.46     806  882.81   825.5  893.81   835.2  897.61     913  920.91
#Mann= 3 , 0 , 0
       0     .07       0   572.2    .045       0   611.3     .08       0
Bank Sta=572.2,611.3
XS Rating Curve= 0 ,0
Exp/Cntr=0.3,0.1

Type RM Length L Ch R = 1 ,101601.8,255.2,245.5,235.6
XS GIS Cut Line= 4
      1911585.17      618250.609     1911871.629      618326.997
     1912069.545      618391.234     1912446.281      618537.067
#Sta/Elev= 30
       0  962.04    76.5  938.21    86.1  936.43   114.8  933.31   124.3  931.66
   133.9     928   143.4  922.09     153  915.04   172.1  899.81   191.3  883.61
   239.1  841.43   267.8   818.3   286.9  804.91   305.9  793.37   334.3  777.98
   343.8  774.24   353.2  772.74   362.7  772.67   411.1  776.77   438.3  778.91
   476.2  779.17   495.1  781.49   514.2  786.02   552.6  799.02   610.4  816.72
   687.3  841.66   735.4  860.02   812.3   892.1   879.7  909.97   908.5  918.21
#Mann= 3 , 0 , 0
       0      .1       0   343.8    .045       0   411.1      .1       0
Bank Sta=343.8,411.1
XS Rating Curve= 0 ,0
Exp/Cntr=0.3,0.1

Type RM Length L Ch R = 1 ,101356.3,299.4,302.9,306.3
XS GIS Cut Line= 4
     1911668.504      618618.664     1911958.434      618597.831
      1912053.92      618585.678     1912432.393        618620.4
#Sta/Elev= 30
       0   913.2    19.4  909.44    29.1  906.84    38.8  903.02    67.8  890.24
   135.6   861.4   203.5  833.34   232.5  820.94   290.7  793.78   300.3  789.11
   319.6  778.22   329.2  774.14   338.8  772.74   348.4  772.98   367.7   775.3
   386.9  777.11   416.2  778.28   435.7  781.08   464.9  787.41   484.4   793.1
   494.1  796.42   513.6  803.97   542.9   817.3   572.1  832.23   640.3   868.3
   669.5  882.91   698.8  896.96   708.5  900.88   737.8  910.52     767  921.13
#Mann= 3 , 0 , 0
       0      .1       0   329.2    .045       0   367.7     .07       0
Bank Sta=329.2,367.7
XS Rating Curve= 0 ,0
Exp/Cntr=0.3,0.1

Type RM Length L Ch R = 1 ,101053.5,101.4,107.5,113.5
XS GIS Cut Line= 4
      1911670.24      618755.817     1912062.601      618865.192
     1912194.431      618869.238     1912472.323      618859.984
#Sta/Elev= 30
       0  903.46    38.8  900.18    48.5  898.68    58.2  896.76    77.6  891.29
      97  884.44   126.1  872.72   203.7  837.03   223.1  828.65   242.4  821.15
   261.8  814.65   281.2  810.02   339.4  798.56   387.9  787.08   463.8  774.62
   482.7  772.67   492.1  773.02   501.5  774.41     511  776.94   520.4  780.92
   539.2  792.51   596.7  832.63   625.5  851.87   673.4   887.9   692.6  899.74
   702.2  904.51   721.4   912.4   750.1  921.48   778.9  927.93   817.3  933.24
#Mann= 3 , 0 , 0
       0     .05       0   463.8    .045       0     511     .08       0
Bank Sta=463.8,511
XS Rating Curve= 0 ,0
Exp/Cntr=0.3,0.1