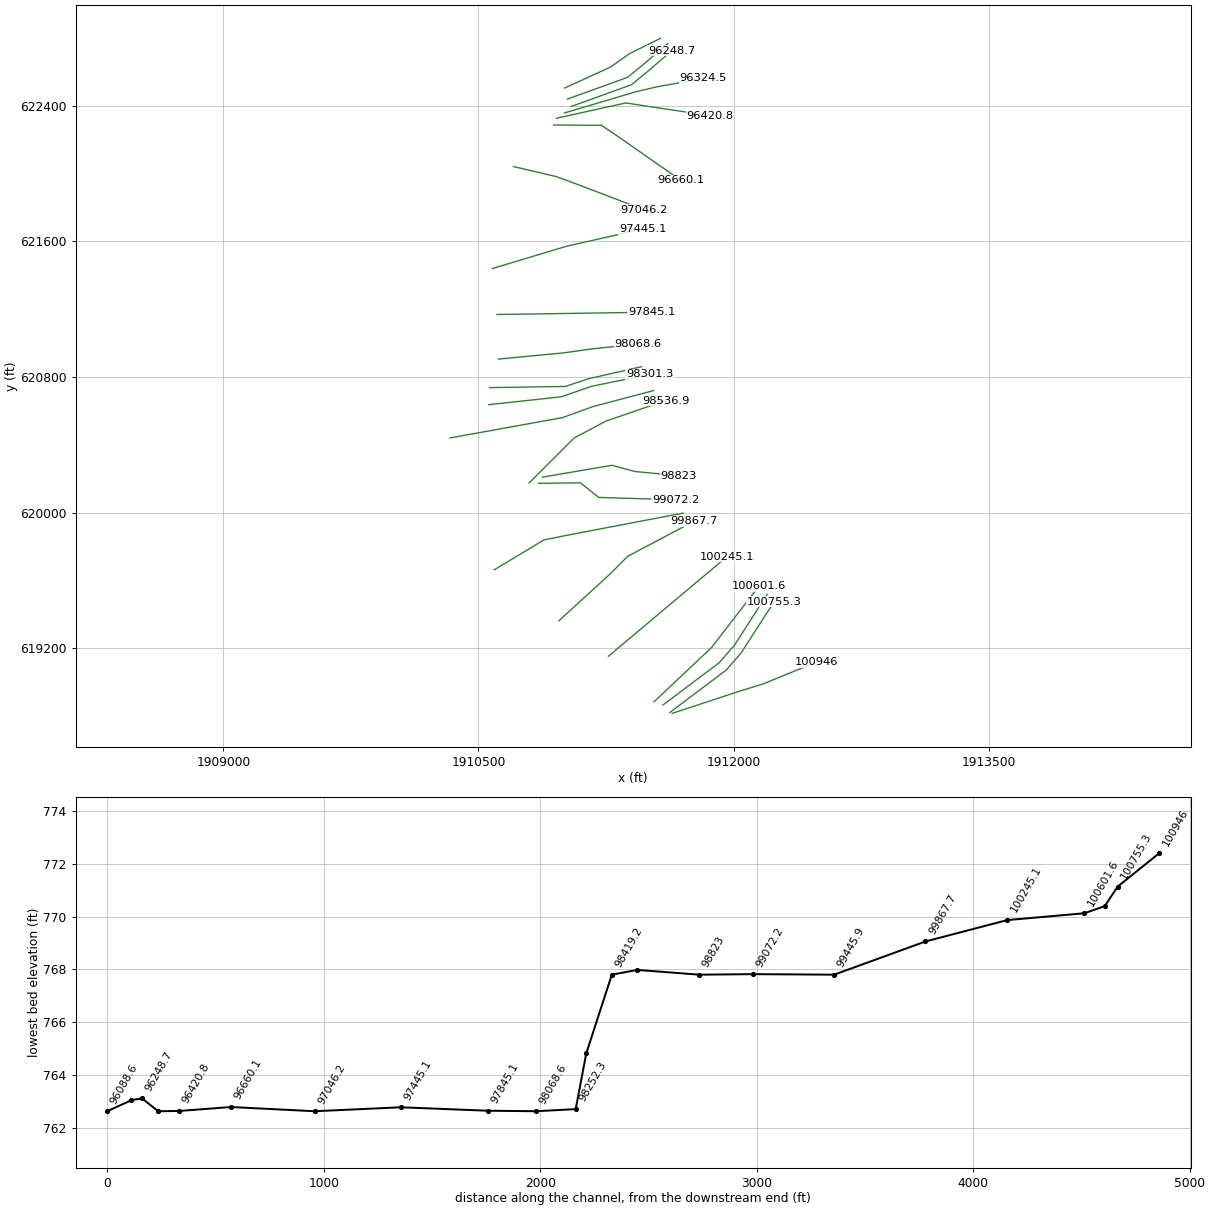
HEC-RAS study HenryFork.prj: HenryFork

--- HenryFork.g01 (geometry) --- (continued)

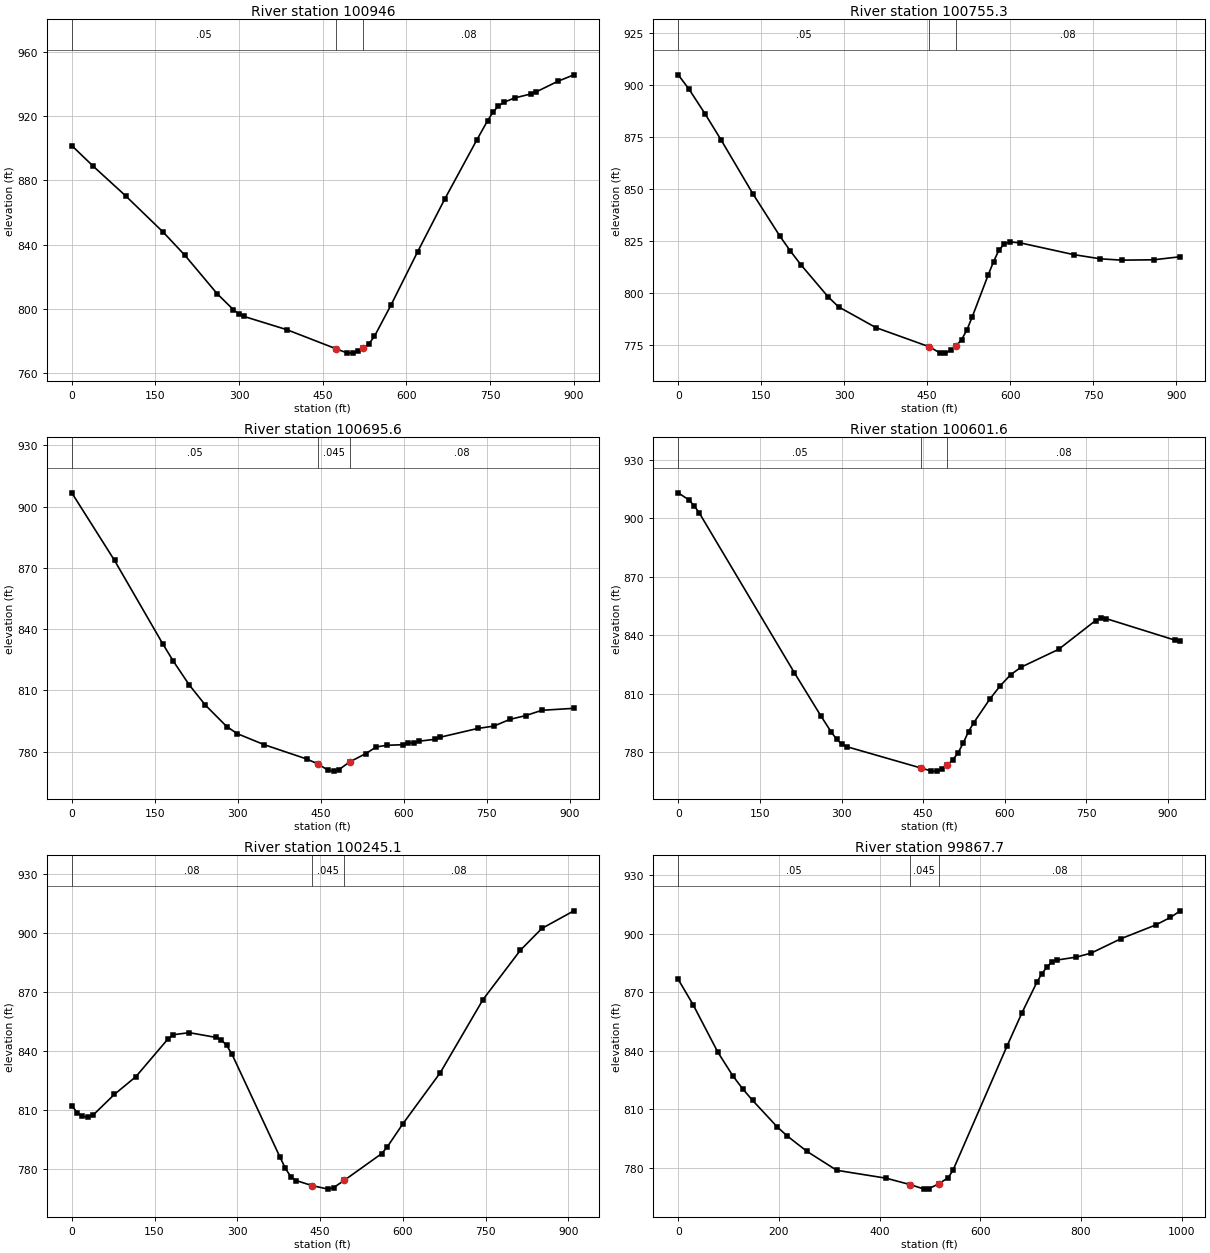
Type RM Length L Ch R = 1 ,100946  ,178,190.7,203.3
XS GIS Cut Line= 4
      1911638.99      618816.581     1912033.087      618946.789
     1912173.712      618990.192     1912486.212      619118.664
#Sta/Elev= 30
       0  901.65    38.6  888.77    96.5  870.38   164.1  847.68   202.7  833.38
   260.6  809.42   289.6   799.5   299.2  796.94   308.9  795.24   386.1  786.94
   473.9  775.09   493.5  772.52   503.4   772.4   513.2  773.45     523  775.38
   532.8   778.2   542.6  782.86   571.9  802.07   620.1  835.57   668.4  868.18
   726.3  905.28   745.6  917.26   755.3  922.59     765  926.36   774.6  928.61
   793.9  931.35   822.9   933.8   832.5  935.09   871.1  941.66   900.1  945.74
#Mann= 3 , 0 , 0
       0     .05       0   473.9    .045       0     523     .08       0
Bank Sta=473.9,523
XS Rating Curve= 0 ,0
Exp/Cntr=0.3,0.1

Type RM Length L Ch R = 1 ,100755.3,59.8,59.7,59.7
XS GIS Cut Line= 4
     1911625.101      618821.789     1911956.698      619071.789
      1912045.24       619174.22     1912237.948      619474.567
#Sta/Elev= 30
       0  905.02    19.3  898.19    48.3  886.34    77.3  873.77   135.2  847.68
   183.5  827.52   202.8  820.21   222.1  813.53   270.4  798.37   289.7  793.42
   357.3  783.42     454  774.17   473.3   771.2     483  771.14   492.6  772.48
   502.3  774.62     512  777.56   521.7  782.24   531.3  788.52   560.3  808.78
     570   815.2   579.6  820.68   589.2  823.61   598.9  824.65   618.2  824.18
   714.6  818.54   762.9  816.51   801.4  815.87   859.3  816.04   907.5  817.51
#Mann= 3 , 0 , 0
       0     .05       0     454    .045       0   502.3     .08       0
Bank Sta=454,502.3
XS Rating Curve= 0 ,0
Exp/Cntr=0.3,0.1

Type RM Length L Ch R = 1 ,100695.6,95.7,94,95.3
XS GIS Cut Line= 4
     1911584.736       618866.06     1911916.334       619116.06
     1912004.875      619218.491     1912197.584      619518.838
#Sta/Elev= 30
       0  906.78    77.3  873.65   164.2   832.9   183.5  824.31   212.5  812.58
   241.4  802.77   280.1  792.24   299.4  788.73   347.7  783.37     425  776.31
   444.3  773.98   463.6  770.82   473.3   770.4     483  771.16   502.3   774.9
   531.3  778.99   550.7  782.28     570  783.06   598.9  783.35   608.5  784.26
   618.2  784.22   627.8  785.07   656.8  786.02   666.4  787.05   733.9  791.32
   762.9  792.46   791.8  795.75   820.7  797.63   849.7  800.21   907.5  801.18
#Mann= 3 , 0 , 0
       0     .05       0   444.3    .045       0   502.3     .08       0
Bank Sta=444.3,502.3
XS Rating Curve= 0 ,0
Exp/Cntr=0.3,0.1

Type RM Length L Ch R = 1 ,100601.6,358.4,356.5,351.7
XS GIS Cut Line= 3
     1911532.349      618884.954     1911870.327      619204.602
     1912149.152       619566.95
#Sta/Elev= 30
       0  913.11    19.4   909.5    29.1  906.56    38.8   902.7   213.2  820.76
   261.7  798.66     281  790.25   290.8   786.6   300.4  783.94   310.1  782.65
   445.8  771.74   465.2  770.17   474.9  770.13   484.6  771.16   494.4  773.37
   504.1  775.82   513.8  779.37   523.6  784.55   533.3  790.46     543  795.04
   572.2  807.05   591.6  813.98   611.1  819.77   630.6  823.64   698.7  832.68
   766.8   847.5   776.5  848.78   786.2  848.48   912.7  837.42   922.4   837.1
#Mann= 3 , 0 , 0
       0     .05       0   445.8    .045       0   494.4     .08       0
Bank Sta=445.8,494.4
XS Rating Curve= 0 ,0
Exp/Cntr=0.3,0.1

Type RM Length L Ch R = 1 ,100245.1,375.3,377.3,379.4
XS GIS Cut Line= 3
     1911264.377      619153.854     1911612.405      619446.944
     1911960.432      619740.034
#Sta/Elev= 30
       0  812.37     9.7  808.79    19.4  806.85      29  806.46    38.7  807.52
    77.4  818.06   116.2  827.04   174.3  846.18   183.9  848.35     213   849.4
   261.4  846.99   271.1  845.68   280.7  842.95   290.4  838.43   377.6  786.01
   387.2  780.43   396.9  776.21   406.6  774.23   435.6  771.66   464.7  769.87
   474.4  770.59   493.7   774.3   561.5  787.88   571.2  791.08   600.2  803.11
     668  829.09   745.4  866.25   813.2  891.34   851.9  902.35     910  911.33
#Mann= 3 , 0 , 0
       0     .08       0   435.6    .045       0   493.7     .08       0
Bank Sta=435.6,493.7
XS Rating Curve= 0 ,0
Exp/Cntr=0.3,0.1

Type RM Length L Ch R = 1 ,99867.7 ,436.9,421.9,394.4
XS GIS Cut Line= 4
     1910972.757      619362.588      1911277.58      619641.749
     1911377.271      619742.796     1911768.119      619949.855
#Sta/Elev= 30
       0  876.51    29.5  863.58    78.7  839.22   108.3  827.18   127.9   820.5
   147.6  814.56   196.8  800.91   216.5   796.3   255.9  788.38   314.9  778.71
   413.3  774.65   460.6  771.39     489  769.06   498.5  769.38   517.4  771.76
   536.4  774.91   545.8  778.66   653.6  842.55   683.1  859.48   712.6  875.06
   722.4   879.4   732.2  882.74     742  885.41   751.9  886.41   791.2  887.95
   820.7  890.02   879.6  897.36   948.4  904.37   977.9  908.26   997.6  911.65
#Mann= 3 , 0 , 0
       0     .05       0   460.6    .045       0   517.4     .08       0
Bank Sta=460.6,517.4
XS Rating Curve= 0 ,0
Exp/Cntr=0.3,0.1

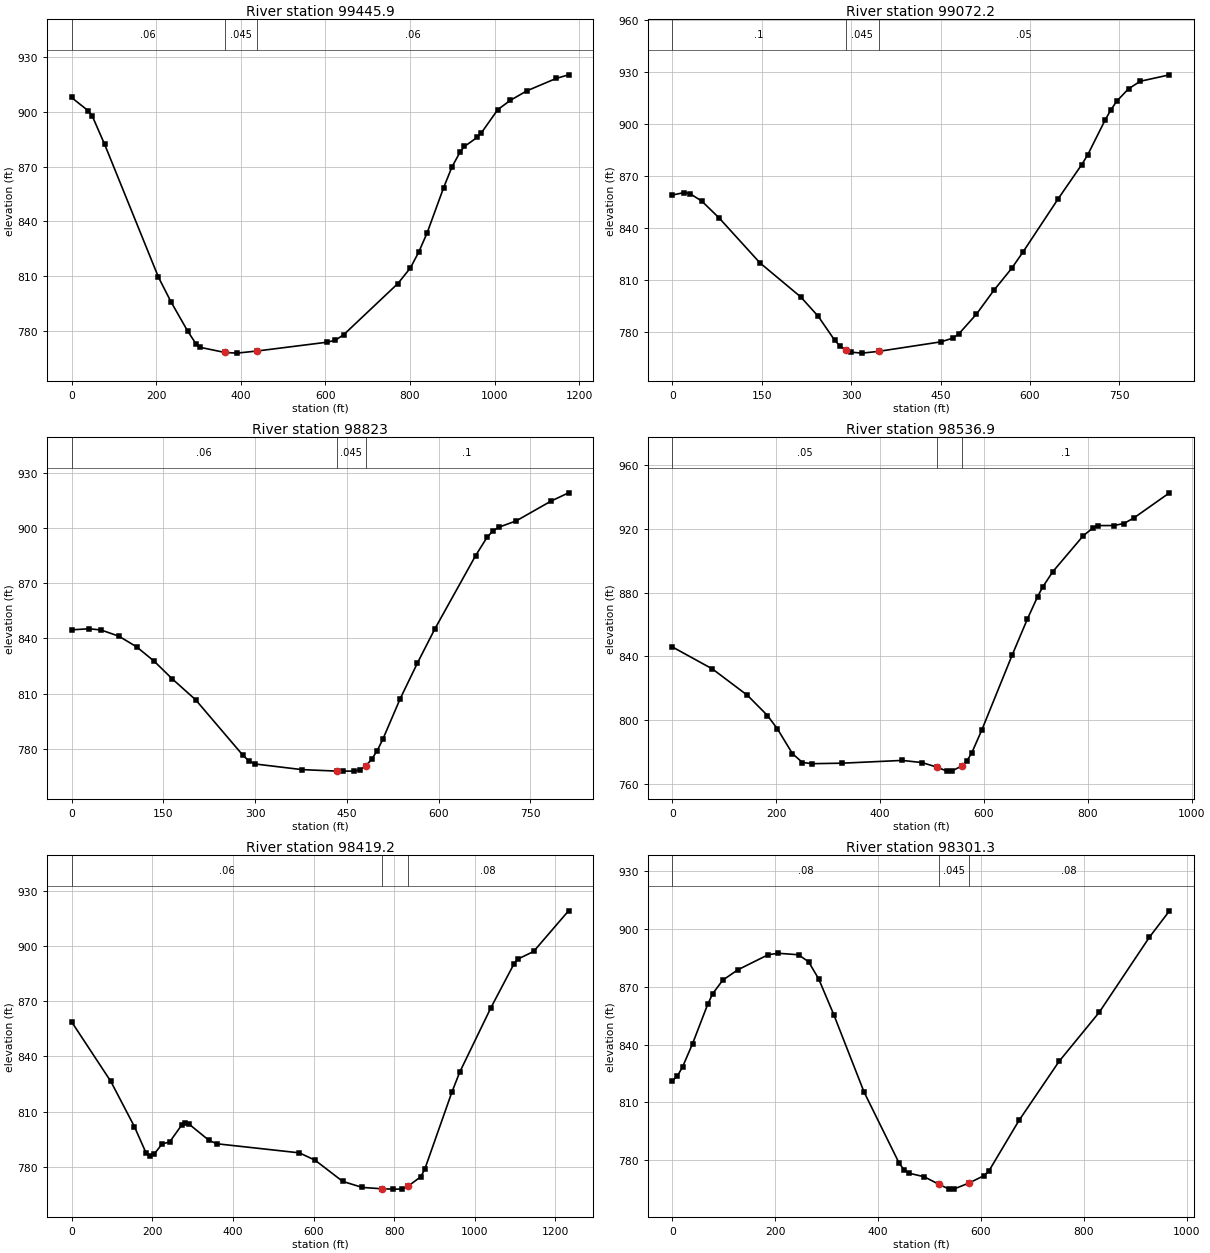
Type RM Length L Ch R = 1 ,99445.9 ,391.1,373.7,367.7
XS GIS Cut Line= 4
     1910592.549      619662.935     1910885.952      619840.018
     1911045.927      619871.681     1911703.087      619997.625
#Sta/Elev= 30
       0  907.84    39.2  900.61      49   897.7    78.3  882.15   205.6  809.33
     235  795.96   274.2  780.01   293.7  773.04   303.5     771   361.9  768.19
   390.7   767.8   438.6  768.96   604.2  773.79   623.9  774.91   643.5  777.91
   771.5  805.94     801  814.47   820.7  823.13   840.3   833.5   879.7  858.51
   899.4  869.84   919.1  878.21   928.9     881   958.4  885.93   968.3   888.3
  1007.6  901.18  1037.1  906.25  1076.5   911.5  1145.4  918.26  1174.9  920.25
#Mann= 3 , 0 , 0
       0     .06       0   361.9    .045       0   438.6     .06       0
Bank Sta=361.9,438.6
XS Rating Curve= 0 ,0
Exp/Cntr=0.3,0.1

Type RM Length L Ch R = 1 ,99072.2 ,241,249.2,257.6
XS GIS Cut Line= 4
     1910854.702      620173.352     1911099.499      620176.292
     1911207.132      620090.018     1911658.521      620076.129
#Sta/Elev= 30
       0  858.95    19.6  860.36    29.4  859.73      49  855.52    78.3  845.76
   146.9  819.83   215.4   800.2   244.8  789.01   272.4  775.21   281.6  771.82
   290.8  769.55     300  768.36   318.4  767.82     346  768.83   451.5  774.37
   471.1  776.54   480.9  778.95   510.4  790.33   539.8  804.12   569.3   816.6
   588.9  826.31   647.8  856.92   687.1  876.48   696.9  881.96   726.4   902.2
   736.2  908.14     746  913.08   765.6  920.16   785.3  924.51   834.4  928.23
#Mann= 3 , 0 , 0
       0      .1       0   290.8    .045       0     346     .05       0
Bank Sta=290.8,346
XS Rating Curve= 0 ,0
Exp/Cntr=0.3,0.1

Type RM Length L Ch R = 1 ,98823   ,269.1,286.1,303.2
XS GIS Cut Line= 4
     1910875.535       620209.81     1911284.817      620279.353
     1911420.674      620242.796     1911675.882      620218.491
#Sta/Elev= 30
       0  844.63      29   845.2    48.3  844.54    77.2  841.19   106.2  835.42
   135.2  827.52   164.1  818.11   202.8  806.59     280  776.44   289.6  773.44
   299.3  771.71   376.5  768.62   433.9  767.81   443.3   767.8     462   767.8
   471.4   768.5   480.8   770.6   490.2  774.14   499.6  778.96   508.9  785.29
   537.1  807.19   565.3  826.62   593.8  845.18   660.3  884.97   679.3  895.07
   688.8  898.43   698.3  900.42   726.8  903.89   783.7  914.64   812.2  919.12
#Mann= 3 , 0 , 0
       0     .06       0   433.9    .045       0   480.8      .1       0
Bank Sta=433.9,480.8
XS Rating Curve= 0 ,0
Exp/Cntr=0.3,0.1

Type RM Length L Ch R = 1 ,98536.9 ,120.9,117.7,114.4
XS GIS Cut Line= 4
      1910797.41      620175.088     1911063.035      620440.713
     1911248.799      620539.671     1911599.493      620661.199
#Sta/Elev= 30
       0  845.84    77.1  832.04   144.5  815.51     183  802.86   202.3  794.41
   231.2  778.92   250.4  773.39   269.7  772.65   327.5  772.97   442.6   774.7
   480.9  773.33   509.6  770.46   528.7  767.98   538.3  768.09   557.4  771.24
     567  774.29   576.6  779.52   595.9  793.83   654.5  840.95   683.8  863.52
   703.3  877.46   713.1  883.46   732.6   893.1   791.2  915.61   810.8  920.76
   820.5  921.99   849.8  922.02   869.4  923.28   888.9  926.83   957.3  942.54
#Mann= 3 , 0 , 0
       0     .05       0   509.6    .045       0   557.4      .1       0
Bank Sta=509.6,557.4
XS Rating Curve= 0 ,0
Exp/Cntr=0.3,0.1

Type RM Length L Ch R = 1 ,98419.2 ,118.3,117.9,117.8
XS GIS Cut Line= 4
     1910332.132      620440.713      1910993.59      620560.504
     1911175.882      620626.477     1911530.049      620720.227
#Sta/Elev= 30
       0  858.93    97.4  826.44   155.9  801.83   185.1  787.34   194.8  785.73
   204.6  786.77   224.1  792.27   243.6  793.54   272.8  802.55   282.5  803.63
   292.3  803.02     341  794.31   360.5  792.48     565  787.54     604  783.53
   672.2  772.03   720.7  768.73   769.2  767.99   798.2   767.8   818.6  767.84
   833.6  769.25   866.1  774.56   875.7  778.54   943.2  820.63   962.5  831.44
  1039.6  866.41  1097.5  890.57  1107.1  893.05  1145.7  897.13  1232.4  919.26
#Mann= 3 , 0 , 0
       0     .06       0   769.2    .045       0   833.6     .08       0
Bank Sta=769.2,833.6
XS Rating Curve= 0 ,0
Exp/Cntr=0.3,0.1

Type RM Length L Ch R = 1 ,98301.3 ,49.3,49,48.6
XS GIS Cut Line= 4
     1910559.563      620636.893     1910988.382      620683.768
     1911161.993      620744.532     1911505.743      620815.713
#Sta/Elev= 30
       0  821.19     9.8   823.7    19.6  828.31    39.2  840.49    68.6  860.93
    78.4  866.48      98  873.51   127.4  878.87   186.3   886.7   205.9  887.43
   245.1  886.66   264.7     883   284.3  874.12   313.7  855.52   372.6  815.27
     441   778.2   450.7  774.76   460.4  773.08   489.5  771.24   518.5  767.26
   537.9  764.82   547.5   764.9   576.6  767.99   605.6  771.81   615.3  774.26
   673.8  800.53   751.8  831.26   829.8  856.74   927.4   895.8   966.4   909.5
#Mann= 3 , 0 , 0
       0     .08       0   518.5    .045       0   576.6     .08       0
Bank Sta=518.5,576.6
XS Rating Curve= 0 ,0
Exp/Cntr=0.3,0.1

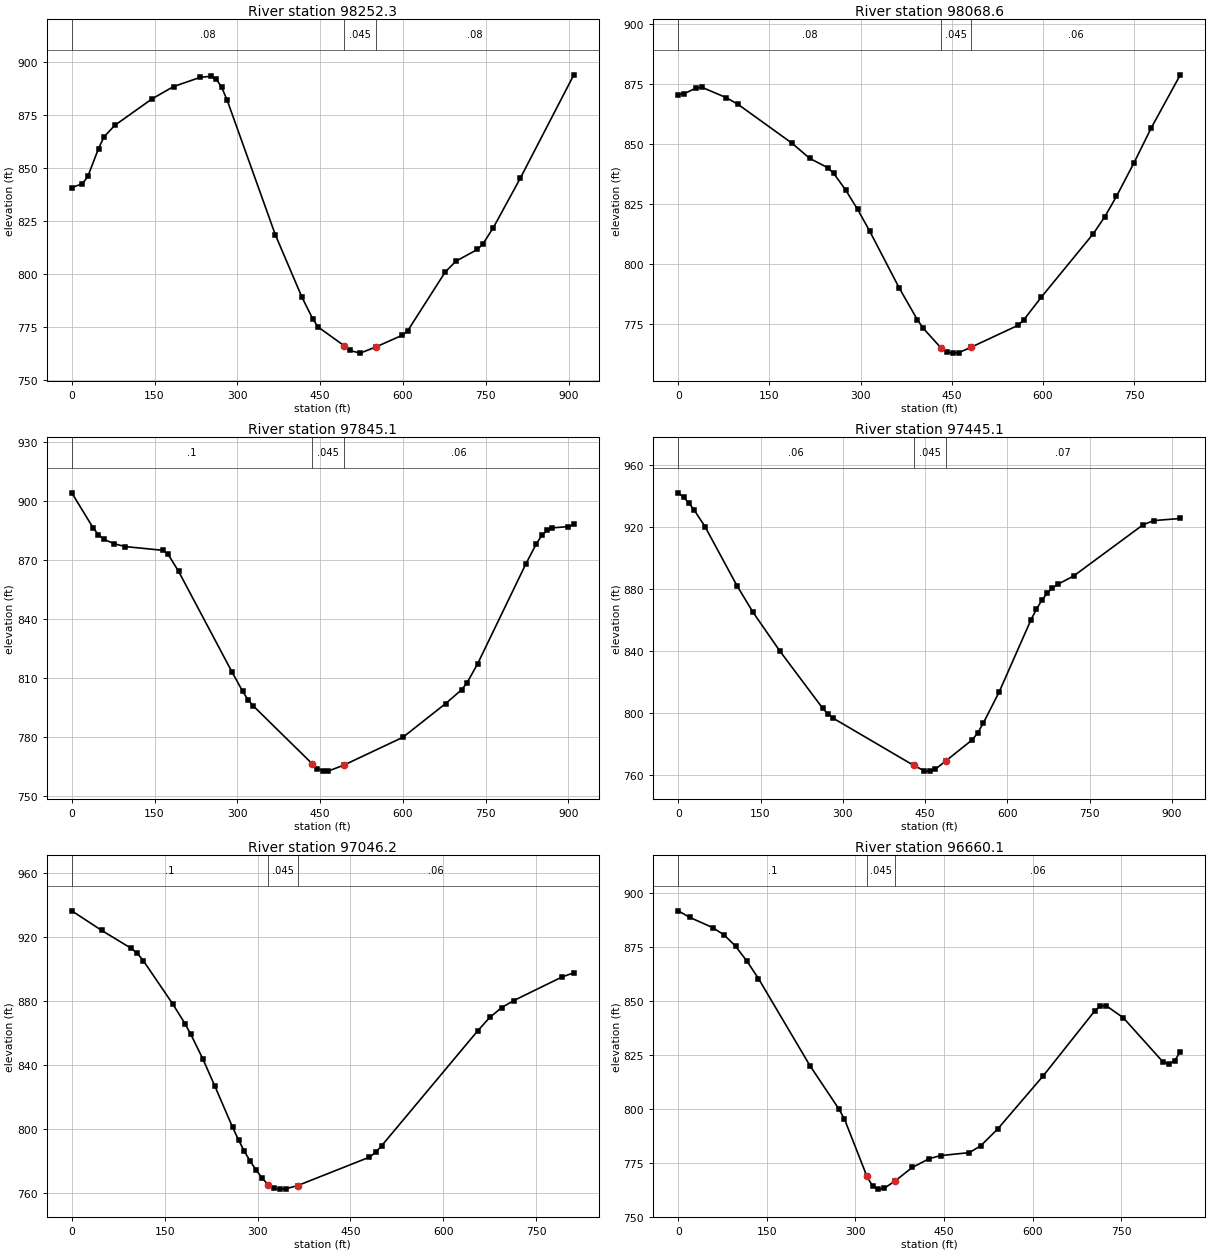
Type RM Length L Ch R = 1 ,98252.3 ,187.7,183.6,179.4
XS GIS Cut Line= 4
     1910564.771      620737.588     1911010.952      620744.532
     1911146.376      620789.636     1911458.868      620860.852
#Sta/Elev= 30
       0  840.74    19.4  842.55    29.1  845.99    48.5  859.13    58.2  864.53
    77.6  869.98   145.5  882.55   184.3  888.32   232.8  892.68   252.2  893.18
   261.9  891.84   271.6  887.93   281.3  882.04   368.6  818.58   417.1  788.96
   436.5  778.87   446.2  775.02   493.8  766.11   503.3  763.98   522.4   762.7
   550.9   765.6   598.7  771.13   608.4  773.18   676.4  800.89   695.8  806.01
   734.7  811.55   744.4     814   763.8   821.9   812.4  845.07   909.5  893.86
#Mann= 3 , 0 , 0
       0     .08       0   493.8    .045       0   550.9     .08       0
Bank Sta=493.8,550.9
XS Rating Curve= 0 ,0
Exp/Cntr=0.3,0.1

Type RM Length L Ch R = 1 ,98068.6 ,226.3,223.5,220.7
XS GIS Cut Line= 4
      1910618.59      620905.991     1911000.535      620942.449
     1911174.146      620966.754     1911439.771      620994.532
#Sta/Elev= 30
       0  870.59     9.8  871.07    29.5  873.39    39.4  873.66    78.7  869.42
    98.4  866.58   186.9   850.4   216.4  843.99     246  840.11   255.8  837.72
   275.5  830.78   295.1  822.71   314.8  813.71     364  789.65   393.4  776.61
   403.2  772.99   432.4  764.78   442.1  763.03   451.8  762.62   461.6  762.83
   481.1     765     559  774.23   568.5  776.51   597.1  785.91     683  812.56
   702.1   819.7   721.1  828.16   749.8   842.1   778.4  856.79   826.1  878.92
#Mann= 3 , 0 , 0
       0     .08       0   432.4    .045       0   481.1     .06       0
Bank Sta=432.4,481.1
XS Rating Curve= 0 ,0
Exp/Cntr=0.3,0.1

Type RM Length L Ch R = 1 ,97845.1 ,393.7,400,404.7
XS GIS Cut Line= 3
     1910608.859      621168.824     1911063.808      621175.625
     1911518.757      621182.426
#Sta/Elev= 30
       0  903.98    38.7  886.17    48.4  882.67    58.1   880.4    77.4  878.08
    96.8  876.68   164.6   874.8   174.3  872.88   193.6   864.1   290.4  812.99
   309.8  803.13   319.5  798.89   329.2   795.7   435.6  766.41   445.3  763.94
     455  762.81   464.7  762.64   493.7  765.76   600.2  779.84   677.7  796.97
   706.7  803.99   716.4  807.51   735.7  817.22   822.9  867.81   842.2  878.18
   851.9  882.34   861.6   884.9   871.3  886.18   900.3  886.84     910   887.9
#Mann= 3 , 0 , 0
       0      .1       0   435.6    .045       0   493.7     .06       0
Bank Sta=435.6,493.7
XS Rating Curve= 0 ,0
Exp/Cntr=0.3,0.1

Type RM Length L Ch R = 1 ,97445.1 ,413.5,398.9,385.8
XS GIS Cut Line= 3
     1910581.199      621439.518     1911020.246      621572.012
      1911465.78      621672.613
#Sta/Elev= 30
       0  942.34     9.8  939.47    19.5  935.67    29.3  931.11    48.8  920.54
   107.3  882.29   136.6  865.14   185.4  840.19   263.4  803.32   273.2  799.45
     283  796.81   429.3  766.46   448.8  762.94   458.6  762.77   468.3  763.86
   487.8  769.34   536.4  783.07   546.1  787.48   555.8  793.51   584.9  813.67
   643.2  860.47     653  867.18   662.7  872.89   672.4  877.47   682.1  880.93
   691.8  883.26     721  888.71   847.3  921.67   866.8  924.42   915.4  925.79
#Mann= 3 , 0 , 0
       0     .06       0   429.3    .045       0   487.8     .07       0
Bank Sta=429.3,487.8
XS Rating Curve= 0 ,0
Exp/Cntr=0.3,0.1

Type RM Length L Ch R = 1 ,97046.2 ,391.3,386.1,380.8
XS GIS Cut Line= 4
     1910705.396      622041.407     1910958.069       621981.87
     1911092.549      621932.032     1911473.318      621786.522
#Sta/Elev= 30
       0  936.32    48.1  924.13    96.2  912.86   105.8  909.76   115.4  905.27
   163.4  877.97   182.7  865.94   192.3  859.16   211.5  843.98   230.8  827.11
   259.6  801.25   269.2  793.35   278.7  786.18   288.3  779.88   297.8  774.47
   307.4  769.51     317   765.4   326.5  763.12   336.1  762.62   345.6  762.83
   364.8  764.85   480.6  782.58   490.4  785.53   500.1   789.6   655.4  861.44
   674.8  869.75   694.2  875.97   713.6   880.3   791.2  894.98   810.6  897.67
#Mann= 3 , 0 , 0
       0      .1       0     317    .045       0   364.8     .06       0
Bank Sta=317,364.8
XS Rating Curve= 0 ,0
Exp/Cntr=0.3,0.1

Type RM Length L Ch R = 1 ,96660.1 ,229.5,239.4,249.3
XS GIS Cut Line= 4
     1910941.507      622286.199     1911222.757      622284.463
     1911318.026      622220.391     1911689.771       621959.81
#Sta/Elev= 30
       0  891.81    19.4  888.78    58.2  884.04    77.6  880.66      97  875.42
   116.4  868.45   135.8  860.41   223.1  819.97   271.6   800.1   281.3  795.33
   319.5  768.66   329.1  764.15   338.7  762.78   348.2  763.08   367.4  766.61
   396.1  772.81     425  776.92   444.4  778.33   492.7   779.7     512  782.84
     541  790.71   618.2  815.41   705.2  845.42   714.8  847.68   724.5  847.82
   753.4  842.25   821.1  821.62   830.7  820.91   840.4   822.3     850  826.51
#Mann= 3 , 0 , 0
       0      .1       0   319.5    .045       0   367.4     .06       0
Bank Sta=319.5,367.4
XS Rating Curve= 0 ,0
Exp/Cntr=0.3,0.1

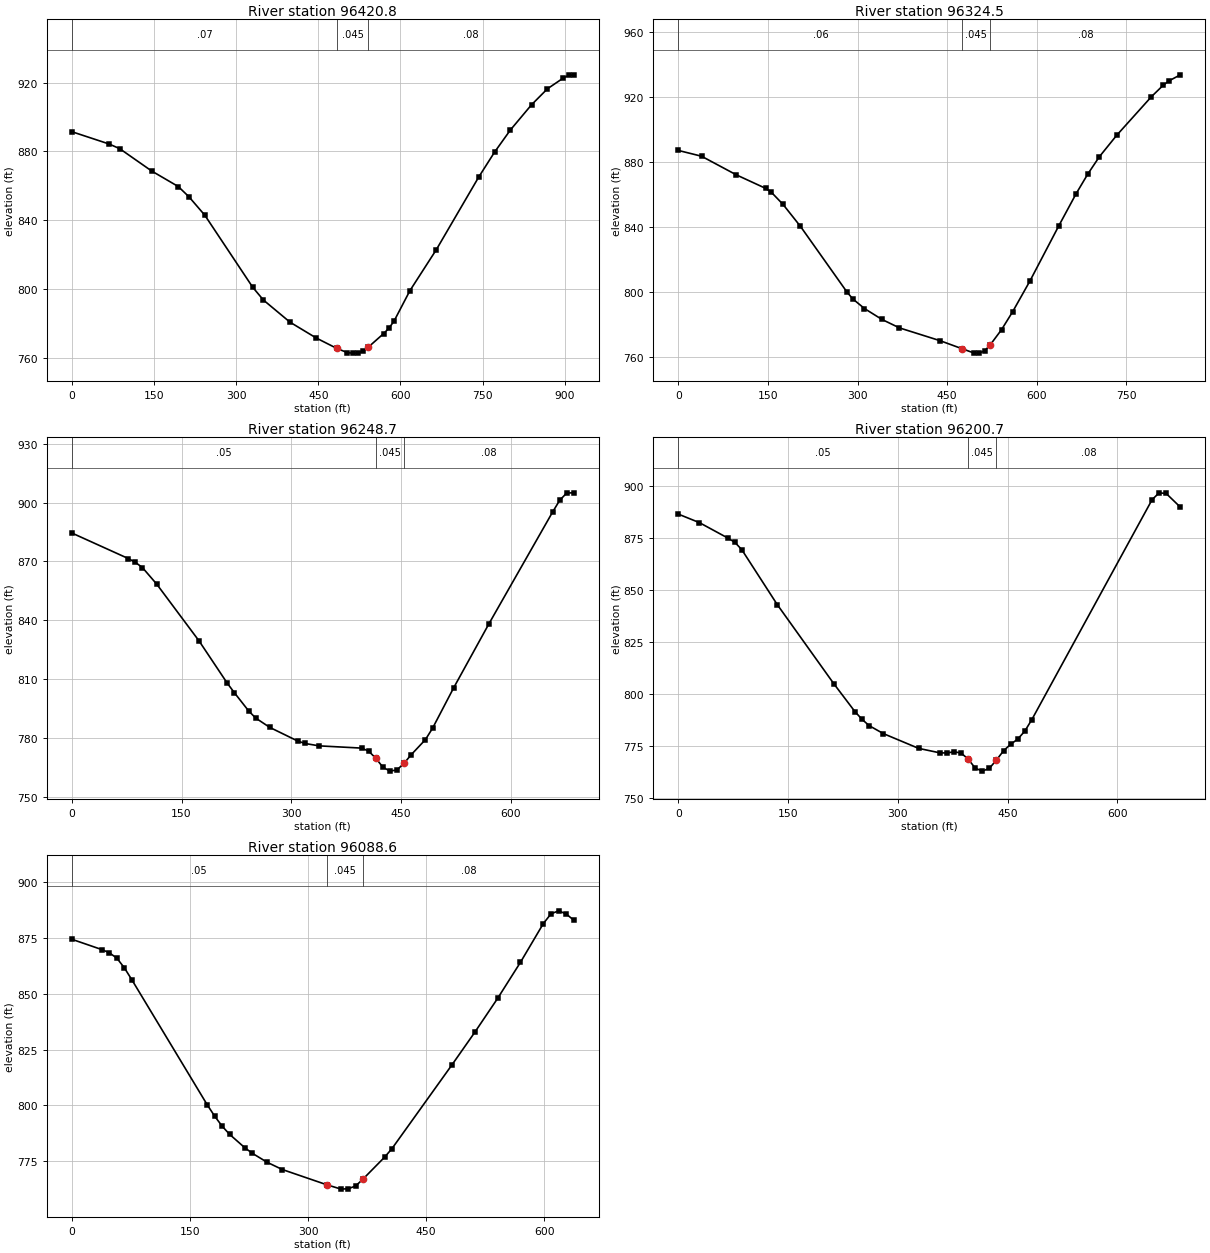
Type RM Length L Ch R = 1 ,96420.8 ,87.5,96.3,105
XS GIS Cut Line= 4
     1910958.868      622326.129     1911366.854      622416.407
     1911535.257      622390.366      1911859.91      622341.754
#Sta/Elev= 30
       0   891.5      68  884.35    87.5  881.62   145.8  868.63   194.4  859.58
   213.8  853.65   242.9  842.87   330.4  800.92   349.8  793.54   398.4  780.64
   446.3  771.43   484.1  765.33   503.1  762.92   512.5  762.63     522  762.71
   531.5   763.7   540.9     766   569.3  774.01   578.8  777.08   588.3  781.28
   617.2  798.96   665.5  822.86   742.7  865.02   771.7  879.57   800.7  892.51
   839.3  907.18   868.3  916.47   897.2  922.71   906.9  924.27   916.5  924.59
#Mann= 3 , 0 , 0
       0     .07       0   484.1    .045       0   540.9     .08       0
Bank Sta=484.1,540.9
XS Rating Curve= 0 ,0
Exp/Cntr=0.3,0.1

Type RM Length L Ch R = 1 ,96324.5 ,65.4,75.8,86.2
XS GIS Cut Line= 4
     1911005.743      622357.379     1911425.882      622482.379
     1911543.938      622510.157     1911819.979      622560.504
#Sta/Elev= 30
       0  887.19      39  883.62    97.4  872.14   146.1   863.9   155.8  861.48
   175.3  854.04   204.6  840.48   282.5  800.09   292.2   795.9   311.7  790.01
   340.9  783.32   370.2  778.13   438.3  770.25   475.7  765.22   494.3  762.78
   503.6  762.62     513  764.08   522.3  767.81     541  777.02   559.6  788.05
   588.6  806.99     637  840.96     666   860.7   685.4  872.69   704.8  883.34
   733.8  896.51   791.8  920.19   811.2  927.11   820.9  929.87   840.2  933.64
#Mann= 3 , 0 , 0
       0     .06       0   475.7    .045       0   522.3     .08       0
Bank Sta=475.7,522.3
XS Rating Curve= 0 ,0
Exp/Cntr=0.3,0.1

Type RM Length L Ch R = 1 ,96248.7 ,48,48,48
XS GIS Cut Line= 4
     1911045.674      622395.574      1911399.84      622524.046
     1911497.063      622603.907     1911635.952      622723.699
#Sta/Elev= 30
       0  884.47    77.3  871.43    86.9  869.51    96.6  866.81   115.9  858.48
   173.9  829.47   212.5   807.9   222.2  803.05   241.5  793.88   251.2  790.18
   270.5   785.4   309.1  778.38   318.8  777.19   338.1  775.98   396.1  774.84
   405.8  773.26   415.5  769.63   425.1  765.12   434.8  763.11   444.5  763.75
   454.2   767.2   463.8  771.48   483.2  779.17   492.9  784.93   521.9  805.64
   570.1  838.28     657  895.17   666.7  901.14   676.3  904.86     686  904.93
#Mann= 3 , 0 , 0
       0     .05       0   415.5    .045       0   454.2     .08       0
Bank Sta=415.5,454.2
XS Rating Curve= 0 ,0
Exp/Cntr=0.3,0.1

Type RM Length L Ch R = 1 ,96200.7 ,113.8,112,110.2
XS GIS Cut Line= 4
     1911023.104      622438.977     1911377.271      622567.449
     1911474.493       622647.31     1911613.382      622767.102
#Sta/Elev= 30
       0  886.44      29  882.32    67.6  874.96    77.3  872.92    86.9  869.32
   135.2  843.03   212.5  805.03   241.5  791.58   251.2  787.88   260.8  784.89
   280.2  781.06   328.4  773.97   357.4  771.82   367.1  771.75   376.8  772.33
   386.4  771.73   396.1  768.86   405.8  764.46   415.5  763.04   425.1  764.38
   434.8  768.38   444.5  772.82   454.2  775.93   463.8   778.4   473.5  782.22
   483.2  787.82   647.4  893.33     657  896.64   666.7  896.33     686  889.78
#Mann= 3 , 0 , 0
       0     .05       0   396.1    .045       0   434.8     .08       0
Bank Sta=396.1,434.8
XS Rating Curve= 0 ,0
Exp/Cntr=0.3,0.1

Type RM Length L Ch R = 1 ,96088.6 ,252.3,254.8,257.4
XS GIS Cut Line= 4
     1911006.177      622503.936     1911275.275        622627.2
     1911388.122      622707.061     1911570.413      622797.339
#Sta/Elev= 30
       0  874.27    38.2  869.65    47.7  868.23    57.3  865.81    66.8  861.49
    76.4   856.1   171.9  800.37   181.4  795.26     191  790.73   200.5  787.08
   219.6  781.16   229.2  778.65   248.2   774.6   267.3  771.39   323.6   764.6
   342.1  762.62   351.3  762.82   360.5  764.03   369.7  767.06   397.4  776.95
   406.6  780.71   482.7  818.09   511.7  832.65   540.8  847.85   569.8  863.97
   598.9   881.3   608.6  885.63   618.3  886.97     628  885.55   637.6  882.76
#Mann= 3 , 0 , 0
       0     .05       0   323.6    .045       0   369.7     .08       0
Bank Sta=323.6,369.7
XS Rating Curve= 0 ,0
Exp/Cntr=0.3,0.1