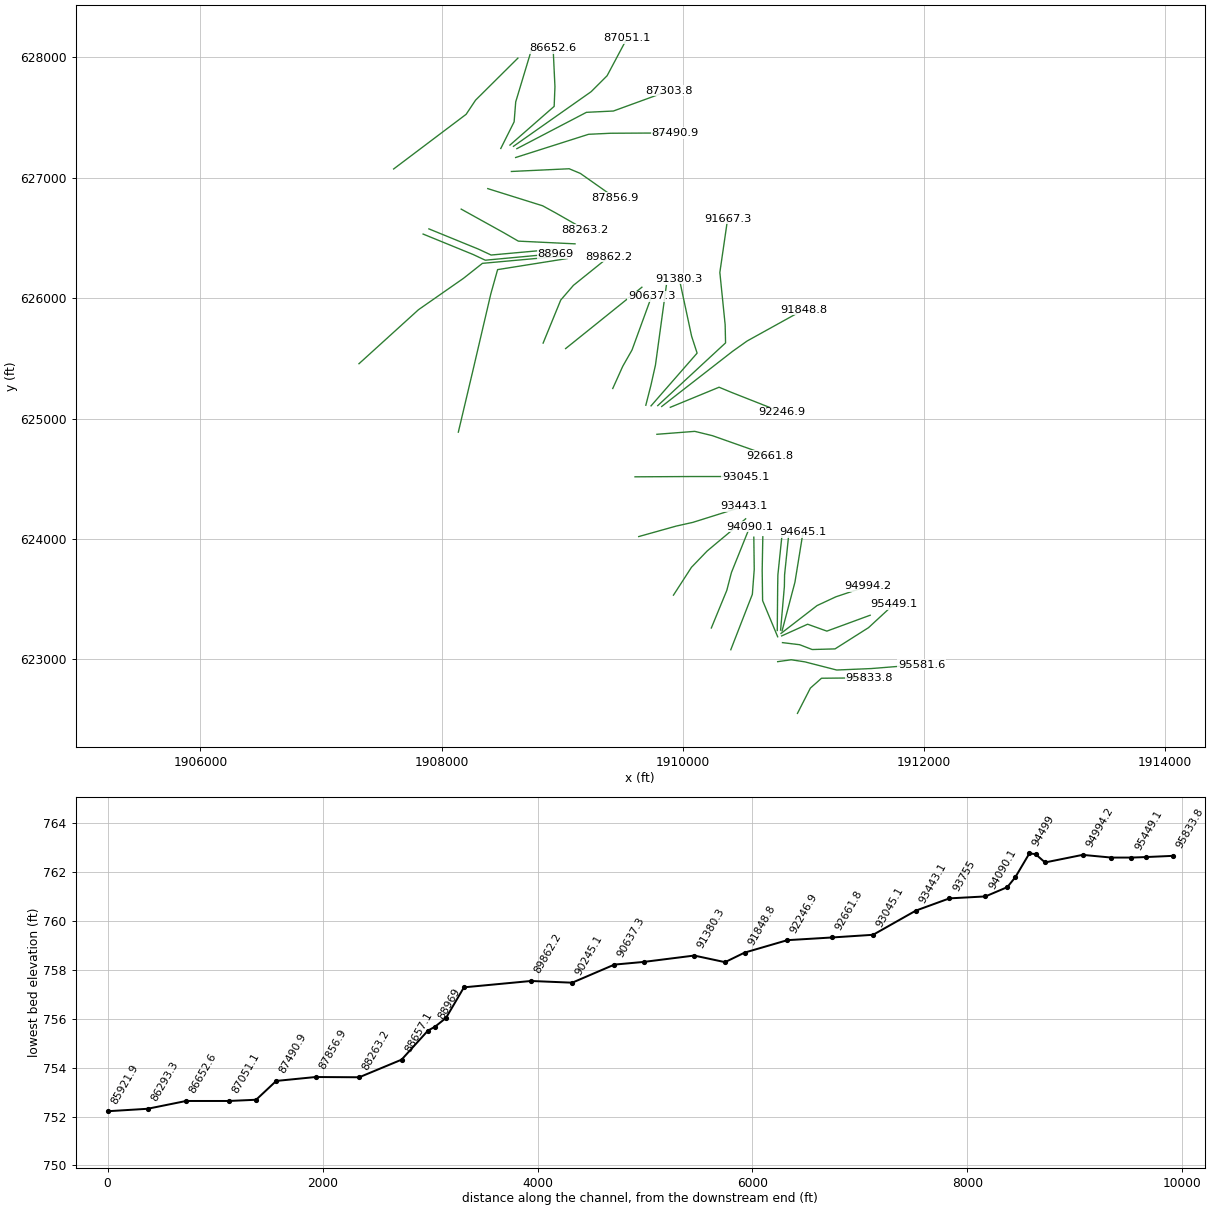
HEC-RAS study HenryFork.prj: HenryFork

--- HenryFork.g01 (geometry) --- (continued)

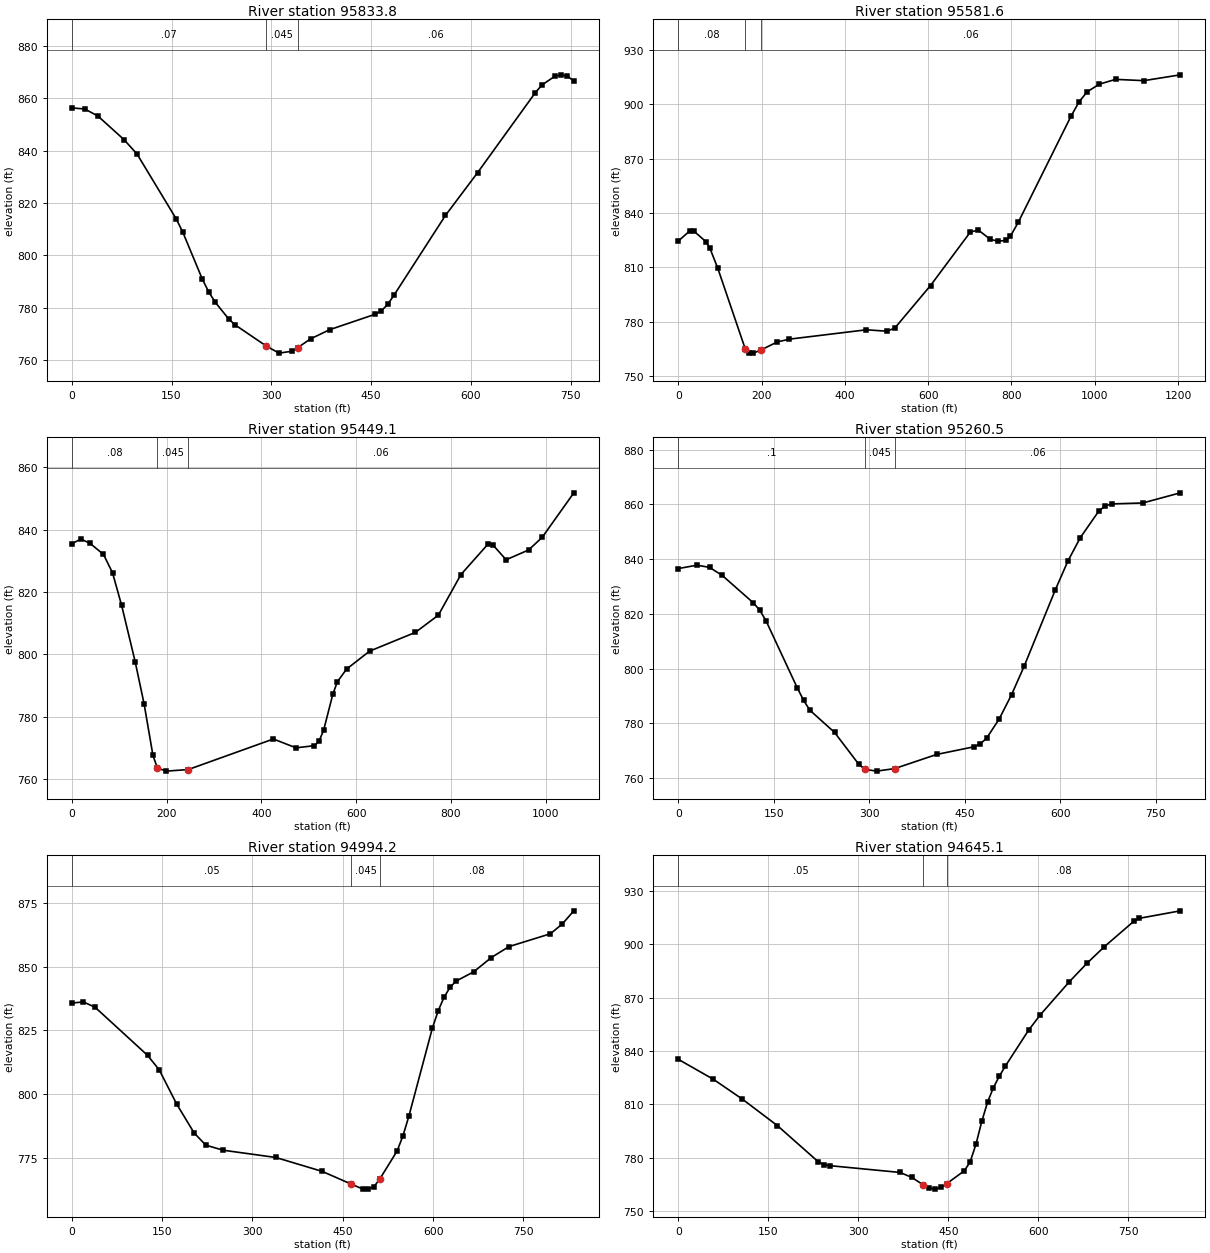
Type RM Length L Ch R = 1 ,95833.8 ,272.1,252.3,232
XS GIS Cut Line= 4
     1910952.358      622552.547     1911059.531      622762.439
     1911152.011      622844.214     1911547.844      622847.686
#Sta/Elev= 30
       0  856.26    19.6  855.84    39.3  853.15    78.6  844.14    98.2  838.63
   157.1  813.88   166.9  808.86   196.4  790.87   206.2   785.9     216  782.02
   235.7   775.8   245.2  773.52   292.6  765.36   311.6  762.67   330.6  763.37
   340.1  764.81   359.1  768.12   388.1  771.64   455.7  777.46   465.3  778.74
     475  781.24   484.6   784.8   561.9  815.21   610.2  831.53     697  862.05
   706.7  864.94     726  868.27   735.7  868.88   745.3   868.4     755  866.48
#Mann= 3 , 0 , 0
       0     .07       0   292.6    .045       0   340.1     .06       0
Bank Sta=292.6,340.1
XS Rating Curve= 0 ,0
Exp/Cntr=0.3,0.1

Type RM Length L Ch R = 1 ,95581.6 ,137.4,132.5,127.7
XS GIS Cut Line= 6
     1910788.295      622981.801     1910901.143      622997.426
      1911013.99      622980.065     1911277.879      622912.356
     1911564.623      622924.494      1911981.19       622958.11
#Sta/Elev= 30
       0  824.48    28.5  830.28      38  829.91    66.5  824.17      76  820.57
    94.9  809.52   160.7  765.08     171  762.77   180.5  762.62   199.6  764.46
   237.8  768.81     267  770.34   451.9  775.51   500.5  774.73   519.7  776.38
   605.8  799.96   701.4   829.5   720.6  830.57   749.3  825.46   768.4  824.38
   787.5  824.95   797.3  827.04   816.7  834.99     943  893.44   962.5  901.41
   981.9  906.96  1011.1  911.14    1050  913.81    1118  913.09  1205.5  916.31
#Mann= 3 , 0 , 0
       0     .08       0   160.7    .045       0   199.6     .06       0
Bank Sta=160.7,199.6
XS Rating Curve= 0 ,0
Exp/Cntr=0.3,0.1

Type RM Length L Ch R = 1 ,95449.1 ,188.1,188.5,189.5
XS GIS Cut Line= 6
     1910828.226      623139.787     1910970.587      623122.426
     1911074.754      623082.495      1911263.99      623087.703
     1911542.114      623264.148     1911752.023       623458.11
#Sta/Elev= 30
       0  835.46    19.1  836.98    38.2  835.65    66.9  832.07      86  826.18
   105.2  815.73   133.8  797.66   152.7   784.1   171.3  767.65   180.6  763.62
   199.2   762.6   245.7   763.1   425.4   772.9   473.3  770.06   512.1  770.77
   521.8  772.21   531.5  775.72   550.8  787.19   560.5  791.25   579.9   795.3
   628.3  801.04   725.2  807.08   773.6  812.59   821.3  825.62   878.4  835.37
     888  835.22   916.6  830.34   964.2   833.5   992.8  837.55  1059.5   851.8
#Mann= 3 , 0 , 0
       0     .08       0   180.6    .045       0   245.7     .06       0
Bank Sta=180.6,245.7
XS Rating Curve= 0 ,0
Exp/Cntr=0.3,0.1

Type RM Length L Ch R = 1 ,95260.5 ,248.4,266.3,283.5
XS GIS Cut Line= 4
     1910821.281      623195.342     1911036.559      623292.565
     1911196.281      623235.273     1911555.656      623367.217
#Sta/Elev= 30
       0  836.56    29.5  837.79    49.2  836.99    68.9  834.09   118.1  824.02
     128  821.38   137.8  817.54     187     793   196.8  788.51   206.7  784.85
   245.6  776.72   283.4  765.17   292.8  763.28   311.6   762.6   339.9  763.52
   405.9  768.69   464.8  771.49   474.6  772.56   484.4  774.62   504.1   781.6
   523.7  790.55   543.3  800.85   592.4  828.81     612  839.25   631.7  847.87
   661.1   857.7   670.9  859.39   680.8  860.16   729.8  860.51   788.7  864.21
#Mann= 3 , 0 , 0
       0      .1       0   292.8    .045       0   339.9     .06       0
Bank Sta=292.8,339.9
XS Rating Curve= 0 ,0
Exp/Cntr=0.3,0.1

Type RM Length L Ch R = 1 ,94994.2 ,329,349.1,371.2
XS GIS Cut Line= 4
     1910816.073      623216.176     1911114.684      623447.078
     1911270.934      623519.995     1911540.031      623610.273
#Sta/Elev= 30
       0  835.78    19.4   836.2    38.7  834.12   125.8  815.25   145.2  809.56
   174.2   796.1   203.2  784.76   222.6  779.97   251.6  777.98   338.8  775.14
   415.8  769.68   463.7  764.72   482.8  762.79   492.4  762.71     502  763.73
   511.6  766.72   540.3  777.72   549.9  783.63   559.7  791.29   598.8  825.94
   608.6  832.84   618.4  838.15   628.2  841.96     638  844.37   667.4  848.03
   696.7  853.65   726.1  857.94   794.6  862.96   814.2  866.74   833.7  871.98
#Mann= 3 , 0 , 0
       0     .05       0   463.7    .045       0   511.6     .08       0
Bank Sta=463.7,511.6
XS Rating Curve= 0 ,0
Exp/Cntr=0.3,0.1

Type RM Length L Ch R = 1 ,94645.1 ,83.5,89,92.3
XS GIS Cut Line= 3
     1910824.754      623237.009     1910931.506      623641.287
     1910998.445      624054.139
#Sta/Elev= 30
       0  835.42    58.3  824.22     107  812.97   165.3  798.08   233.4  777.74
   243.1  776.15   252.8  775.59   369.5  771.78     389  769.01   408.4  764.72
   418.1  762.94   427.9   762.4   437.6  763.32   447.3  765.47   476.5   772.7
   486.2  777.62     496  787.68   505.7  800.53   515.4  811.46   525.1  819.51
   534.8  825.87   544.6  831.41   583.5  851.71   602.9  860.33   651.6  879.06
   680.8  889.39   709.9  898.75   758.6  912.94   768.3  914.72   836.4  918.92
#Mann= 3 , 0 , 0
       0     .05       0   408.4    .045       0   447.3     .08       0
Bank Sta=408.4,447.3
XS Rating Curve= 0 ,0
Exp/Cntr=0.3,0.1

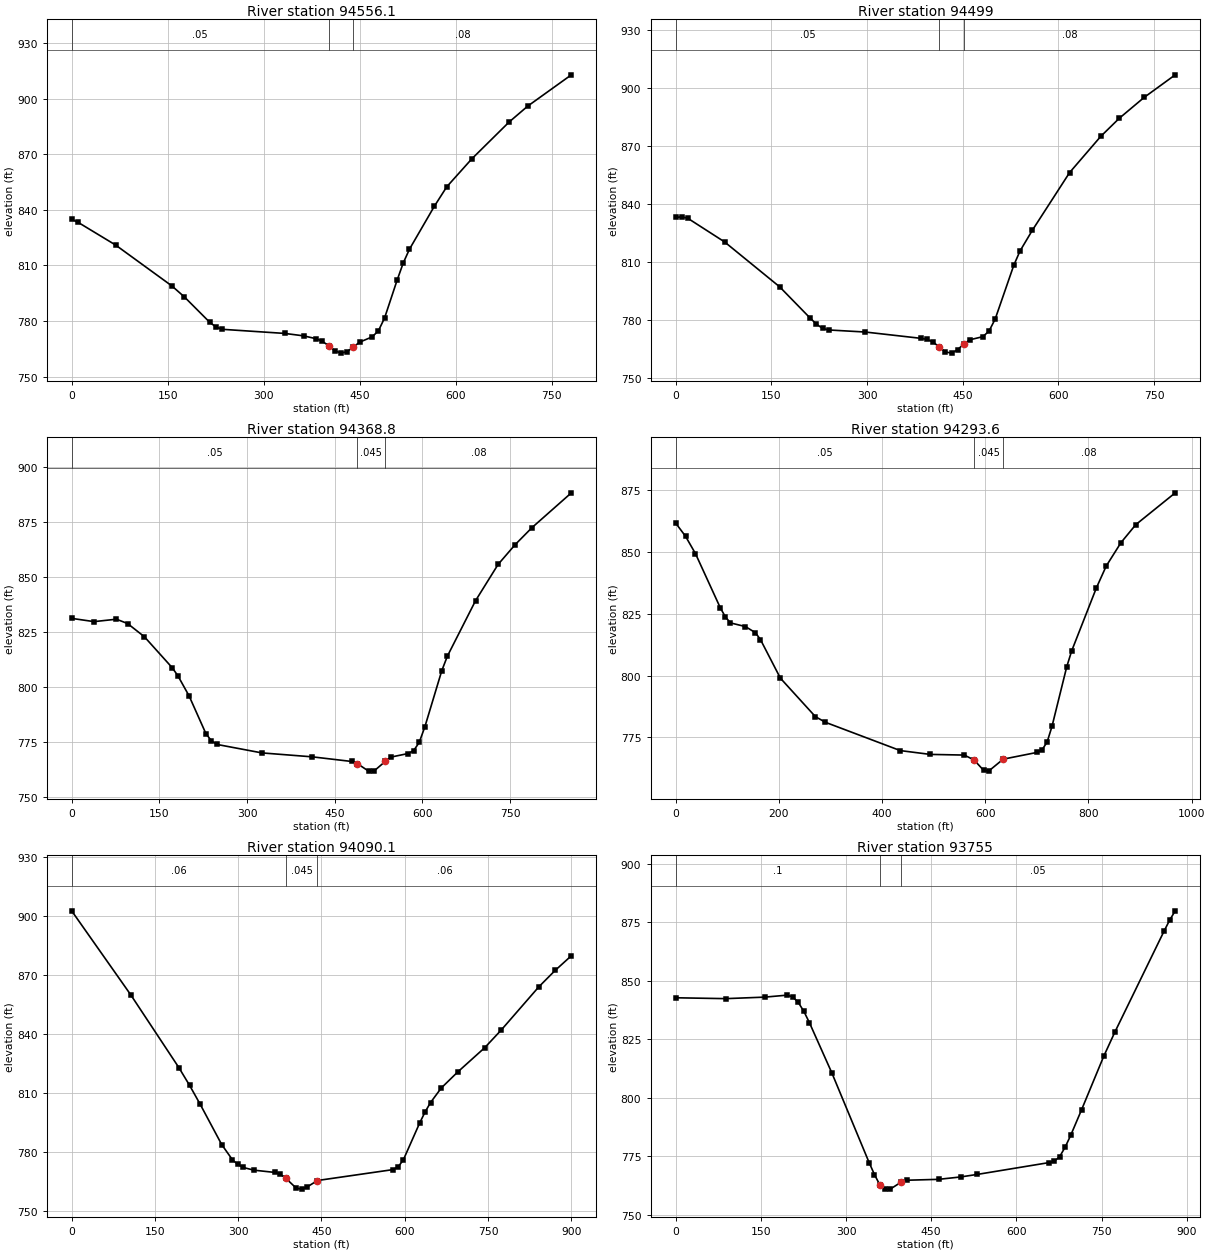
Type RM Length L Ch R = 1 ,94556.1 ,57.3,57.1,57
XS GIS Cut Line= 4
     1910812.601      623243.953     1910843.851      623605.065
     1910845.587      623702.287     1910878.573      624021.731
#Sta/Elev= 30
       0  834.89     9.8  833.31    68.6  821.04   156.7  798.95   176.3     793
   215.5  779.45   225.3  776.85   235.1  775.59   333.1  773.36   362.5  772.05
   381.9  770.52   391.6  769.14   401.4  766.77   411.1  764.07   420.8  762.74
   430.5  763.57   440.2  766.04     450  768.65   469.4  771.49   479.2  774.71
   488.9  781.65   508.4  801.95   518.1  811.35   527.8  818.76   566.8  841.98
   586.2  852.47   625.1  867.44   683.5  887.34   712.7  895.95   780.8   912.8
#Mann= 3 , 0 , 0
       0     .05       0   401.4    .045       0   440.2     .08       0
Bank Sta=401.4,440.2
XS Rating Curve= 0 ,0
Exp/Cntr=0.3,0.1

Type RM Length L Ch R = 1 ,94499   ,129.4,130.2,130.7
XS GIS Cut Line= 4
     1910784.823      623240.481     1910788.295      623605.065
     1910790.031      623702.287     1910823.018      624021.731
#Sta/Elev= 30
       0  832.92     9.6  833.25    19.2  832.52    76.8   820.3   163.1  797.08
   211.1  780.84   220.7  777.79   230.3  775.58   239.9  774.75   297.4  773.68
     384  770.44   393.8  769.91   403.5  768.53   413.2  765.93   422.9  763.39
   432.7  762.77   442.4  764.64   452.1  767.67   461.8  769.72   481.3  771.26
     491  774.05   500.8  780.33     530  808.19   539.7  815.54   559.2  826.36
   617.5  856.16   666.2  874.83   695.4  884.25   734.3  895.02     783   906.7
#Mann= 3 , 0 , 0
       0     .05       0   413.2    .045       0   452.1     .08       0
Bank Sta=413.2,452.1
XS Rating Curve= 0 ,0
Exp/Cntr=0.3,0.1

Type RM Length L Ch R = 1 ,94368.8 ,77.2,75.1,73
XS GIS Cut Line= 4
     1910788.295      623188.398     1910663.295      623488.745
     1910659.823      623738.745     1910665.031      624018.259
#Sta/Elev= 30
       0  831.17    38.3  829.69    76.6  830.79    95.7  828.82   124.4  822.83
   172.2  808.72   181.8  805.07   200.9  795.96   229.6  778.88   239.2  775.52
   248.8  773.91   325.3  770.08   411.9  768.28   479.2  766.18   488.8   765.2
     508   761.8   517.6  761.92   536.9  766.29   546.5  768.19   575.3  769.77
     585  771.09   594.6  774.83   604.3  781.95   633.2  807.41   642.8  814.02
     691  839.21   729.6  855.69   758.5  864.58   787.4  872.35   854.9  888.18
#Mann= 3 , 0 , 0
       0     .05       0   488.8    .045       0   536.9     .08       0
Bank Sta=488.8,536.9
XS Rating Curve= 0 ,0
Exp/Cntr=0.3,0.1

Type RM Length L Ch R = 1 ,94293.6 ,207.6,203.5,199.9
XS GIS Cut Line= 4
     1910399.406      623080.759     1910578.226      623540.828
     1910593.851      623747.426     1910590.379      624014.787
#Sta/Elev= 30
       0  861.74    19.4  856.32    38.7  849.29    87.1  827.26    96.8  823.69
   106.5  821.31   135.5  819.82   154.8  817.35   164.5  814.59   203.2  798.96
     271  783.42   290.4  781.13   435.5  769.69   493.6  768.15   559.5  767.88
   578.4  765.91   597.2  761.66   606.6  761.39   634.9  766.23   700.8  768.97
   710.3  770.05   719.9  773.11   729.4  779.47   758.1  803.67   767.6  810.02
   815.4  835.45   834.5   844.3   863.1  853.77   891.8  861.03   968.2  873.89
#Mann= 3 , 0 , 0
       0     .05       0   578.4    .045       0   634.9     .08       0
Bank Sta=578.4,634.9
XS Rating Curve= 0 ,0
Exp/Cntr=0.3,0.1

Type RM Length L Ch R = 1 ,94090.1 ,346.3,335.2,323
XS GIS Cut Line= 4
     1910237.948      623261.315      1910366.42      623573.815
     1910404.615      623721.384     1910557.393      624101.592
#Sta/Elev= 30
       0  902.56   106.2  859.94   193.1  822.83   212.4   813.8   231.7  804.07
   270.3  783.67   289.6  775.94   299.3  773.57   308.9  772.04   328.2  770.66
   366.5  769.49     376  768.52   385.5  766.58   404.6  761.49   414.1  761.01
   423.6  762.01   442.7  765.39   578.1  770.91   587.9  772.21   597.6  775.99
   626.9  794.68   636.6  800.25   646.4  805.04   665.9  812.49   695.2  820.54
     744  832.94   773.2  841.75   841.5  863.91   870.8  872.22   900.1  879.72
#Mann= 3 , 0 , 0
       0     .06       0   385.5    .045       0   442.7     .06       0
Bank Sta=385.5,442.7
XS Rating Curve= 0 ,0
Exp/Cntr=0.3,0.1

Type RM Length L Ch R = 1 ,93755   ,325.1,311.9,298.8
XS GIS Cut Line= 4
     1909923.712      623533.884     1910073.018      623764.787
     1910203.226      623900.203      1910522.67      624167.565
#Sta/Elev= 30
       0  842.71    88.4  842.34   157.1  842.99   196.4  843.83   206.2  843.08
     216  840.74   225.9  836.89   235.7  832.03     275  810.66   340.7  772.28
   350.1  767.16   359.5  762.76   368.9  760.93   378.3     761   397.1  763.93
   406.5  764.73   462.8  765.11   501.6  766.13   530.6   767.2   656.6  772.24
   666.3  772.77     676  774.82   685.6  778.84   695.3  783.85   714.7  794.93
   753.5  817.67   772.8  827.87     860  871.33   869.7  875.95   879.4  879.87
#Mann= 3 , 0 , 0
       0      .1       0   359.5    .045       0   397.1     .05       0
Bank Sta=359.5,397.1
XS Rating Curve= 0 ,0
Exp/Cntr=0.3,0.1

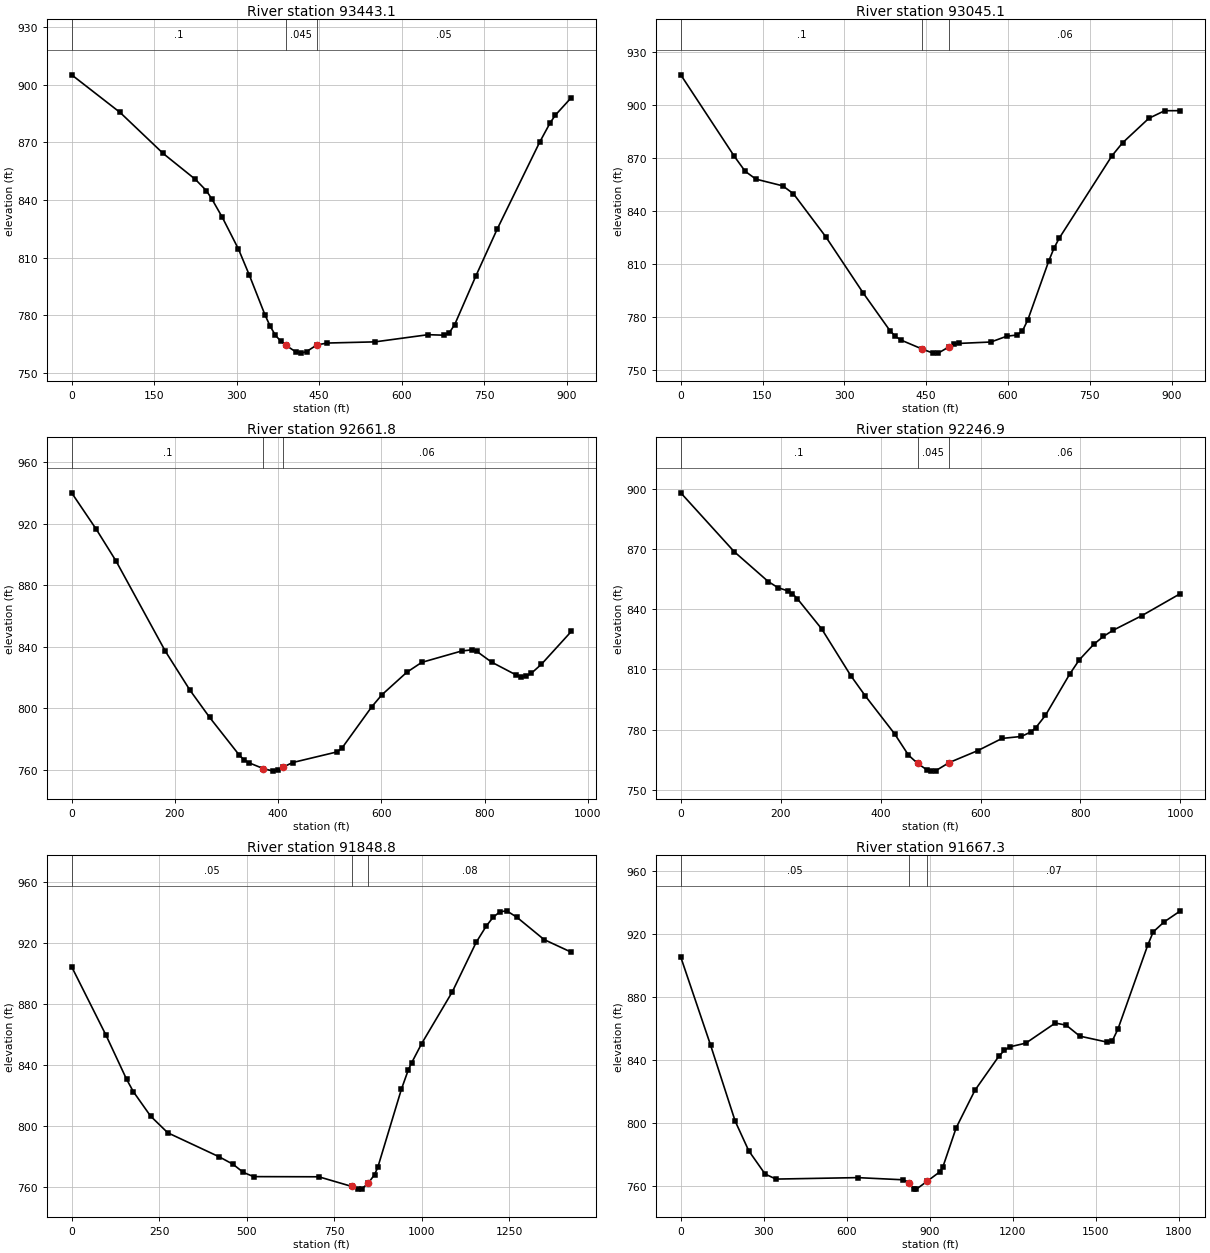
Type RM Length L Ch R = 1 ,93443.1 ,402.8,398,393
XS GIS Cut Line= 4
     1909635.518      624019.995      1909946.58      624107.042
      1910085.17      624138.051     1910508.319      624271.151
#Sta/Elev= 30
       0  905.17    88.1  885.59   166.4  864.27   225.1  850.77   244.7     845
   254.5  840.83   274.1  830.97   303.4   814.5     323  801.07   351.4  780.44
   360.9  774.46   370.4  769.79   379.8  766.78   389.3  764.58   408.2  760.94
   417.7  760.43   427.2  761.25   446.1  764.72     465  765.68   551.8  766.29
   648.2  770.02   677.2  769.75   686.8  771.08   696.5  775.25     735  800.54
   773.6   824.8   850.8  870.01     870  880.15   879.7  884.25   908.6  893.32
#Mann= 3 , 0 , 0
       0      .1       0   389.3    .045       0   446.1     .05       0
Bank Sta=389.3,446.1
XS Rating Curve= 0 ,0
Exp/Cntr=0.3,0.1

Type RM Length L Ch R = 1 ,93045.1 ,388.8,383.3,377.9
XS GIS Cut Line= 3
     1909604.729      624515.952     1910067.282      624518.341
     1910520.948      624518.352
#Sta/Elev= 30
       0  916.86    98.4  870.68   118.1  862.29   137.8  857.86     187  854.06
   206.7  849.56   265.7  825.34   334.6  793.42   383.8  772.05   393.7  768.91
   403.5  766.87   442.9  761.72   462.6  759.44   472.2  759.46   491.5  762.96
   501.2  764.51   510.8  764.94   568.7  765.73   597.7  769.01     617   769.7
   626.6  772.07   636.3  778.18   674.9  811.68   684.6  818.99   694.2  824.57
   790.7  871.09     810  878.37   858.3  892.26   887.3  896.56   916.2  896.59
#Mann= 3 , 0 , 0
       0      .1       0   442.9    .045       0   491.5     .06       0
Bank Sta=442.9,491.5
XS Rating Curve= 0 ,0
Exp/Cntr=0.3,0.1

Type RM Length L Ch R = 1 ,92661.8 ,418.4,414.9,411.2
XS GIS Cut Line= 4
     1909786.559      624868.953     1910100.795      624893.259
     1910247.019      624857.447     1910720.587      624690.134
#Sta/Elev= 30
       0  940.04    47.8  916.32      86  895.76   181.5   837.2   229.2  811.89
   267.4  794.18   324.6  769.79     334  766.62   343.4  764.77   371.6  760.93
   390.4  759.33   399.9  759.98   409.3  761.89   428.1   764.9     514   771.8
   523.7   774.3   581.6   801.2   600.9  808.85   649.2   823.5   678.2  829.94
   755.5  837.33   774.8  838.07   784.5  837.19   813.4  830.14   861.7  821.66
   871.4  820.65     881  821.09   890.7  822.92     910  828.69     968  850.04
#Mann= 3 , 0 , 0
       0      .1       0   371.6    .045       0   409.3     .06       0
Bank Sta=371.6,409.3
XS Rating Curve= 0 ,0
Exp/Cntr=0.3,0.1

Type RM Length L Ch R = 1 ,92246.9 ,374.8,398.1,421.4
XS GIS Cut Line= 4
      1909897.67      625092.912     1910302.184      625259.578
     1910402.897       625217.66     1910824.754      625051.245
#Sta/Elev= 30
       0  898.25     107  868.84     175  853.95   194.4  850.89   213.9   849.3
   223.6  847.89   233.3  845.36     282  830.29   340.3  806.92   369.4  796.78
   427.8  777.93   455.7  767.23   473.9  763.11     492  759.96   501.1  759.22
   510.2  759.42   537.5  763.52   594.8   769.5   643.1  775.56   681.7  776.54
     701  778.81   710.6  780.93   729.9  787.07   778.2  807.57   797.5  814.77
   826.4  822.52   845.7  826.48     865  829.54   922.9  836.89  1000.1  847.92
#Mann= 3 , 0 , 0
       0      .1       0   473.9    .045       0   537.5     .06       0
Bank Sta=473.9,537.5
XS Rating Curve= 0 ,0
Exp/Cntr=0.3,0.1

Type RM Length L Ch R = 1 ,91848.8 ,159.6,181.5,202.9
XS GIS Cut Line= 4
      1909826.49      625099.856     1910414.226      625557.488
     1910534.823      625643.259     1911001.837       625901.94
#Sta/Elev= 30
       0  904.33      98  859.54   156.8  830.67   176.4  822.45   225.4  806.53
   274.4  795.61   421.4  779.85   460.7  775.01   490.1  769.68   519.5   766.9
   705.7  766.79   800.4  760.44   818.9  758.71   828.1  758.82   846.6  762.49
   865.1  768.27   874.4  773.14   941.4  823.98   960.8  836.46   970.5  841.29
   999.6  854.06    1087  887.91    1155  920.25  1184.1  931.03  1203.5  936.71
  1222.9  940.32  1242.3  940.94  1271.4  936.73  1349.1  922.11  1426.8  913.85
#Mann= 3 , 0 , 0
       0     .05       0   800.4    .045       0   846.6     .08       0
Bank Sta=800.4,846.6
XS Rating Curve= 0 ,0
Exp/Cntr=0.3,0.1

Type RM Length L Ch R = 1 ,91667.3 ,280.5,287,293.7
XS GIS Cut Line= 5
     1909793.504      625106.801     1910356.004      625627.634
     1910352.531      625778.676     1910308.591      626212.024
     1910373.551      626659.499
#Sta/Elev= 30
       0  905.48   108.1  849.44   196.6  801.43   245.7  782.62   304.7  767.89
     344  764.69   638.8  765.62   804.4  764.23   823.2  762.32   842.1  758.62
   851.6  758.32   889.4  763.21     937  769.42   946.7  772.21   995.1  797.21
  1062.9  821.01    1150  842.77  1169.3  846.25  1188.7  848.55  1246.8   850.9
  1353.2  863.64  1392.6  862.31  1441.7  855.35    1540  851.56  1559.7  852.56
  1579.3  859.68  1687.5  913.16  1707.1  921.44  1746.4  927.77  1805.4  934.81
#Mann= 3 , 0 , 0
       0     .05       0   823.2    .045       0   889.4     .07       0
Bank Sta=823.2,889.4
XS Rating Curve= 0 ,0
Exp/Cntr=0.3,0.1

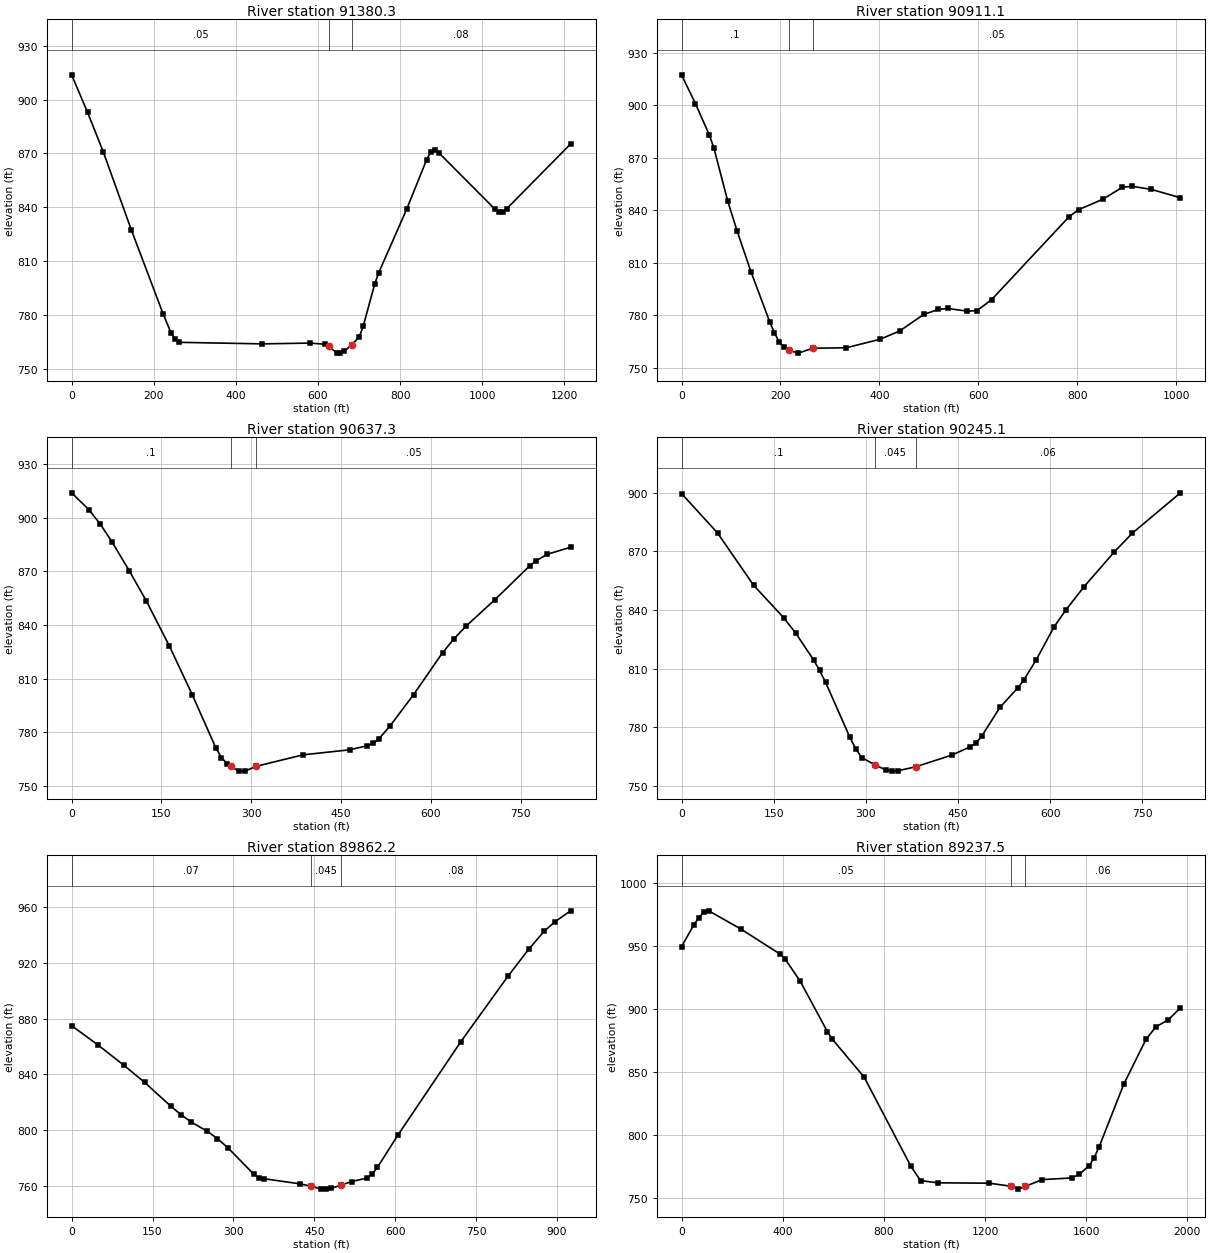
Type RM Length L Ch R = 1 ,91380.3 ,481.2,469.2,457
XS GIS Cut Line= 4
     1909737.948      625105.065     1910119.893      625542.565
      1910074.34      625683.055     1909972.323      626158.884
#Sta/Elev= 30
       0  913.89    38.7  893.02    77.4  870.72   145.2   827.5   222.6  780.63
     242  769.94   251.7  766.35   261.3  764.62   464.6  763.76   580.8  764.19
   617.7  763.55   626.9  762.32   645.4  758.76   654.6  758.59   663.8  759.54
   682.3  763.26   700.8  767.85     710  773.47   738.2  797.21   747.9  803.47
     816  838.93   864.7   866.6   874.4  870.83   884.2  871.92   893.9  870.46
  1030.2  839.11  1039.9   837.5  1049.6   837.5  1059.4  839.14  1215.1  875.29
#Mann= 3 , 0 , 0
       0     .05       0   626.9    .045       0   682.3     .08       0
Bank Sta=626.9,682.3
XS Rating Curve= 0 ,0
Exp/Cntr=0.3,0.1

Type RM Length L Ch R = 1 ,90911.1 ,280.2,273.8,267.1
XS GIS Cut Line= 4
     1909694.545      625110.273     1909736.212      625273.467
     1909774.406      625443.606     1909864.684      626103.328
#Sta/Elev= 30
       0  917.39    28.1  900.96    56.1   883.1    65.5   875.5    93.6  845.08
   112.3   828.2   140.4  804.86   178.1  776.36   187.8  769.92   197.5  764.79
   207.2  761.72   216.9     760   236.2  758.33   265.3  761.12   333.1  761.39
   401.6  766.28   440.7  770.94   489.7  780.43   519.1   783.3   538.6  783.84
   577.8  782.31   597.4  782.63   626.8  788.89   783.4  836.26     803  840.34
     852  846.32   891.2  853.13   910.8  853.69   949.9   851.9  1008.7  847.14
#Mann= 3 , 0 , 0
       0      .1       0   216.9    .045       0   265.3     .05       0
Bank Sta=216.9,265.3
XS Rating Curve= 0 ,0
Exp/Cntr=0.3,0.1

Type RM Length L Ch R = 1 ,90637.3 ,400.7,392.2,383.7
XS GIS Cut Line= 4
      1909420.24      625249.162     1909502.998      625433.122
     1909579.962      625568.606     1909743.059      626015.905
#Sta/Elev= 30
       0  913.92    28.8  904.53      48  896.37    67.2   886.6    96.1  870.45
   124.9  853.38   163.3  828.24   201.7  800.87   240.7  771.39   250.4   765.8
   260.2  762.18   265.8  760.84   279.6  758.26   289.4  758.22   308.8  760.94
   386.7  767.34   464.4  770.14   493.6  772.41   503.3  773.68     513   776.1
   532.4  783.67   571.3  800.99   619.9  824.56   639.3  832.42   658.8  839.28
   707.3  854.18   765.6  873.14   775.3  875.73   794.8  879.58   833.6  883.45
#Mann= 3 , 0 , 0
       0      .1       0   265.8    .045       0   308.8     .05       0
Bank Sta=265.8,308.8
XS Rating Curve= 0 ,0
Exp/Cntr=0.3,0.1

Type RM Length L Ch R = 1 ,90245.1 ,378.6,382.9,386.6
XS GIS Cut Line= 3
     1909029.181      625580.325     1909280.519      625782.364
      1909661.88      626089.602
#Sta/Elev= 30
       0  899.64    58.6  879.46   117.3  852.68   166.1   836.1   185.7  828.25
     215  814.43   224.8  809.03   234.5  802.96   273.6  775.13   283.4  769.01
   293.2  764.45     315  760.67   332.3  758.15   342.1  757.48   351.9  757.64
   381.2  759.71     440  765.68   469.4  769.86   479.2  771.78     489  775.57
   518.4  790.14   547.8  800.27   557.5  804.28   577.1   814.3   606.5  831.37
   626.1   840.2   655.5  852.02   704.5  869.73   733.8  879.34   812.2     900
#Mann= 3 , 0 , 0
       0      .1       0     315    .045       0   381.2     .06       0
Bank Sta=315,381.2
XS Rating Curve= 0 ,0
Exp/Cntr=0.3,0.1

Type RM Length L Ch R = 1 ,89862.2 ,614.6,624.6,634.5
XS GIS Cut Line= 4
     1908842.549      625625.898     1908988.784      625983.495
     1909094.285      626105.499     1909388.269      626342.195
#Sta/Elev= 30
       0  874.94    48.3  861.26    96.6  846.62   135.2  834.24   183.5  817.25
   202.8  811.02   222.2  805.65   251.1  799.16   270.4  793.82   289.8  787.23
     338  768.16   347.7   765.9   357.4  764.99   424.3   761.3   443.3  759.68
   462.2  757.67   471.7  757.55   481.2  758.08   500.2  760.51   519.2  762.99
   547.6  765.52   557.3  768.24     567   773.2   605.7  796.77   721.8  863.54
   808.9   910.4   847.6  929.89   876.7  942.98     896  949.52   925.1  957.43
#Mann= 3 , 0 , 0
       0     .07       0   443.3    .045       0   500.2     .08       0
Bank Sta=443.3,500.2
XS Rating Curve= 0 ,0
Exp/Cntr=0.3,0.1

Type RM Length L Ch R = 1 ,89237.5 ,181,166.6,152.3
XS GIS Cut Line= 5
     1908139.176      624886.929     1908260.699      625400.819
     1908408.521      626033.884     1908464.945      626235.707
      1909043.07      626327.721
#Sta/Elev= 30
       0  949.64    48.9     967    68.4   972.5      88   976.9   107.6  978.04
   234.7   963.6   391.2  943.56   410.7  939.53   469.4   922.2   576.6   882.3
     596  876.28   722.1  846.15   906.5  775.59   945.3  764.06  1013.2  762.29
  1216.3  762.01    1302  759.62  1330.6  757.29  1359.1  759.47  1426.8  764.84
  1543.8  766.17  1573.1  769.02  1612.1  775.97  1631.6   782.1  1651.2  790.69
  1748.7  840.43  1836.5  875.99  1875.6  885.96  1924.3  891.51  1973.1  901.09
#Mann= 3 , 0 , 0
       0     .05       0    1302    .045       0  1359.1     .06       0
Bank Sta=1302,1359.1
XS Rating Curve= 0 ,0
Exp/Cntr=0.3,0.1

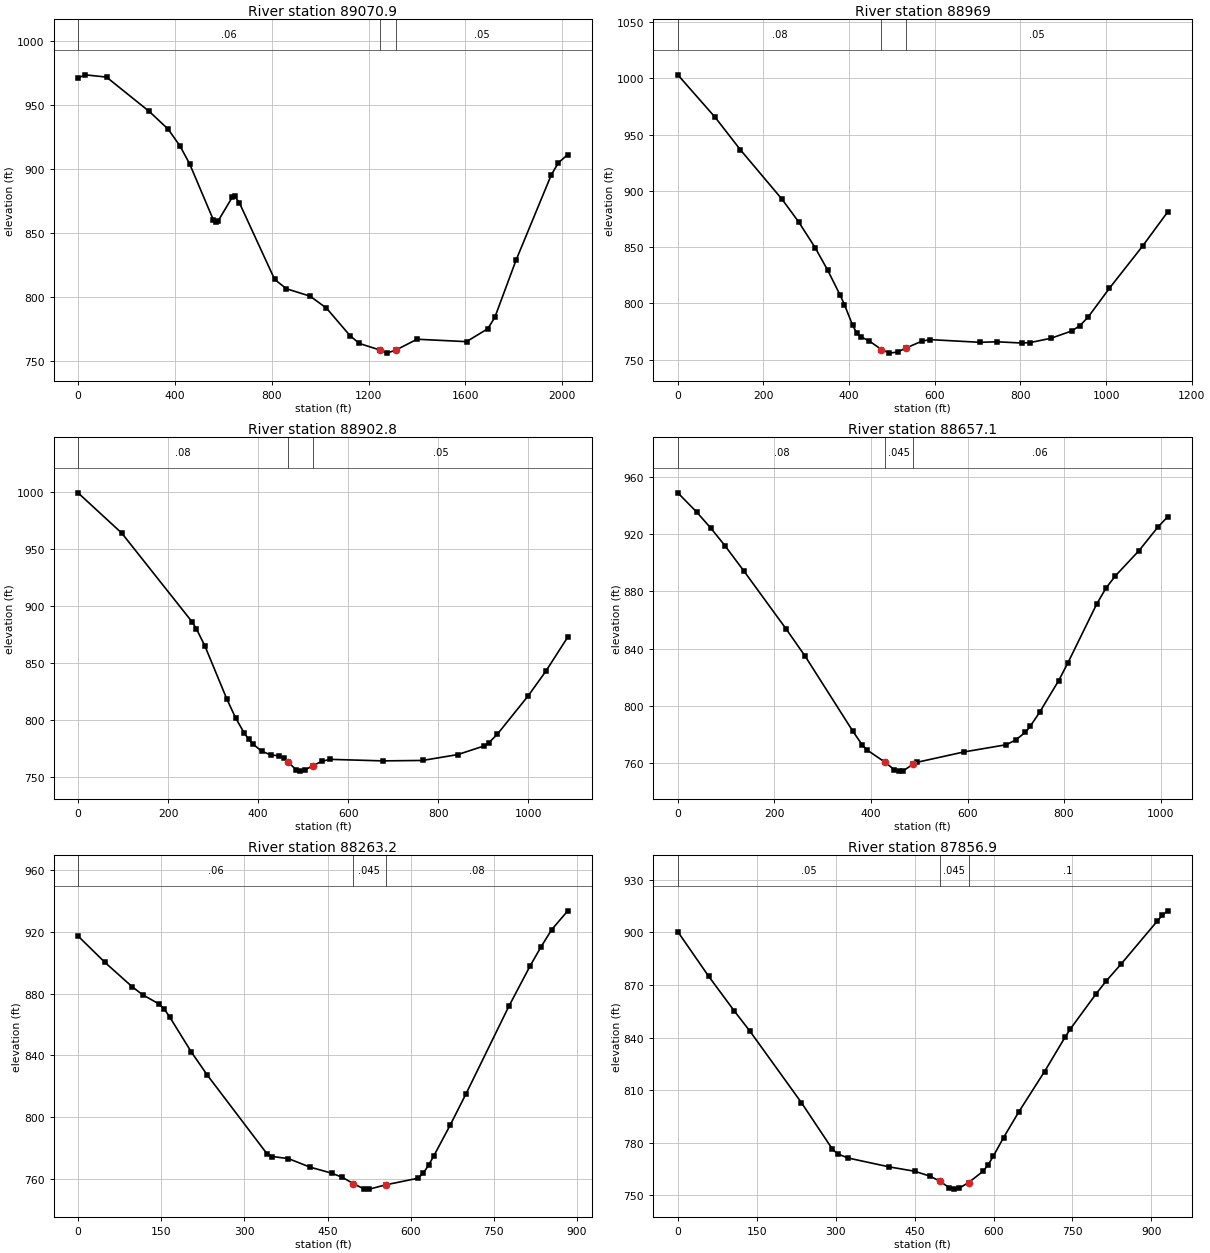
Type RM Length L Ch R = 1 ,89070.9 ,126.9,101.9,75.3
XS GIS Cut Line= 5
     1907314.957      625454.637      1907808.36      625902.736
     1908182.827      626164.092     1908339.077       626287.79
     1909036.559      626351.158
#Sta/Elev= 30
       0  970.79    29.4  973.24   117.6  971.47     294  944.69   372.5  930.78
   421.5  917.59   460.7  903.86   558.7  860.13   568.5  858.04   578.3   859.1
   637.1  877.72   646.9  878.44   666.5  873.35   812.2  813.52   860.8  806.28
     958  800.53    1026  791.19  1123.2  769.72  1161.1  763.64  1246.5  758.49
    1275  756.04    1313  758.45  1400.3  766.88  1604.5     765  1692.1  775.05
  1721.3  783.85  1808.8  828.44  1954.7  895.18  1983.9  904.56  2022.8  911.03
#Mann= 3 , 0 , 0
       0     .06       0  1246.5    .045       0    1313     .05       0
Bank Sta=1246.5,1313
XS Rating Curve= 0 ,0
Exp/Cntr=0.3,0.1

Type RM Length L Ch R = 1 ,88969   ,66.3,66.2,66.8
XS GIS Cut Line= 4
     1907846.889      626530.846     1908260.952      626361.575
     1908362.948      626313.832     1908944.111      626368.042
#Sta/Elev= 30
       0 1003.18    87.5  965.24   145.9   936.6   243.1  892.64     282  872.48
   320.9  849.35   350.1  829.33   379.2  807.11     389  798.86   408.4  780.31
   418.2  773.27   427.9  770.08   447.3  766.43   475.5  758.86   494.2  755.68
     513  756.65   531.8  760.03   569.7  766.31   589.1   767.7   705.9  765.29
   744.8  765.77   803.2  764.67   822.6  765.06   871.2  768.88   919.9  775.39
   939.3  780.24   958.8  788.09  1007.4  813.16  1085.3  850.89  1143.6  881.12
#Mann= 3 , 0 , 0
       0     .08       0   475.5    .045       0   531.8     .05       0
Bank Sta=475.5,531.8
XS Rating Curve= 0 ,0
Exp/Cntr=0.3,0.1

Type RM Length L Ch R = 1 ,88902.8 ,247.3,245.7,243.5
XS GIS Cut Line= 4
     1907895.066      626573.815     1908309.129      626404.544
     1908411.125      626356.801     1908937.167        626404.5
#Sta/Elev= 30
       0  999.52    97.2  964.17   252.8  886.69   262.6  880.56     282  865.16
   330.6  818.73   350.1  802.18   369.5  788.74   379.2  783.44     389  779.08
   408.4  772.94   427.9  769.77   447.3  768.89   456.7  767.13   466.1  763.66
   484.9  756.58   494.2  755.52   503.6  756.37   522.4  760.44   541.2  764.04
   559.9  765.84   677.3  764.51   765.4  764.88   843.6  770.02   902.3  777.61
   912.1  780.16   931.6  787.89  1000.1  821.52  1039.2  843.02  1088.1  873.08
#Mann= 3 , 0 , 0
       0     .08       0   466.1    .045       0   522.4     .05       0
Bank Sta=466.1,522.4
XS Rating Curve= 0 ,0
Exp/Cntr=0.3,0.1

Type RM Length L Ch R = 1 ,88657.1 ,393.1,393.9,396.2
XS GIS Cut Line= 4
     1908162.861      626737.834     1908513.556      626543.389
      1908636.82      626472.209     1909107.306      626449.639
#Sta/Elev= 30
       0  948.81    39.1  935.37    68.5  924.08    97.8   911.8   136.9  894.17
     225  853.36   264.1  834.45   361.9  782.56   381.4   772.9   391.2  769.28
   429.5  760.49   448.4   755.3   457.9  754.33   467.4  754.68   486.4  758.97
   495.9  760.54   592.4  767.72   680.7   772.8   700.3  776.26     720  781.49
   729.8  785.59   749.4  795.46   788.7   817.5   808.3  830.23   867.2  870.82
   886.8  882.24   906.4  890.82   955.5   908.5   994.7  925.03  1014.4  931.97
#Mann= 3 , 0 , 0
       0     .08       0   429.5    .045       0   486.4     .06       0
Bank Sta=429.5,486.4
XS Rating Curve= 0 ,0
Exp/Cntr=0.3,0.1

Type RM Length L Ch R = 1 ,88263.2 ,404.4,406.3,406.3
XS GIS Cut Line= 4
     1908383.347      626907.973     1908838.209      626765.611
      1908949.32      626704.848     1909192.375      626565.959
#Sta/Elev= 30
       0  917.22    48.6  900.14    97.3  884.53   116.7   879.2   145.9  873.34
   155.6  869.95   165.4  864.82   204.3  842.26   233.4  827.18   340.4  776.63
   350.2   774.7   379.4  773.34   418.3  767.83   457.2  763.96   476.6  761.23
   496.1  757.24   515.6  753.73   525.3  753.61   554.6  756.36   612.9  760.64
   622.6  763.91   632.2  769.12   641.9  775.29   670.8  794.78   699.8  815.29
     777  871.84   815.6   898.1   834.9  910.18   854.2  921.36   883.2   933.5
#Mann= 3 , 0 , 0
       0     .06       0   496.1    .045       0   554.6     .08       0
Bank Sta=496.1,554.6
XS Rating Curve= 0 ,0
Exp/Cntr=0.3,0.1

Type RM Length L Ch R = 1 ,87856.9 ,355.5,366,375.9
XS GIS Cut Line= 4
     1908579.528      627050.334     1909058.695      627072.903
      1909151.37      627034.188     1909438.102      626832.322
#Sta/Elev= 30
       0  900.37    58.7  874.92   107.7  855.05   137.1  843.65     235  802.89
   293.7  776.45   303.5  773.75   323.1  771.39   401.4  766.32   450.3   763.8
   479.7  760.96     498  758.14   516.2  754.36   525.4  753.62   534.5  754.12
   552.7  757.38   580.1  763.78   589.9  767.56   599.6  772.39   619.1  783.03
   648.3  797.78     697  820.66     736  840.26   745.7  844.79   794.4  864.75
   813.9  872.19   843.1  882.15   911.3  906.46   921.1  909.84   930.8  912.28
#Mann= 3 , 0 , 0
       0     .05       0     498    .045       0   552.7      .1       0
Bank Sta=498,552.7
XS Rating Curve= 0 ,0
Exp/Cntr=0.3,0.1

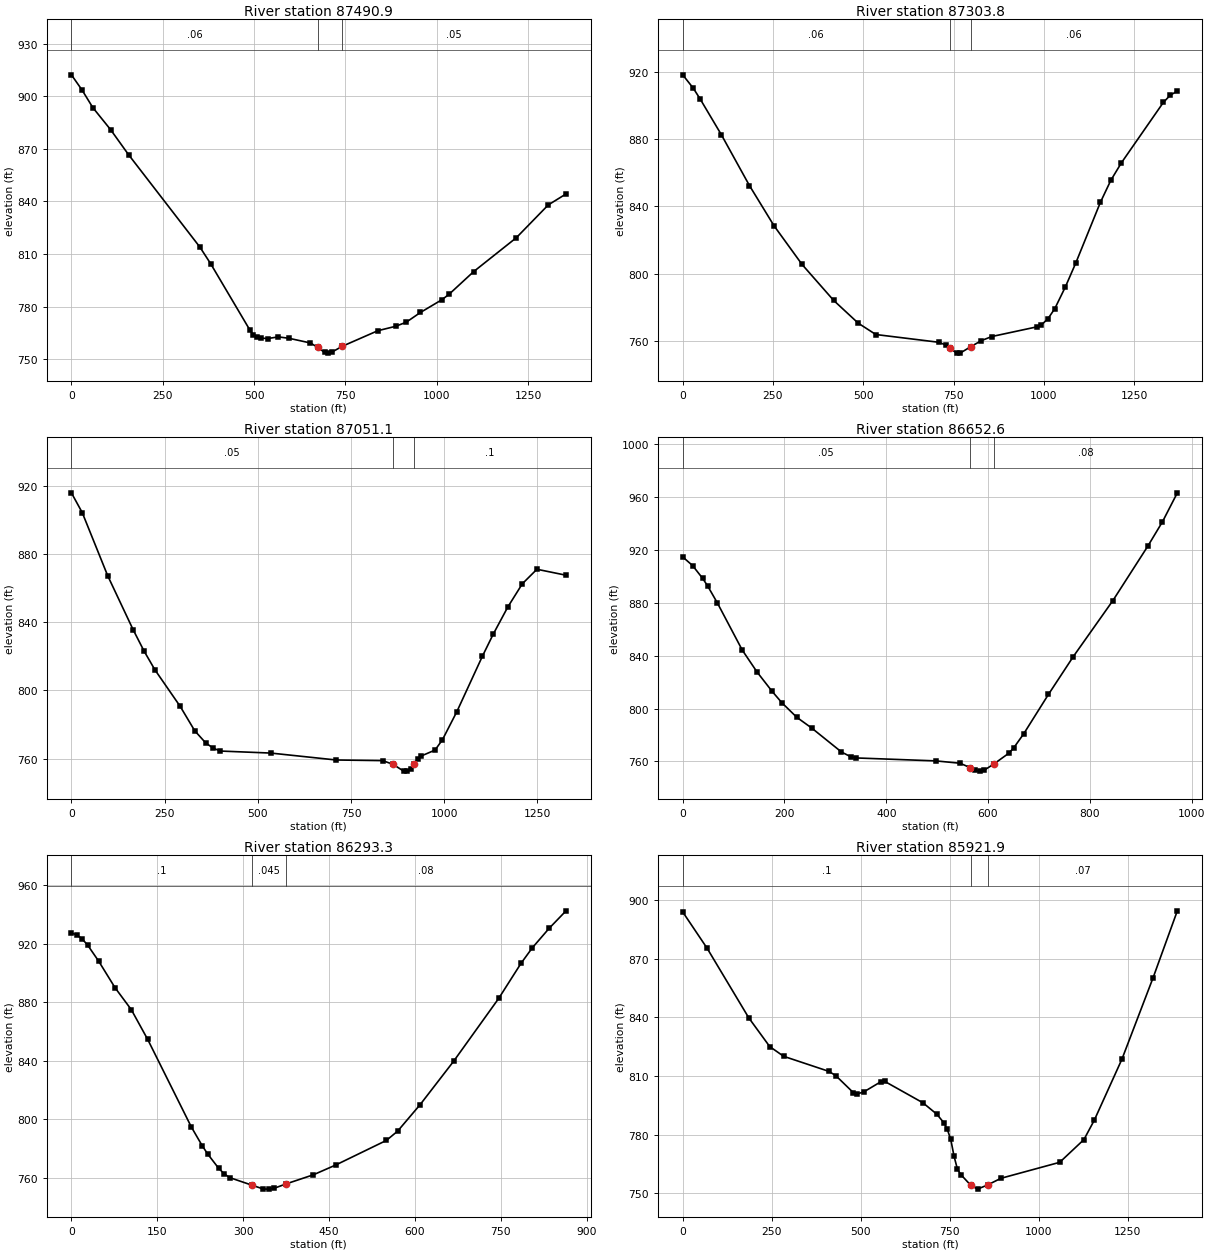
Type RM Length L Ch R = 1 ,87490.9 ,187.3,187.1,187.3
XS GIS Cut Line= 4
     1908614.684      627166.219     1909219.719      627358.927
     1909403.747      627367.608     1909938.469      627370.212
#Sta/Elev= 30
       0  912.18    29.3  903.47    58.6   893.5   107.5  880.86   156.3  866.68
   351.7  813.93     381  804.52   488.4  766.67   498.2  763.84     508  762.43
   517.8  762.04   537.3  761.78   566.6  762.72   595.9  761.91   654.4  759.25
   673.8  756.76   693.2  753.84   702.9  753.46   712.6  753.99   741.6  757.38
   838.7  766.24   887.3  768.75   916.4  771.07   955.3  776.64  1013.7  783.87
  1033.1   786.9  1101.2  799.98  1217.8  819.27  1305.3  837.99  1353.9  844.25
#Mann= 3 , 0 , 0
       0     .06       0   673.8    .045       0   741.6     .05       0
Bank Sta=673.8,741.6
XS Rating Curve= 0 ,0
Exp/Cntr=0.3,0.1

Type RM Length L Ch R = 1 ,87303.8 ,236.1,252.6,269.2
XS GIS Cut Line= 4
     1908624.667       627239.57     1909201.924      627541.219
     1909425.448       627552.07     1909889.858      627721.341
#Sta/Elev= 30
       0  918.26    29.2  910.34    48.6  903.79   106.9  882.68   184.7  852.41
   252.8  828.47   330.5  805.43     418  784.04   486.1  770.49   534.7  763.76
   709.7  759.13   729.2  757.41   738.9  755.63   758.4  752.74   768.1  752.69
   797.3   756.5   826.5  760.09   855.6  762.56   981.7  768.37   991.4  769.21
  1010.8  773.02  1030.2  779.18  1059.3  792.02  1088.3  806.34  1156.2  842.31
  1185.2  855.47  1214.3  865.84  1330.6  901.82    1350  906.18  1369.4  908.57
#Mann= 3 , 0 , 0
       0     .06       0   738.9    .045       0   797.3     .06       0
Bank Sta=738.9,797.3
XS Rating Curve= 0 ,0
Exp/Cntr=0.3,0.1

Type RM Length L Ch R = 1 ,87051.1 ,382.3,398.6,414.9
XS GIS Cut Line= 4
     1908596.455      627259.101     1909240.986       627712.66
     1909373.365      627845.039     1909538.295      628155.368
#Sta/Elev= 30
       0  915.91    29.2  904.25    97.3  867.31   165.4   835.7   194.6   823.2
   223.8  812.15   291.9   790.6   330.8  776.33     360  769.25   379.5  766.23
   398.9  764.43   535.1  763.23   710.3  759.17   834.9   758.8     863  756.62
   891.1  752.64   900.4  752.66   909.8  754.09   919.2  756.76   928.5   759.7
   937.9  761.48   975.3  764.98   994.9   770.9  1033.9  787.52  1102.2  819.93
  1131.5  832.99  1170.6  848.92  1209.6  862.57  1248.7  871.07  1326.8  867.57
#Mann= 3 , 0 , 0
       0     .05       0     863    .045       0   919.2      .1       0
Bank Sta=863,919.2
XS Rating Curve= 0 ,0
Exp/Cntr=0.3,0.1

Type RM Length L Ch R = 1 ,86652.6 ,359.6,359.3,358.7
XS GIS Cut Line= 4
     1908567.375      627269.409     1908934.129       627590.59
     1908940.639       627753.35     1908925.448      628074.531
#Sta/Elev= 30
       0  914.71    19.5  908.13      39  898.57    48.8  892.88    68.2  879.83
     117  844.24   146.2  827.57   175.5  813.09     195  804.32   224.2  793.36
   253.5  785.23     312   767.1   331.5  763.25   341.3  762.61   497.1  760.39
     545  758.61   564.2  755.38   573.8   753.3   583.3  752.64   592.9  753.44
   612.1  758.23   640.8  766.19   650.4  770.24   669.9  780.79   718.6  810.65
   767.3  839.21   845.3   881.7   913.5   922.6   942.7   941.3   971.9  963.19
#Mann= 3 , 0 , 0
       0     .05       0   564.2    .045       0   612.1     .08       0
Bank Sta=564.2,612.1
XS Rating Curve= 0 ,0
Exp/Cntr=0.3,0.1

Type RM Length L Ch R = 1 ,86293.3 ,382.5,371.3,360.1
XS GIS Cut Line= 4
      1908491.42      627241.197     1908602.097      627462.552
     1908615.118      627627.482     1908745.327       628059.34
#Sta/Elev= 30
       0  927.21     9.5  925.86      19  923.08    28.6  918.79    47.6  907.98
    76.2  889.85   104.7  874.81   133.3   854.5   209.4  794.82   228.4  782.01
     238  776.33   257.2  766.56     267  762.72   276.7  760.15   315.6  754.99
   335.1  752.42   344.8  752.32   354.5  752.94     374  755.76   422.7  762.11
     462  768.84   550.2  785.58   569.8  791.89     609  809.93   667.9  839.75
   746.3  882.48   785.5  906.55   805.2  917.12   834.6  930.42     864  942.32
#Mann= 3 , 0 , 0
       0      .1       0   315.6    .045       0     374     .08       0
Bank Sta=315.6,374
XS Rating Curve= 0 ,0
Exp/Cntr=0.3,0.1

Type RM Length L Ch R = 1 ,85921.9 ,109.1,105.9,102.7
XS GIS Cut Line= 4
     1907602.531      627071.059      1908203.66      627524.618
     1908281.785      627641.805     1908633.347      627991.197
#Sta/Elev= 30
       0  893.93    68.5  875.38   185.8  839.73   244.5  825.09   283.6  820.12
   410.8  812.41   430.3   810.2   479.2  801.58     489  800.82   508.6  801.91
   557.4   807.2   567.2  807.33   674.8  796.36   713.9  790.52   733.5  786.18
   743.3  782.76     753  777.64   762.4  768.92   771.8   762.4   781.2  759.68
   809.4  754.16   828.2  752.22   856.3  754.34   893.9  757.75  1059.1  765.93
  1127.1  777.55  1156.3  787.48    1234  818.71  1321.5  860.34  1389.5  894.49
#Mann= 3 , 0 , 0
       0      .1       0   809.4    .045       0   856.3     .07       0
Bank Sta=809.4,856.3
XS Rating Curve= 0 ,0
Exp/Cntr=0.3,0.1