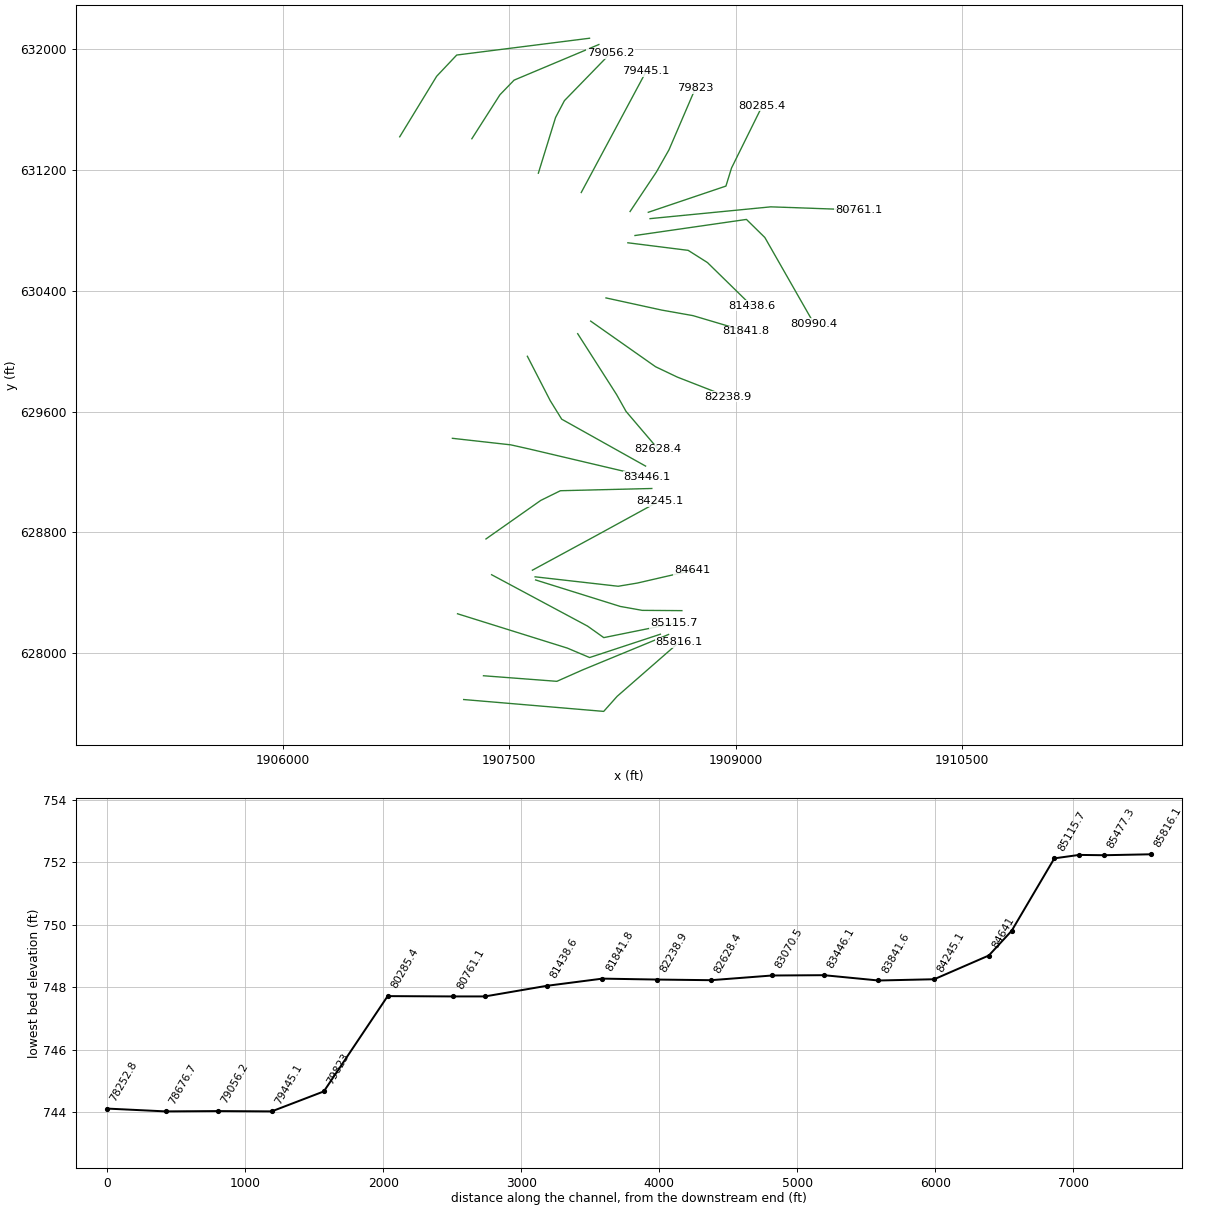
HEC-RAS study HenryFork.prj: HenryFork

--- HenryFork.g01 (geometry) --- (continued)

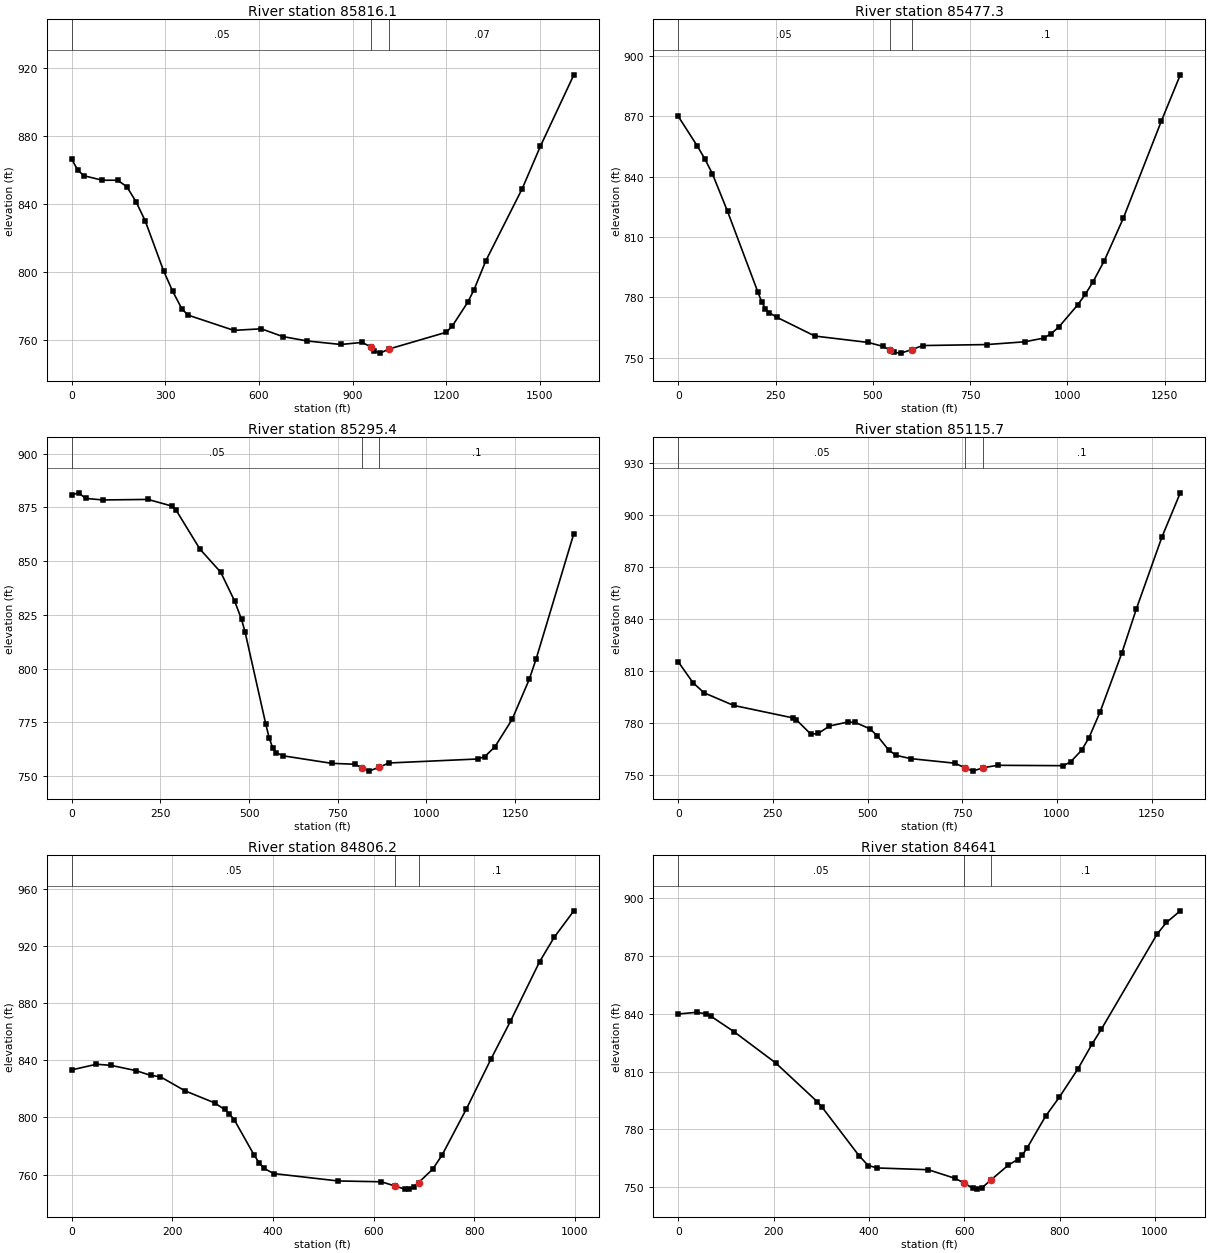
Type RM Length L Ch R = 1 ,85816.1 ,349.2,338.8,328.2
XS GIS Cut Line= 4
      1907199.32       627693.02     1908126.837      627614.461
     1908215.813      627714.288     1908625.969      628072.361
#Sta/Elev= 30
       0  866.29    19.6  859.83    39.2  856.62      98  853.99     147  853.98
   176.4  850.18   205.8   841.4   235.2  830.16     294   800.8   323.3  788.65
   352.7  778.37   372.3  774.64   519.3  765.65   607.5  766.56   676.1     762
   754.5   759.4   862.2  757.34   930.8  758.55   959.5  755.79     969  753.56
   988.2  752.25  1016.8  754.68  1200.7  764.55  1220.1  768.38  1268.7  782.13
  1288.2  789.18  1327.1  806.65  1443.7  849.08  1502.1  874.09    1609  916.01
#Mann= 3 , 0 , 0
       0     .05       0   959.5    .045       0  1016.8     .07       0
Bank Sta=959.5,1016.8
XS Rating Curve= 0 ,0
Exp/Cntr=0.3,0.1

Type RM Length L Ch R = 1 ,85477.3 ,200.5,181.8,162.8
XS GIS Cut Line= 4
     1907330.396      627850.572     1907816.507       627813.68
     1907987.948      627889.635     1908556.525       628124.01
#Sta/Elev= 30
       0  870.05    48.8  855.34    68.2  848.91    87.8  841.46   126.8  822.71
   204.8  782.51   214.5  777.74   224.2  774.24     234  772.34   253.5  770.05
     351  760.72   487.5  757.55     525  755.64   543.8  753.81   553.1  752.61
   571.9  752.22     600  753.97   628.1  755.99   792.2  756.48   889.8  757.85
   938.6  759.67   958.1   761.9   977.6  765.16  1026.4  776.24    1046  781.52
  1065.5  787.64  1094.8  798.22  1143.6  819.37  1241.2  867.65    1290   890.7
#Mann= 3 , 0 , 0
       0     .05       0   543.8    .045       0     600      .1       0
Bank Sta=543.8,600
XS Rating Curve= 0 ,0
Exp/Cntr=0.3,0.1

Type RM Length L Ch R = 1 ,85295.4 ,184.7,179.7,174.8
XS GIS Cut Line= 4
     1907158.521      628261.163     1907885.952      628033.732
     1908033.521      627971.232     1908502.271      628125.746
#Sta/Elev= 30
       0  880.86    19.5   881.8    39.1   879.2    87.9  878.48     215  878.73
   283.4  875.59   293.1  874.03   361.5  855.59   420.2  844.81   459.2  831.44
   478.8  822.87   488.6  817.12   547.2  774.07     557  767.55   566.7  763.05
   576.5  760.83     596  759.36   732.8  755.86   799.9  755.42   818.7  753.61
   837.6  752.23   865.8  753.95   894.1  756.02    1145  757.88  1164.4  758.94
  1193.4  763.56  1241.8  776.27  1290.2  794.95  1309.5  804.38    1416  862.85
#Mann= 3 , 0 , 0
       0     .05       0   818.7    .045       0   865.8      .1       0
Bank Sta=818.7,865.8
XS Rating Curve= 0 ,0
Exp/Cntr=0.3,0.1

Type RM Length L Ch R = 1 ,85115.7 ,299.4,309.5,319.5
XS GIS Cut Line= 4
     1907384.215      628519.843     1908019.632      628179.565
     1908127.271      628103.177     1908590.813      628196.927
#Sta/Elev= 30
       0  815.32      39  803.22    68.2  797.39   146.1  790.11     302  782.92
   311.7  781.84   350.7  773.36   370.1  773.98   399.4  778.19   448.1  780.51
   467.5  780.25   506.5  776.53     526  772.41   555.2  764.45   574.7  761.28
   613.6  759.35   730.2  756.71   758.5  753.91   777.4  752.12   805.6  754.11
   843.4  755.48  1016.9  755.27  1036.2  757.51  1065.1   764.2  1084.4  771.38
  1113.4  786.05  1171.3  820.37  1209.9  846.03  1277.4  887.57  1325.7  912.98
#Mann= 3 , 0 , 0
       0     .05       0   758.5    .045       0   805.6      .1       0
Bank Sta=758.5,805.6
XS Rating Curve= 0 ,0
Exp/Cntr=0.3,0.1

Type RM Length L Ch R = 1 ,84806.2 ,157.4,165.3,173.1
XS GIS Cut Line= 4
     1907675.882      628485.121     1908236.646      628309.774
     1908382.479      628283.732     1908644.632      628281.996
#Sta/Elev= 30
       0  833.27      49  837.24    78.3  836.44   127.3  832.78   156.7  829.46
   176.3  828.44   225.2  818.59     284  810.17   303.6  805.56   313.4  802.51
   323.2  798.17   362.3   773.7   372.1  768.33   381.9  764.35   401.5  760.69
   528.8  755.53   615.3  754.94   643.1  751.91   661.6   749.8   670.9  749.89
   680.1  751.54   689.4  754.44   717.2  763.76   735.7  773.49   784.2  805.91
   832.8  840.65   871.6  867.21   929.9  909.13     959  926.22   997.8  944.64
#Mann= 3 , 0 , 0
       0     .05       0   643.1    .045       0   689.4      .1       0
Bank Sta=643.1,689.4
XS Rating Curve= 0 ,0
Exp/Cntr=0.3,0.1

Type RM Length L Ch R = 1 ,84641   ,388.5,395.9,403.3
XS GIS Cut Line= 4
      1907672.41      628505.954     1908222.757      628443.454
     1908349.815      628464.631     1908710.959      628547.955
#Sta/Elev= 30
       0  839.94    38.9  840.81    58.3     840      68  838.87   116.6  830.81
   204.1   814.6   291.5  794.44   301.2  791.74     379  766.46   398.4  761.26
   417.8     760   524.7  759.08   581.5  754.54   599.9   752.1   618.3  749.44
   627.5  749.01   636.7  749.61   655.1  753.57   692.4  761.46     712  764.37
   721.7  766.64   731.5   770.2   770.5  786.82   799.7  796.81   838.8  811.55
     868  824.27   887.5  831.95  1004.6  881.41  1024.1  887.44  1053.3   893.5
#Mann= 3 , 0 , 0
       0     .05       0   599.9    .045       0   655.1      .1       0
Bank Sta=599.9,655.1
XS Rating Curve= 0 ,0
Exp/Cntr=0.3,0.1

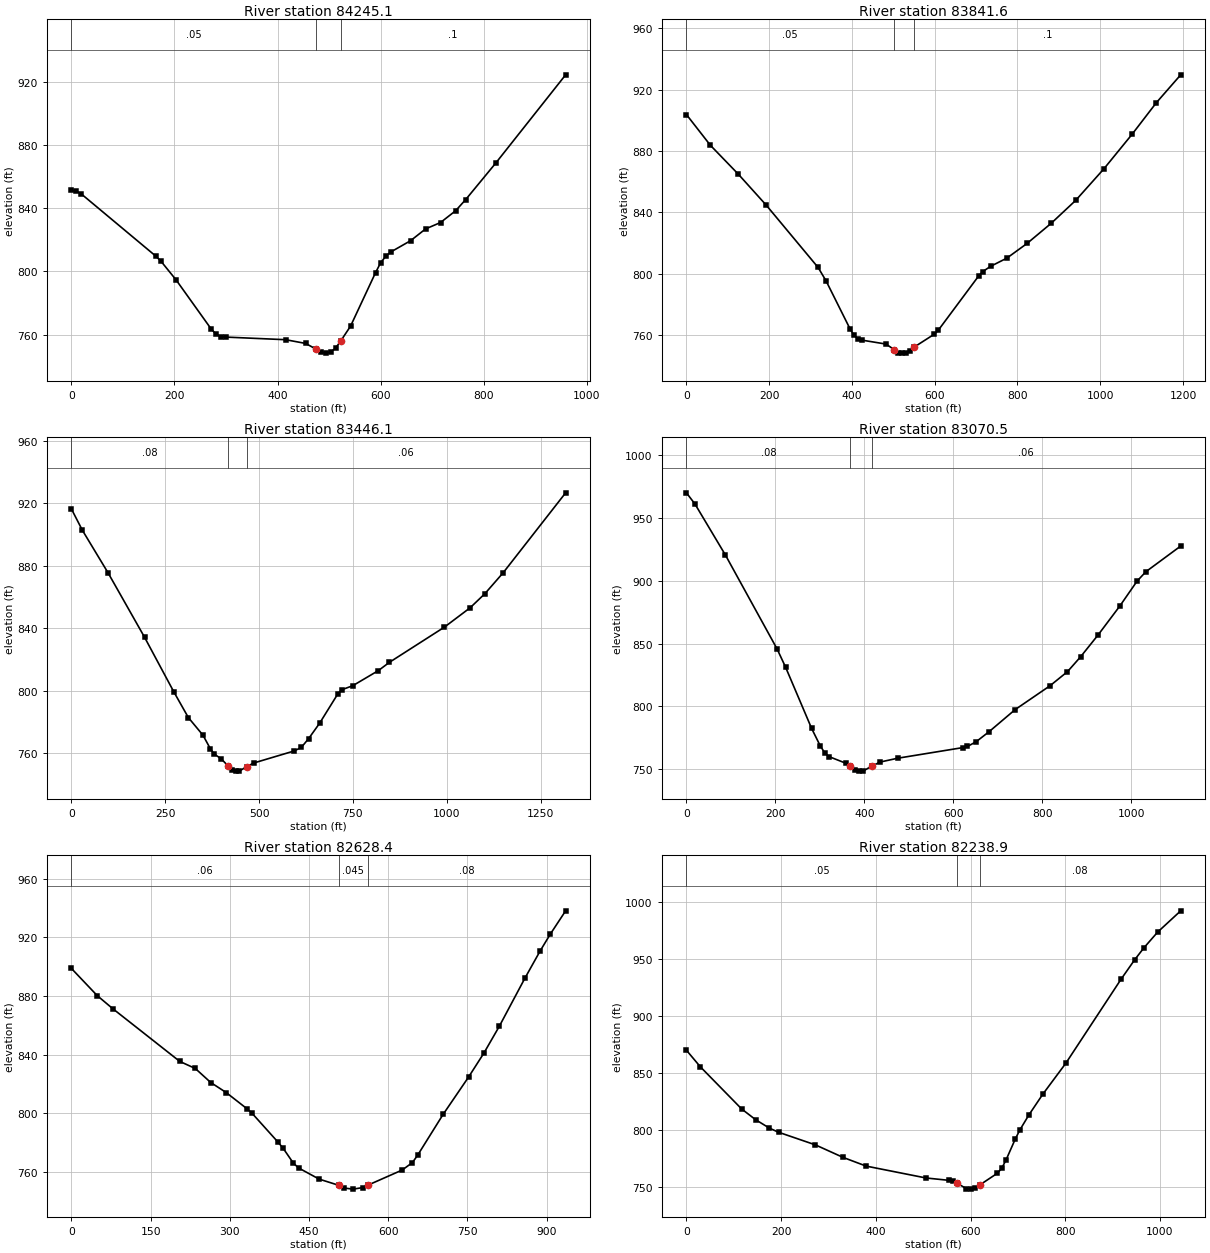
Type RM Length L Ch R = 1 ,84245.1 ,404.3,403.5,402.3
XS GIS Cut Line= 3
     1907654.494      628549.905     1908087.834      628784.903
     1908496.401      629008.484
#Sta/Elev= 30
       0  851.23     9.7  850.67    19.3  848.93   164.3  809.46     174  806.29
     203  794.62   270.6  763.78   280.3  760.32     290  758.66   299.6   758.4
   415.6  756.74   454.3  754.39   473.6  750.97   483.3  748.99     493  748.25
   502.7  748.84   512.4  751.42   522.1  755.78   541.5  765.31     590  799.17
   599.7  805.31   609.4  809.38   619.1  812.15   657.9  819.36     687  826.81
   716.1  830.88   745.2  838.29   764.6  845.29   822.9  868.37   958.7   924.3
#Mann= 3 , 0 , 0
       0     .05       0   473.6    .045       0   522.1      .1       0
Bank Sta=473.6,522.1
XS Rating Curve= 0 ,0
Exp/Cntr=0.3,0.1

Type RM Length L Ch R = 1 ,83841.6 ,411.9,395.6,379.2
XS GIS Cut Line= 4
     1907346.889      628756.822     1907709.736      629012.031
     1907839.945      629076.267     1908445.492      629091.077
#Sta/Elev= 30
       0  903.76    57.9  883.72   125.4  864.88   192.9  844.67   318.2  804.06
   337.5  795.28   395.4     764     405  759.82   414.7  757.52   424.3  756.67
   482.3  754.12   501.7  750.56   511.4  748.54     521  748.21   530.7   748.3
   540.4  749.72   550.1   752.1   598.6  760.49   608.3  763.02     706  798.45
   715.8  801.34   735.4  804.86   774.4  810.16   823.3  819.75   881.9  832.96
   940.5  847.75  1008.9  868.39  1077.3  891.02  1135.9  911.59  1194.5  929.68
#Mann= 3 , 0 , 0
       0     .05       0   501.7    .045       0   550.1      .1       0
Bank Sta=501.7,550.1
XS Rating Curve= 0 ,0
Exp/Cntr=0.3,0.1

Type RM Length L Ch R = 1 ,83446.1 ,390.9,375.5,358.5
XS GIS Cut Line= 4
     1907124.667      629423.489      1907511.82      629380.086
     1907633.858      629352.742     1908414.338      629168.888
#Sta/Elev= 30
       0   916.4    29.2  902.74    97.4  875.56   194.8  834.21   272.7  799.25
   311.7  782.65   350.6  771.37   370.1  762.74   379.8  759.47   399.2  756.24
   418.4  751.45   428.1  749.35   437.7  748.38   447.3  748.39   466.5  751.19
   485.8  753.59   592.9  761.26   612.4  763.56     632  769.23   661.3   779.1
   710.2  798.06     720  800.51   749.3  803.08   817.8  812.81   847.1  818.09
   993.8  840.67  1062.2  853.06  1101.4  862.06  1150.2   875.5  1316.5  926.69
#Mann= 3 , 0 , 0
       0     .08       0   418.4    .045       0   466.5     .06       0
Bank Sta=418.4,466.5
XS Rating Curve= 0 ,0
Exp/Cntr=0.3,0.1

Type RM Length L Ch R = 1 ,83070.5 ,441.7,442.1,442.4
XS GIS Cut Line= 4
     1907621.195      629966.892     1907772.236      629673.489
     1907848.625      629550.225     1908404.181      629239.461
#Sta/Elev= 30
       0  970.16    19.4   961.1    87.4  920.74   203.8  845.77   223.2  831.02
   281.5  782.41   300.9  768.52   310.6  763.19   320.3  759.99     359  754.58
   368.7  752.59   378.3  749.33     388  748.37   397.7  748.46     417  752.44
   436.3  755.66     475  758.65   621.9  767.14   631.7     768   651.3  771.73
   680.7  779.82   739.4  797.44   817.8  816.44     857  827.66   886.3  839.42
   925.5  856.76   974.5  879.85  1013.6  899.85  1033.2  907.26  1111.6  927.75
#Mann= 3 , 0 , 0
       0     .08       0   368.7    .045       0     417     .06       0
Bank Sta=368.7,417
XS Rating Curve= 0 ,0
Exp/Cntr=0.3,0.1

Type RM Length L Ch R = 1 ,82628.4 ,377.2,389.5,401.7
XS GIS Cut Line= 4
     1907954.528      630116.545      1908212.34      629712.899
     1908275.183      629601.198     1908488.382       629350.92
#Sta/Elev= 30
       0  898.74    48.9   880.2    78.2  871.33   205.3   835.3   234.6  830.51
   263.9  820.93   293.2  814.08   332.3  803.09   342.1  799.96     391  780.38
   400.8  776.18   420.3  765.97   430.1  762.69   469.2  755.04   506.4  750.82
   515.6  748.98   533.9  748.22   552.2  749.32   561.4  750.91   626.5  761.26
   645.8  766.34   655.5  771.26   703.8  799.13   752.2   824.7   781.2  841.04
   810.2   859.2   858.5  891.88   887.6  910.63   906.9  922.13   935.9  938.01
#Mann= 3 , 0 , 0
       0     .06       0   506.4    .045       0   561.4     .08       0
Bank Sta=506.4,561.4
XS Rating Curve= 0 ,0
Exp/Cntr=0.3,0.1

Type RM Length L Ch R = 1 ,82238.9 ,391.1,397.1,403.2
XS GIS Cut Line= 4
     1908040.465      630199.878     1908470.153      629897.795
     1908614.049      629829.194     1908948.613      629698.781
#Sta/Elev= 30
       0  869.79    29.2  855.38   116.7  818.37   145.9  809.07   175.1  801.65
   194.5  798.03   272.4  786.96   330.7  776.02   379.4  768.41   505.8     758
   553.4  755.97   562.8   755.2   572.1  753.32   590.9  748.68   600.3  748.24
   609.6   749.2     619  751.78   656.5  762.12   665.9  766.54   675.3  774.17
   694.4  792.13   704.1  800.08   723.5  813.43   752.6  831.38   801.1  858.42
   917.6   931.9   946.7  949.13   966.1  959.51   995.2  973.31  1043.7  991.85
#Mann= 3 , 0 , 0
       0     .05       0   572.1    .045       0     619     .08       0
Bank Sta=572.1,619
XS Rating Curve= 0 ,0
Exp/Cntr=0.3,0.1

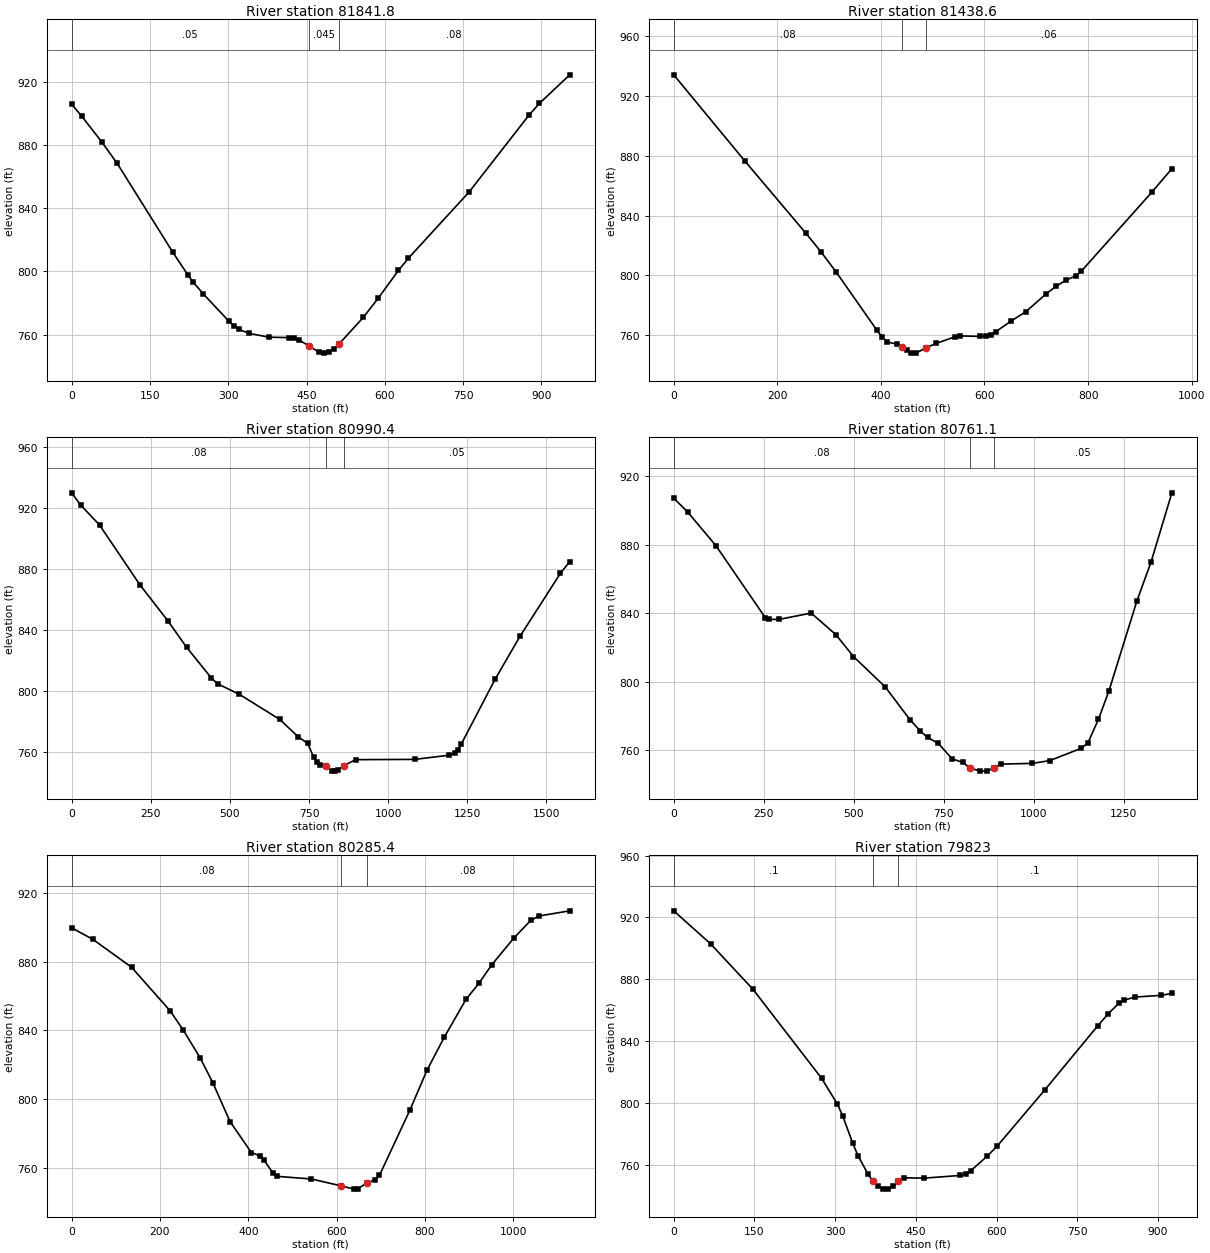
Type RM Length L Ch R = 1 ,81841.8 ,411.9,403.1,394.3
XS GIS Cut Line= 4
     1908142.028      630353.524      1908511.82      630272.795
     1908717.549      630236.336     1909069.111       630132.17
#Sta/Elev= 30
       0  905.73    19.4  898.12    58.2   881.7    87.4  868.25   194.1  811.96
   223.2   797.5   232.9  793.19   252.3   785.7   300.9  768.61   310.6  765.62
   320.3  763.36   339.7  760.78   378.5  758.35   416.5  758.09     426  757.68
   435.5  756.55   454.5  752.93   473.5  748.87     483  748.27   492.5  748.68
     502  750.76   511.5  753.81   558.9  770.91   587.4  783.06     626  800.55
   645.3  808.38   761.1  850.07   876.9  899.14   896.2  906.27   954.1  924.29
#Mann= 3 , 0 , 0
       0     .05       0   454.5    .045       0   511.5     .08       0
Bank Sta=454.5,511.5
XS Rating Curve= 0 ,0
Exp/Cntr=0.3,0.1

Type RM Length L Ch R = 1 ,81438.6 ,452.7,448.2,443.7
XS GIS Cut Line= 4
     1908287.019       630718.76     1908686.299      630668.628
     1908813.903      630587.899     1909105.832      630302.237
#Sta/Elev= 30
       0  934.07   137.4  876.43   255.2  828.16   284.6  815.63   314.1  802.02
   392.6  763.17   402.4  758.74   411.8  755.49   430.7  754.11   440.2  752.44
   449.6  749.84     459  748.04   468.5   748.2   487.4  751.62   506.2  754.48
     544  759.08   553.4  759.56   592.3   759.2     602  759.46   611.8  760.44
   621.5  762.26   650.7  769.33   679.8   775.7   718.7  787.59   738.2   792.7
   757.6  796.87   777.1  799.78   786.8  802.74     923  855.59   961.8  871.32
#Mann= 3 , 0 , 0
       0     .08       0   440.2    .045       0   487.4     .06       0
Bank Sta=440.2,487.4
XS Rating Curve= 0 ,0
Exp/Cntr=0.3,0.1

Type RM Length L Ch R = 1 ,80990.4 ,212.8,229.3,245.8
XS GIS Cut Line= 4
     1908334.045      630766.872     1909072.367      630873.489
     1909194.328      630753.697     1909519.849      630183.385
#Sta/Elev= 30
       0  930.17    29.4  921.98    88.3  909.11   215.9  869.84   304.3  846.23
   363.2  828.94   441.7  808.74   461.3  804.94     530  798.07   657.6  781.58
   716.5   770.1     746  765.84     765  756.66   774.5  753.47     784  752.04
     803  750.93     822  747.89   831.5   747.7     841  748.29     860  751.36
   897.9  755.23  1083.6  755.39  1191.4   758.1    1211  759.38  1220.8  761.64
  1230.6  765.26  1338.4  808.12  1416.8  836.19  1544.2  877.41  1573.6  885.07
#Mann= 3 , 0 , 0
       0     .08       0     803    .045       0     860     .05       0
Bank Sta=803,860
XS Rating Curve= 0 ,0
Exp/Cntr=0.3,0.1

Type RM Length L Ch R = 1 ,80761.1 ,446,475.7,504.9
XS GIS Cut Line= 4
     1908433.912      630878.697     1909233.391      630956.822
     1909387.037      630951.614      1909814.12      630935.989
#Sta/Elev= 30
       0   907.1    39.2  898.87   117.6  879.24   254.7  837.23   264.5  836.24
   293.9  836.33     382  839.98   450.6  827.39   499.6  814.58   587.8  796.88
   656.3  777.79   685.7  771.06   705.3  767.34   734.7  764.02   773.9  754.86
   803.3   752.8   822.5  749.64   851.3   747.7   870.6  747.77   889.8  749.58
     909   751.8   995.9  752.22  1044.4   753.8  1131.8  760.97  1151.3  764.23
  1180.4  778.01  1209.6  794.59  1287.3  847.14  1326.1  869.53  1384.4  910.19
#Mann= 3 , 0 , 0
       0     .08       0   822.5    .045       0   889.8     .05       0
Bank Sta=822.5,889.8
XS Rating Curve= 0 ,0
Exp/Cntr=0.3,0.1

Type RM Length L Ch R = 1 ,80285.4 ,467.1,462.3,457.4
XS GIS Cut Line= 4
     1908422.193      630920.798     1908936.516      631094.409
     1908973.408      631213.767     1909177.401      631626.093
#Sta/Elev= 30
       0  899.75    48.5  892.94   135.7  876.79     223  851.47     252  840.55
   290.8  824.21   319.9  809.53   358.7  787.04   407.1     769   426.5  767.05
   436.2  764.46   455.6   757.1   465.3  755.15   542.8  753.61   610.1  749.62
   638.9  747.71   648.5  747.98   667.8   751.2   687.3  753.12   697.1  755.74
   765.6  793.46   804.8  816.97   843.9  836.11   892.9  858.08   922.2  867.43
   951.6   878.3  1000.6  893.53  1039.7  904.07  1059.3  906.63  1127.8  909.59
#Mann= 3 , 0 , 0
       0     .08       0   610.1    .045       0   667.8     .08       0
Bank Sta=610.1,667.8
XS Rating Curve= 0 ,0
Exp/Cntr=0.3,0.1

Type RM Length L Ch R = 1 ,79823   ,377.4,378,378.5
XS GIS Cut Line= 4
     1908301.533      630926.006      1908475.66      631187.233
     1908559.346      631334.861     1908733.825      631741.111
#Sta/Elev= 30
       0  924.29    68.7  902.92   147.2  873.67   274.7  816.24   304.1   799.6
   313.9  792.03   332.8  774.25   342.2  766.36   361.1  754.33   370.5  749.63
   379.9  746.36   389.4  744.78   398.8  744.66   408.2  746.38   417.6  749.74
   427.1  751.98   464.8  751.74   532.8   753.5   542.6  754.45   552.4  756.65
   581.9  765.72   601.5  772.56     690  808.85   788.2  850.15   807.9  857.97
   827.5   864.7   837.4  866.67     857  868.63   906.1  869.74   925.8     871
#Mann= 3 , 0 , 0
       0      .1       0   370.5    .045       0   417.6      .1       0
Bank Sta=370.5,417.6
XS Rating Curve= 0 ,0
Exp/Cntr=0.3,0.1

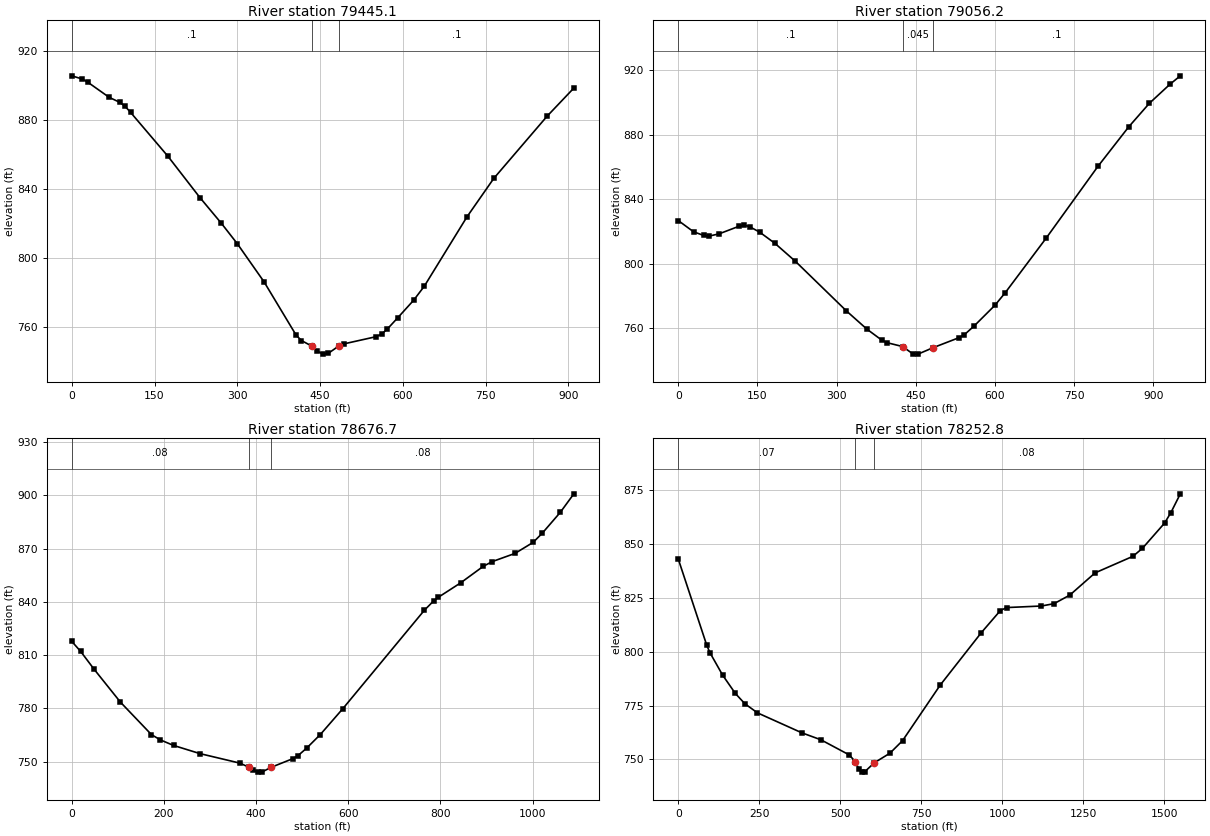
Type RM Length L Ch R = 1 ,79445.1 ,388.6,388.9,388.9
XS GIS Cut Line= 3
     1907978.054      631051.874     1908193.019      631452.891
     1908407.983      631853.909
#Sta/Elev= 30
       0   905.7    19.4  903.81      29     902    67.8   893.2    87.1  890.29
    96.8  887.94   106.5   884.5   174.3  858.96   232.3  834.95   271.1  820.04
   300.1  808.14   348.5  786.02   406.6  755.07   416.3   751.9   435.6   748.6
   445.3  745.77     455  744.02   464.7  744.42     484  748.77   493.7  750.01
   551.8  754.17   561.5   755.7   571.2  758.35   590.5  765.03   619.6  775.31
   638.9  783.45   716.4  823.82   764.8  846.07   861.6  882.27     910  898.59
#Mann= 3 , 0 , 0
       0      .1       0   435.6    .045       0     484      .1       0
Bank Sta=435.6,484
XS Rating Curve= 0 ,0
Exp/Cntr=0.3,0.1

Type RM Length L Ch R = 1 ,79056.2 ,386.2,379.5,373.3
XS GIS Cut Line= 4
     1907693.902      631179.853      1907807.94      631548.837
     1907866.637      631660.381     1908172.572      631974.933
#Sta/Elev= 30
       0  826.84      29  819.86    48.3  817.59    57.9  817.16    77.2  818.56
   115.9  823.39   125.5  823.95   135.2  823.03   154.5  819.58   183.4  812.63
   222.1   801.5   318.6   770.8   357.2  759.56   386.2  752.54   395.9  751.09
     425  748.73   444.4  744.18   454.1  744.03   483.2  748.08   531.8  754.22
   541.5  755.93     561  761.64     600  774.35   619.5  782.15   697.5  816.19
     795  860.43   853.5  884.99   892.5  899.54   931.5  911.33     951  916.53
#Mann= 3 , 0 , 0
       0      .1       0     425    .045       0   483.2      .1       0
Bank Sta=425,483.2
XS Rating Curve= 0 ,0
Exp/Cntr=0.3,0.1

Type RM Length L Ch R = 1 ,78676.7 ,423.2,423.9,423.5
XS GIS Cut Line= 4
     1907253.369      631407.967     1907439.554      631699.444
      1907533.13      631796.212     1908094.825      632032.219
#Sta/Elev= 30
       0  817.72    19.2   812.1      48  802.18   105.7  783.45   172.9  765.18
   192.2   762.2     221  759.06   278.6  754.43   365.1  749.08   384.3  746.79
   393.9  745.06   403.6  744.02   413.2  744.12   432.4   746.7   480.5  751.69
   490.3  753.16     510   757.6   539.4   765.2   588.6  779.88   765.5  835.36
   785.1  840.45   794.9  842.49   844.1  850.74   893.2  860.07   912.9  862.74
     962  867.33  1001.3  873.54    1021  878.67  1060.3  890.48  1089.7  900.92
#Mann= 3 , 0 , 0
       0     .08       0   384.3    .045       0   432.4     .08       0
Bank Sta=384.3,432.4
XS Rating Curve= 0 ,0
Exp/Cntr=0.3,0.1

Type RM Length L Ch R = 1 ,78252.8 ,344.1,327.6,311.7
XS GIS Cut Line= 4
     1906775.492      631420.798     1907020.283       631821.84
     1907153.096      631962.465     1908032.891      632073.749
#Sta/Elev= 30
       0  843.05    88.1  802.96    97.9  799.53     137  789.14   176.2  780.65
   205.6  775.86   244.7  771.61   381.8  762.34   440.5  759.12   527.9  752.11
   547.2  748.89   556.9  745.75   566.6  744.11   576.2  744.34   605.2  748.43
   653.6   752.9   692.5   758.7   809.4  784.62   936.1   808.9   994.6   819.1
  1014.1  820.48  1121.3   821.2  1160.3  822.29    1209  826.27    1287  836.58
  1403.9  844.27  1433.1  847.97  1501.4  859.66  1520.8  864.49  1550.1  873.26
#Mann= 3 , 0 , 0
       0     .07       0   547.2    .045       0   605.2     .08       0
Bank Sta=547.2,605.2
XS Rating Curve= 0 ,0
Exp/Cntr=0.3,0.1