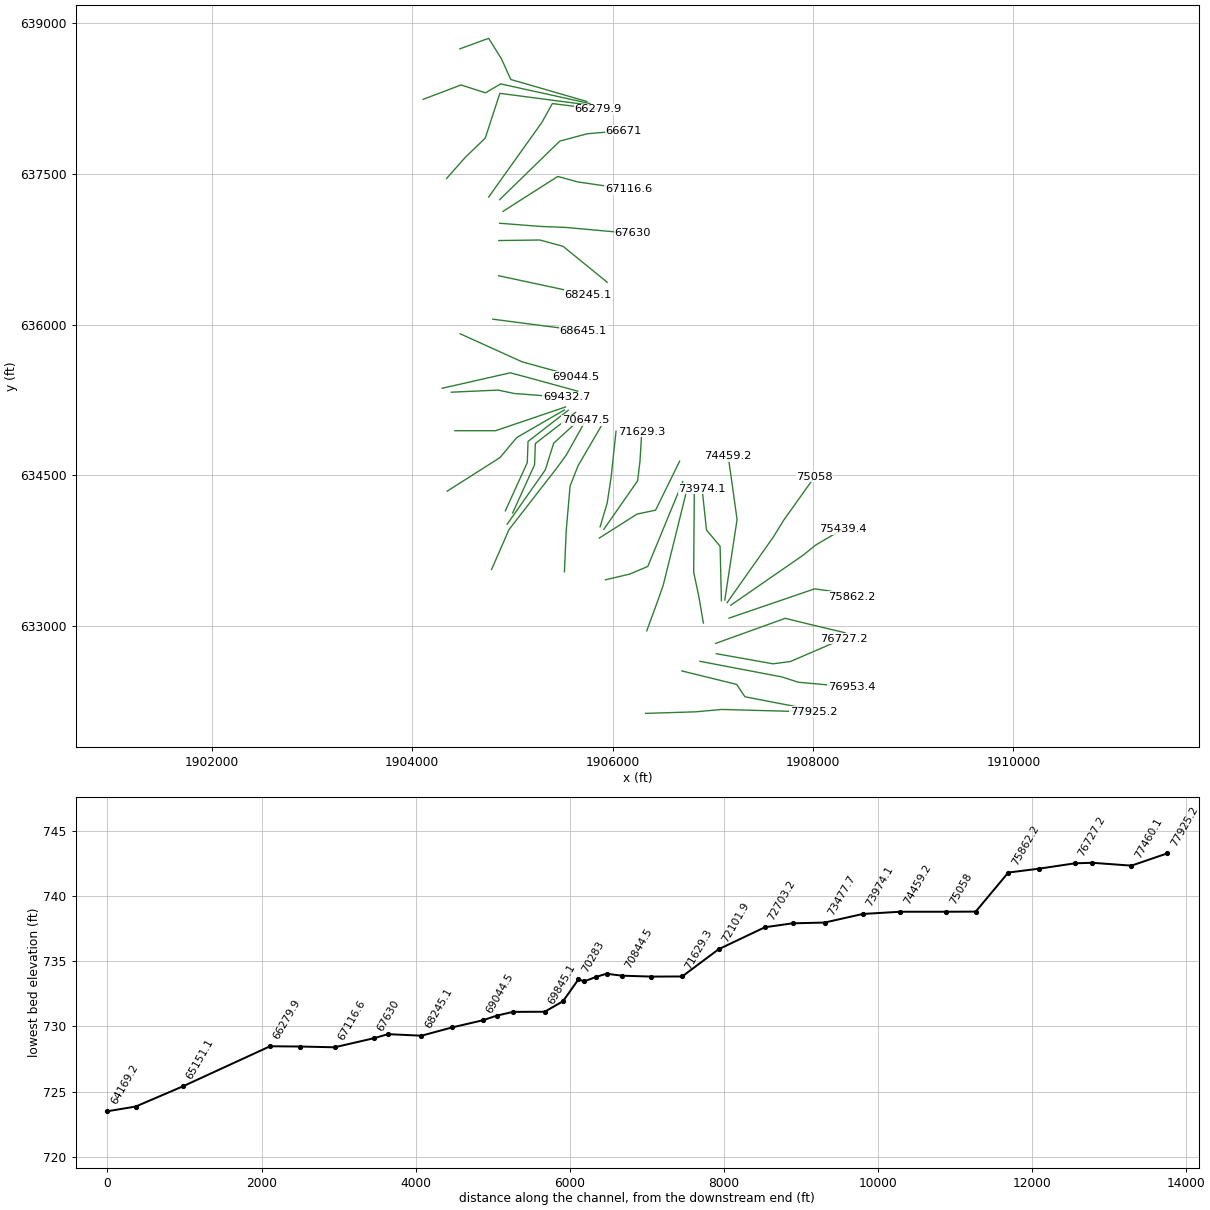
HEC-RAS study HenryFork.prj: HenryFork

--- HenryFork.g01 (geometry) --- (continued)

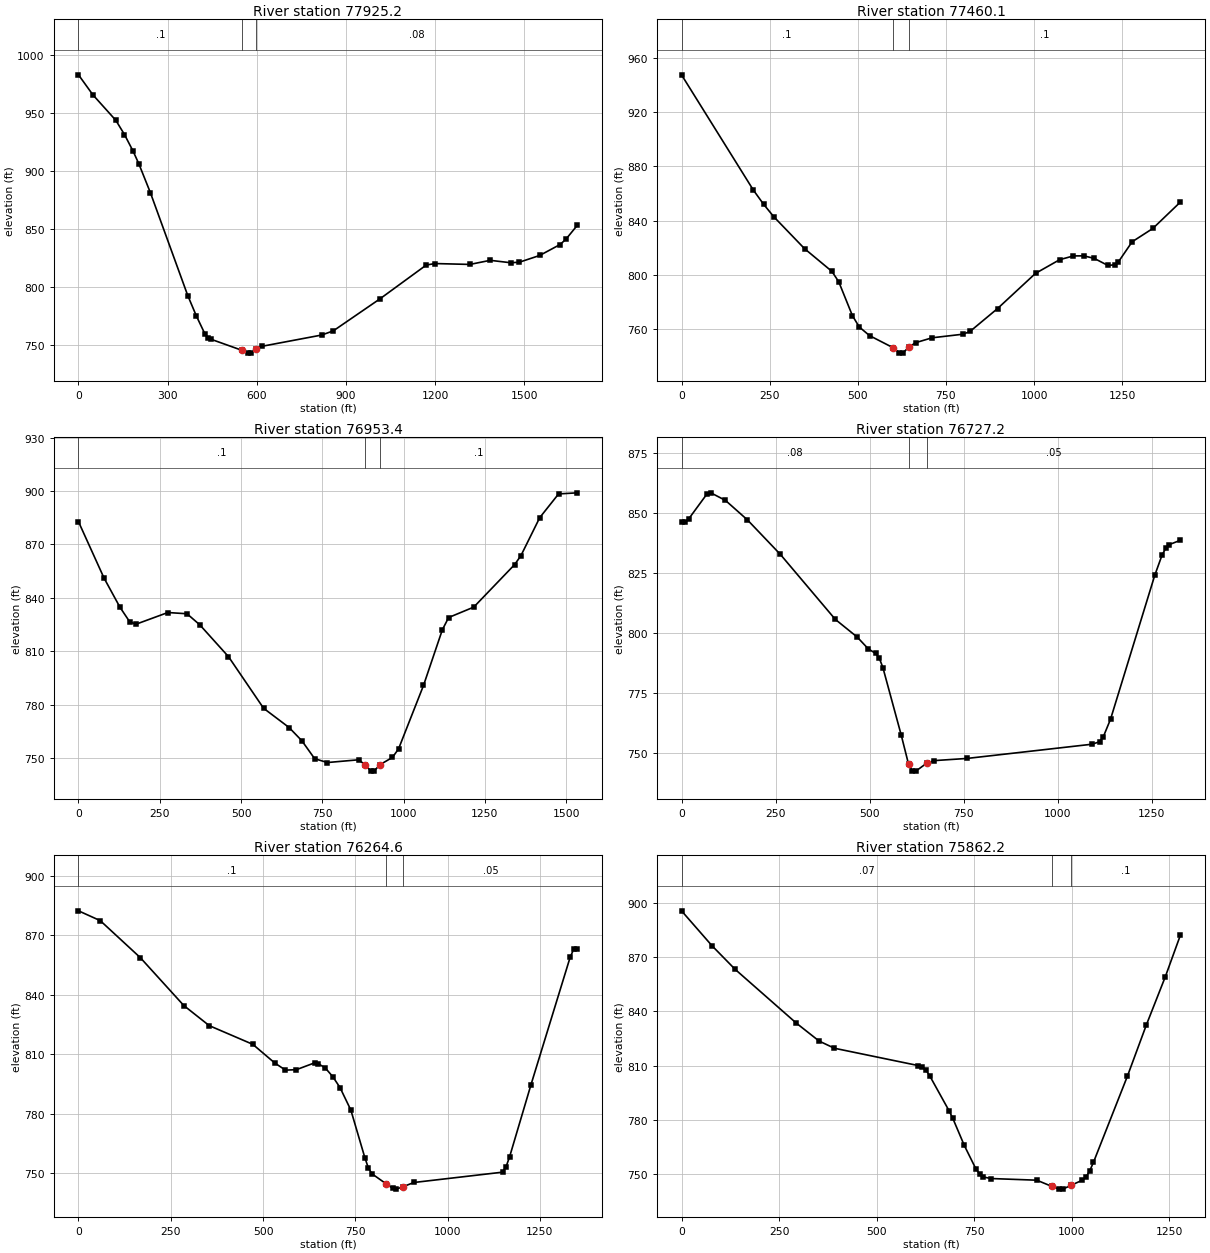
Type RM Length L Ch R = 1 ,77925.2 ,489.1,465.2,441.2
XS GIS Cut Line= 4
     1906330.179       632134.34     1906832.783      632149.965
     1907087.992      632173.402     1908006.748      632148.467
#Sta/Elev= 30
       0  982.57    48.4  965.38   125.7  943.41   154.7  931.22   183.7  916.92
   203.1  905.99   241.8  881.26   367.5  792.82   396.5  775.23   425.5  759.67
   435.2   756.6   444.8   755.3   550.3  745.66   569.3  743.29   578.8  743.29
   597.3  746.53   616.8  749.15   817.8  758.84   856.9  762.41  1013.4  789.85
  1169.8  819.03  1199.1  820.31  1316.4  819.55  1384.9  823.08  1453.3  821.01
  1482.7  821.45  1551.1  827.25  1619.6  836.64  1639.1  841.12  1678.2   853.3
#Mann= 3 , 0 , 0
       0      .1       0   550.3    .045       0   597.3     .08       0
Bank Sta=550.3,597.3
XS Rating Curve= 0 ,0
Exp/Cntr=0.3,0.1

Type RM Length L Ch R = 1 ,77460.1 ,490.6,506.7,522.6
XS GIS Cut Line= 4
     1906692.404      632556.195     1907238.599      632422.361
     1907321.217      632299.286     1908013.339      632166.284
#Sta/Elev= 30
       0  947.59   203.6  862.66   232.7  852.18   261.8  842.92     349  819.38
   426.6  802.63     446  794.98   484.8  769.98   504.2  761.65   533.3  755.28
   599.4  746.45   617.9  742.69   627.2  742.35   645.7  746.94   664.3  750.07
   710.6  753.65   798.7  756.31   818.3  758.31   896.6  775.24  1004.2  801.17
  1072.8  811.27  1111.9  814.05  1141.3  814.08  1170.6  812.24  1209.8  806.98
  1229.4  807.54  1239.2  809.61  1278.3  824.46  1337.1  834.31  1415.4  853.81
#Mann= 3 , 0 , 0
       0      .1       0   599.4    .045       0   645.7      .1       0
Bank Sta=599.4,645.7
XS Rating Curve= 0 ,0
Exp/Cntr=0.3,0.1

Type RM Length L Ch R = 1 ,76953.4 ,216.9,226.2,235.3
XS GIS Cut Line= 4
      1906872.28      632651.961     1907692.158      632496.145
     1907852.748      632444.062     1908382.262      632396.319
#Sta/Elev= 30
       0  882.75    78.6  851.07   127.6  834.67   157.1  826.61   176.7  825.12
   274.9   831.7   333.8  831.01   373.1  824.81   461.5  806.89   569.5  777.89
     648  767.06   687.3  759.62   726.6  749.55   765.8   747.4   862.7  748.96
   881.4  746.03   900.2  742.57   909.6  742.75   928.4  746.27   965.9   750.3
   984.6  755.04  1061.4  790.71  1119.4     822  1138.7  828.89    1216  834.74
  1341.7  858.63    1361  863.62    1419  885.03    1477  898.36    1535  898.97
#Mann= 3 , 0 , 0
       0      .1       0   881.4    .045       0   928.4      .1       0
Bank Sta=881.4,928.4
XS Rating Curve= 0 ,0
Exp/Cntr=0.3,0.1

Type RM Length L Ch R = 1 ,76727.2 ,470.6,462.6,454.2
XS GIS Cut Line= 4
      1907035.04      632727.916     1907600.578      632627.222
     1907774.189      632649.791     1908304.571      632877.656
#Sta/Elev= 30
       0  846.41     9.7  846.15    19.5  847.73    68.2  858.15    77.9  858.51
   116.8  855.36   175.2  847.24   262.9  832.84   408.9  805.78   467.3  798.38
   496.5  793.51     516  791.59   525.8  789.65   535.5  785.68   584.2  757.57
   603.6  745.49   613.3  742.77   623.1  742.53   652.2  745.87   671.7  746.91
   759.3  747.82    1092  753.75  1111.5  754.77  1121.3  756.72  1140.9   764.2
  1258.3  824.07  1277.8  832.56  1287.6  835.38  1297.4  836.95  1326.8  838.76
#Mann= 3 , 0 , 0
       0     .08       0   603.6    .045       0   652.2     .05       0
Bank Sta=603.6,652.2
XS Rating Curve= 0 ,0
Exp/Cntr=0.3,0.1

Type RM Length L Ch R = 1 ,76264.6 ,400.2,402.4,404.6
XS GIS Cut Line= 4
      1907028.53      632829.913     1907722.974      633079.479
     1907953.009      633023.055     1908319.762       632936.25
#Sta/Elev= 30
       0  882.33      59  877.38   167.3  858.78   285.3  834.62   354.2  824.49
   472.3  815.06   531.3  805.73   560.8  802.07   590.3   802.3   639.5  805.73
   649.4  805.38     669  803.07   688.7  798.83   708.4  793.32   737.9  781.92
   775.8  757.95   785.3  752.78   794.8  749.88   832.7  744.89   851.6  742.46
   861.1  742.12     880  743.39   908.5  745.46  1148.7  750.66  1158.4  753.42
  1168.1  758.52    1226  794.82  1332.3  859.15    1342  863.09  1351.7  863.17
#Mann= 3 , 0 , 0
       0      .1       0   832.7    .045       0     880     .05       0
Bank Sta=832.7,880
XS Rating Curve= 0 ,0
Exp/Cntr=0.3,0.1

Type RM Length L Ch R = 1 ,75862.2 ,404.3,422.8,441.2
XS GIS Cut Line= 4
     1907163.078      633081.649     1908015.943      633372.447
     1908159.561      633352.523     1908384.867      633294.322
#Sta/Elev= 30
       0   895.5    78.4  876.16   137.1  863.25   293.8  833.57   352.6  823.59
   391.8  819.62   607.2  810.03     617  809.25   626.8  807.44   636.6   804.2
   685.6  785.14   695.4  780.86   724.8  765.92   754.2  753.12     764  750.13
   773.8  748.51   793.3  747.67   910.7  746.75   949.4   743.3   968.7  741.82
   978.4  741.92   997.7  743.87  1026.7   746.7  1036.4  748.38  1046.1  751.87
  1055.8  756.62    1143   804.3  1191.5  832.56    1240  859.12  1278.8  882.18
#Mann= 3 , 0 , 0
       0     .07       0   949.4    .045       0   997.7      .1       0
Bank Sta=949.4,997.7
XS Rating Curve= 0 ,0
Exp/Cntr=0.3,0.1

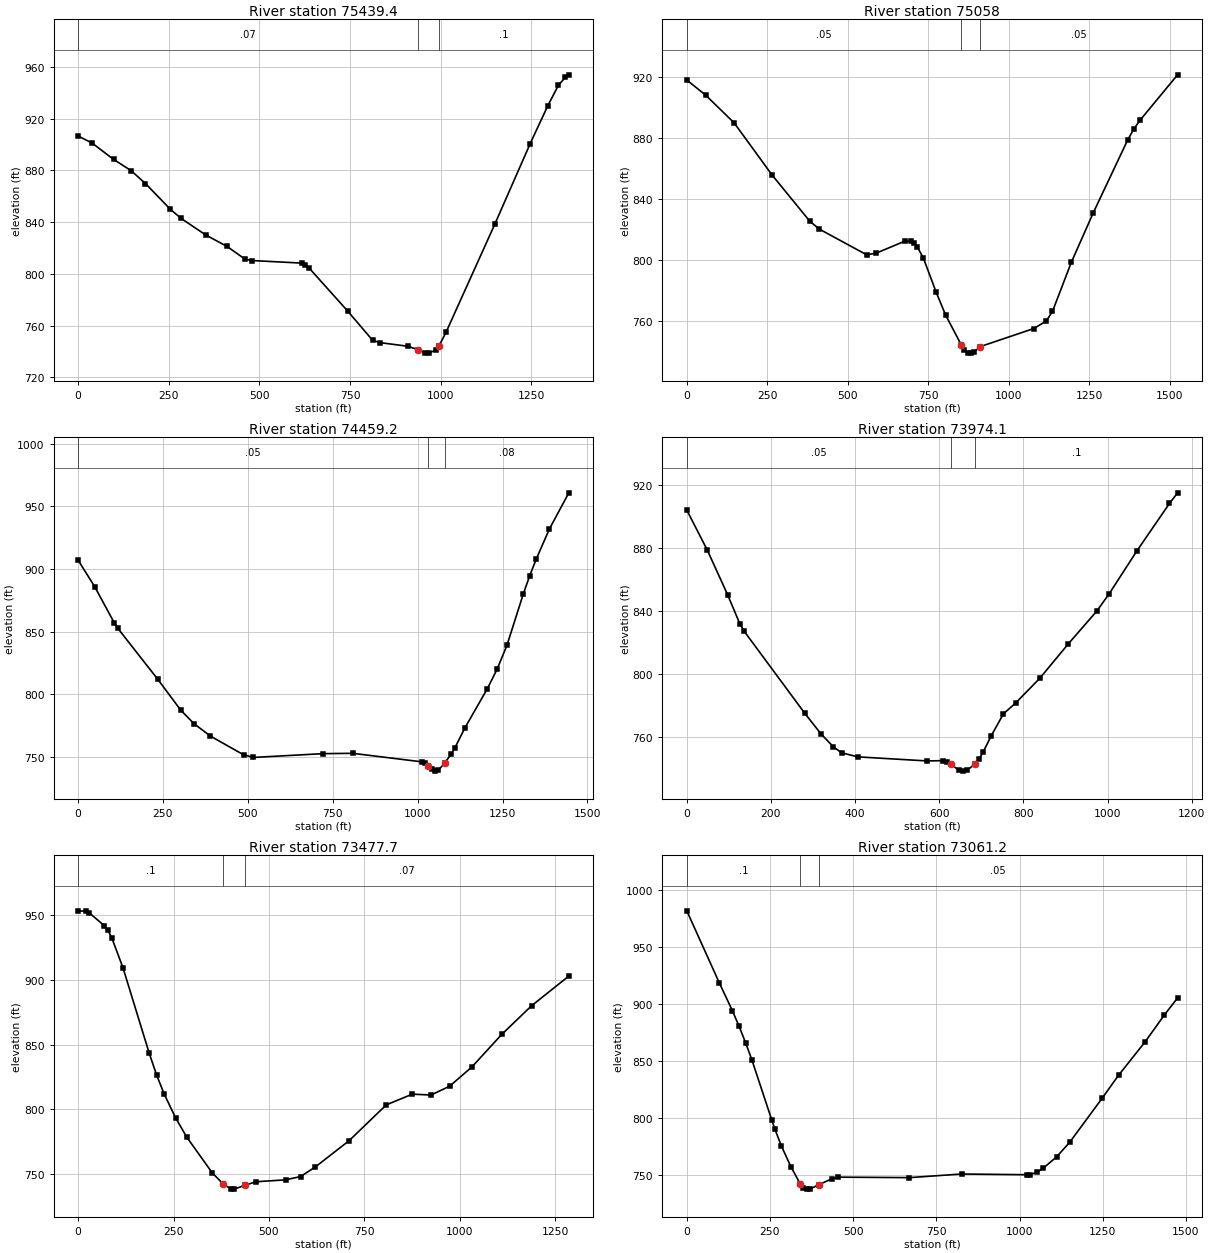
Type RM Length L Ch R = 1 ,75439.4 ,373.8,381.4,388.9
XS GIS Cut Line= 4
     1907180.005      633209.687     1907905.118      633709.442
     1908023.755      633806.041     1908299.797        633967.5
#Sta/Elev= 30
       0  906.59    39.1  901.04    97.8   888.5   146.8  879.67   185.9   869.8
   254.4  849.96   283.8  842.95   352.3  830.05     411  821.22   459.9  811.52
   479.5  810.36   616.4  808.37   626.2  807.26     636  804.92   743.7  771.26
   812.2  748.75   831.7  746.97   909.3  744.13     938  741.44   957.1  739.04
   966.7  738.82   985.8   741.1   995.4  744.44  1014.5  754.79  1149.9  838.83
  1246.8  900.66  1295.3  929.86  1324.4  945.64  1343.7  951.89  1353.4  953.82
#Mann= 3 , 0 , 0
       0     .07       0     938    .045       0   995.4      .1       0
Bank Sta=938,995.4
XS Rating Curve= 0 ,0
Exp/Cntr=0.3,0.1

Type RM Length L Ch R = 1 ,75058   ,583.2,598.8,614.4
XS GIS Cut Line= 4
     1907143.547      633235.729      1907601.88      633884.166
     1907710.598      634059.156     1908015.943      634485.729
#Sta/Elev= 30
       0  918.22    58.8  908.23     147   890.1   264.7  855.88   382.3  825.42
   411.7  820.28   558.8  803.41   588.2  804.48   676.4  812.28     696  812.38
   705.8  811.24   715.6  808.84   735.2  801.15   774.5  778.96   803.9  763.91
   852.9  744.14   862.7  740.73   872.6  739.03   882.4  738.81   892.2  739.49
   911.8   743.1  1077.8  754.95  1116.6  759.86  1136.1   766.2  1194.4  798.35
  1262.4   830.8  1369.2  878.63  1388.7  886.03  1408.1  891.79  1524.7  921.63
#Mann= 3 , 0 , 0
       0     .05       0   852.9    .045       0   911.8     .05       0
Bank Sta=852.9,911.8
XS Rating Curve= 0 ,0
Exp/Cntr=0.3,0.1

Type RM Length L Ch R = 1 ,74459.2 ,473.9,485.2,496
XS GIS Cut Line= 4
      1907120.11       633261.77     1907242.505       634061.25
      1907195.63      634397.187     1907153.964      634691.458
#Sta/Elev= 30
       0  907.15    48.7   886.1   107.2  856.82   116.9  852.79   233.9  812.36
   302.1  787.55   341.1  776.73   389.8  766.77   487.2  751.86   516.5  749.73
   721.1  752.75   808.8  753.02  1012.3  746.22    1022  745.35  1031.7  743.18
  1041.4  740.35  1051.1  738.81  1060.7  739.36  1080.2  745.56  1099.5   752.6
  1109.2  757.13  1138.3  772.89  1205.5  804.73  1234.3  820.34    1263  839.23
    1311  880.08  1330.1   894.8  1349.3  908.02  1387.7  931.87  1445.2  960.85
#Mann= 3 , 0 , 0
       0     .05       0  1031.7    .045       0  1080.2     .08       0
Bank Sta=1031.7,1080.2
XS Rating Curve= 0 ,0
Exp/Cntr=0.3,0.1

Type RM Length L Ch R = 1 ,73974.1 ,506.5,496.3,485.9
XS GIS Cut Line= 4
     1907086.255      633253.958     1907073.235      633795.625
     1906937.818      633957.083     1906893.547      634368.541
#Sta/Elev= 30
       0  903.91    48.4  878.76    96.8  850.44   125.8  832.11   135.5  827.52
   280.6  775.19   319.3  762.11   348.3  754.07   367.7  750.29   406.4  747.67
   570.6   745.1   608.9  745.27   618.4  744.65     628  743.02   647.2  739.08
   656.8  738.64   666.3  739.21   685.5  743.29   695.1  746.51   704.7  750.94
   723.8  761.15   752.6  774.94   781.4  781.73   839.2  797.51   906.5  819.16
   973.9  839.81  1002.8  850.51  1070.1  878.23  1147.1  908.11  1166.4  914.86
#Mann= 3 , 0 , 0
       0     .05       0     628    .045       0   685.5      .1       0
Bank Sta=628,685.5
XS Rating Curve= 0 ,0
Exp/Cntr=0.3,0.1

Type RM Length L Ch R = 1 ,73477.7 ,427.4,416.5,404.6
XS GIS Cut Line= 4
     1906906.568      633032.604     1906859.693      633303.437
     1906809.749      633537.777     1906815.422      634308.645
#Sta/Elev= 30
       0  953.22    19.6  953.59    29.4  951.94    68.7  942.11    78.5  938.35
    88.4  932.57   117.8  909.31   186.5  843.12   206.1  826.04   225.8  811.49
   255.2  793.33   284.4  778.36   351.5  750.59   380.3  741.87   399.4  738.22
     409  737.98   437.8  741.04   466.5   743.7   543.7  745.18   582.8  747.73
   621.8  755.24   709.6  775.44   807.2  803.26   875.5  811.56   924.3  810.88
   973.1  817.69  1031.6  832.66  1109.7  857.86  1187.8  880.03  1285.4  903.06
#Mann= 3 , 0 , 0
       0      .1       0   380.3    .045       0   437.8     .07       0
Bank Sta=380.3,437.8
XS Rating Curve= 0 ,0
Exp/Cntr=0.3,0.1

Type RM Length L Ch R = 1 ,73061.2 ,376.9,358,339.1
XS GIS Cut Line= 4
     1906341.464      632954.479     1906443.026       633230.52
     1906505.526      633407.604      1906745.11      634371.145
#Sta/Elev= 30
       0  981.54      98  918.28   137.3   893.9   156.9   880.6   176.5  866.19
   196.1  850.64   254.9  798.79   264.7  790.48   284.3   775.6   312.9  757.49
   341.1  742.35   350.5  738.73   359.9  737.92   369.2  737.92   397.4  741.86
     435  746.86   453.8  748.41   668.7  747.99     826  751.16  1022.6  750.53
  1032.4  750.68  1052.1  752.67  1071.8  756.43  1111.1   766.1  1150.4  778.83
  1248.7  817.68  1297.8  837.74  1376.5  866.55  1435.5  890.52  1474.8  905.24
#Mann= 3 , 0 , 0
       0      .1       0   341.1    .045       0   397.4     .05       0
Bank Sta=341.1,397.4
XS Rating Curve= 0 ,0
Exp/Cntr=0.3,0.1

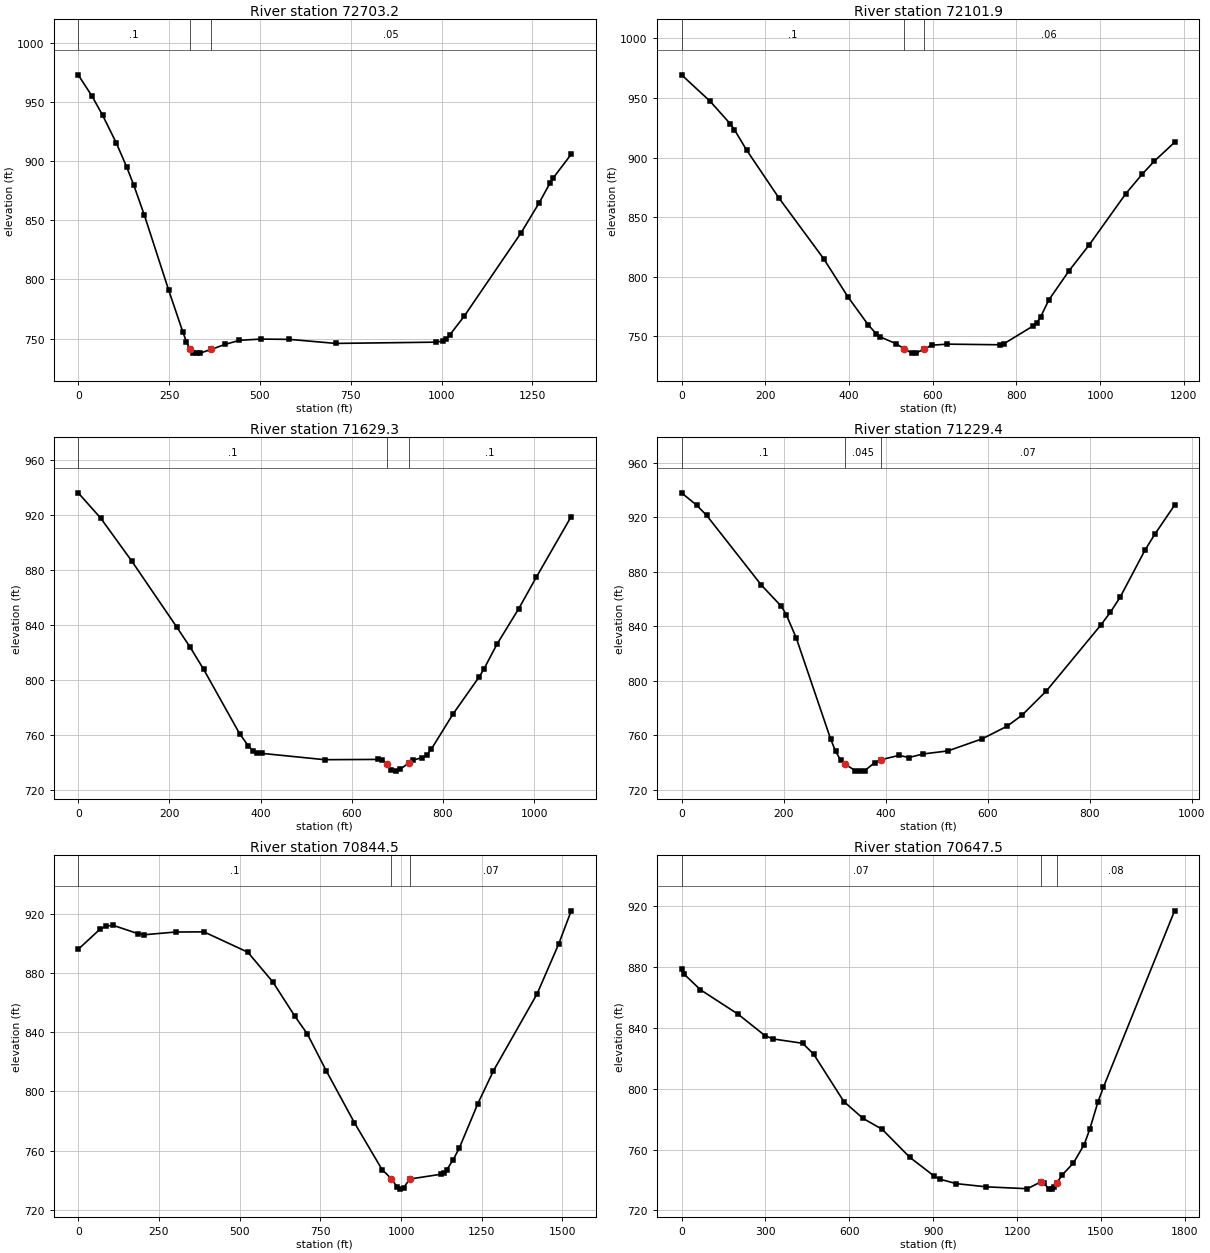
Type RM Length L Ch R = 1 ,72703.2 ,605.5,601.3,597
XS GIS Cut Line= 4
     1905930.005      633462.291     1906172.193      633519.583
      1906351.88      633595.104     1906700.839      634438.854
#Sta/Elev= 30
       0  973.27    38.3  955.08      67  939.17   105.3  915.29     134  894.83
   153.2  879.66   181.9  854.65   248.9  791.08   287.8  755.74   297.6  747.44
   307.4  740.85   317.1  738.08   326.8  737.62   336.6  737.75   365.8  740.75
   404.8  745.07   443.8  748.47   502.7  749.51   581.2  749.27   708.9  745.84
   983.8  746.91  1003.4  747.85  1013.2  749.79    1023  753.18  1062.3  768.87
  1219.4  839.76  1268.5  864.82  1297.9  881.28  1307.8  886.14  1356.8     906
#Mann= 3 , 0 , 0
       0      .1       0   307.4    .045       0   365.8     .05       0
Bank Sta=307.4,365.8
XS Rating Curve= 0 ,0
Exp/Cntr=0.3,0.1

Type RM Length L Ch R = 1 ,72101.9 ,444,472.6,500.9
XS GIS Cut Line= 4
     1905867.984      633877.396      1906245.11      634115.937
     1906430.005         634155.     1906669.589      634641.979
#Sta/Elev= 30
       0  969.48    67.9  947.41   116.4  928.34   126.1  923.53   155.2  906.46
   232.8  866.03   339.5  815.18   397.7  783.05   446.2  759.54   465.1  752.23
   474.6  749.54   512.4  743.86   531.3  739.68   550.2  735.95   559.6  735.93
   578.5  739.13   597.4  742.57   635.2  743.48   761.2  742.93   770.9  743.97
   838.7  758.45   848.4  761.28   858.1  766.49   877.5  780.58     926  805.13
   974.4  826.98  1061.6  869.84  1100.4  886.03  1129.5  897.03  1177.9  912.81
#Mann= 3 , 0 , 0
       0      .1       0   531.3    .045       0   578.5     .06       0
Bank Sta=531.3,578.5
XS Rating Curve= 0 ,0
Exp/Cntr=0.3,0.1

Type RM Length L Ch R = 1 ,71629.3 ,400.6,399.9,399.2
XS GIS Cut Line= 4
     1905912.644      633963.159     1906250.318      634446.666
     1906273.755      634639.375     1906291.985       634936.25
#Sta/Elev= 30
       0   936.1    49.2  917.78     118  886.25   216.2  838.52   245.7  823.82
   275.2  807.78   353.8  761.18   373.5  752.03   383.3   748.8   393.2  747.32
     403  746.74   540.6  742.15   657.7  742.35   667.4  742.01   677.1  738.72
   686.8  734.54   696.5  733.84   706.2  735.21   725.6  739.89   735.3  741.86
   754.8  743.73   764.5  745.52   774.2  749.67   822.2  775.38   879.8  802.48
   889.4  807.73   918.2  825.92   966.2   851.9  1004.6  874.65  1081.3  918.86
#Mann= 3 , 0 , 0
       0      .1       0   677.1    .045       0   725.6      .1       0
Bank Sta=677.1,725.6
XS Rating Curve= 0 ,0
Exp/Cntr=0.3,0.1

Type RM Length L Ch R = 1 ,71229.4 ,390.1,384.9,379.4
XS GIS Cut Line= 4
     1905876.186      633989.201     1905946.498      634223.576
     1905985.561      634478.784      1906035.04      634939.722
#Sta/Elev= 30
       0  937.89    29.4  928.87    48.9  921.48   156.6  870.17   195.8  854.62
   205.5  848.38   225.1  831.19   292.5  757.09   302.1  748.28   311.6  742.03
   321.2  738.79   340.3  734.24   349.9  733.83   359.4  734.27   378.6  740.08
   391.5  742.24   426.4  745.39   445.5   743.8   474.2  746.45   522.2  748.65
   589.8  757.59   638.1  766.76   667.1  774.72   715.4  792.69   821.6  840.78
   840.9  850.44   860.2  861.61   908.5  895.86   927.8  907.53   966.5  928.83
#Mann= 3 , 0 , 0
       0      .1       0   321.2    .045       0   391.5     .07       0
Bank Sta=321.2,391.5
XS Rating Curve= 0 ,0
Exp/Cntr=0.3,0.1

Type RM Length L Ch R = 1 ,70844.5 ,202.7,197,191.5
XS GIS Cut Line= 5
     1905520.252      633541.877     1905538.098      633950.313
     1905576.707      634395.451     1905657.436      634598.576
     1905886.603      634989.201
#Sta/Elev= 30
       0  896.04    68.1  909.79    87.6  911.74   107.1  912.37   184.9  906.69
   204.4  905.92   301.8  907.77   389.4  907.88   525.4  894.12   603.1  873.95
   671.1  850.83   709.9   838.8   768.2     814   855.6  778.81   941.2  747.14
   969.7  741.01   988.7  735.19   998.2   733.9  1007.7  734.69  1026.7   740.7
  1122.4  743.92    1132  744.89  1141.7     747  1160.9  753.51  1180.2  761.52
    1238  791.75  1286.2   813.9  1421.1  865.79  1488.6  899.76  1527.1   922.1
#Mann= 3 , 0 , 0
       0      .1       0   969.7    .045       0  1026.7     .07       0
Bank Sta=969.7,1026.7
XS Rating Curve= 0 ,0
Exp/Cntr=0.3,0.1

Type RM Length L Ch R = 1 ,70647.5 ,131.5,138.9,146.2
XS GIS Cut Line= 5
      1904793.69      633565.315      1904967.53      633962.219
     1905444.008      634573.251     1905540.248      634705.347
     1905731.975       635047.03
#Sta/Elev= 30
       0  878.75     9.6  875.36    67.4   865.2   202.2  849.12   298.5  834.99
   327.4  832.83   433.3  829.97   472.5  822.81   580.4  791.67   649.1  780.57
   717.7  773.38   815.8  755.07   904.1  742.54   923.7  740.61   982.6  737.66
  1090.5  735.55    1237  734.32  1285.1  738.83  1294.7  738.33  1313.9  734.12
  1323.5  734.05  1333.1  735.49  1342.8  738.32    1362   743.5    1401  751.08
  1440.2  763.38  1459.8  773.32  1489.1   791.2  1508.7  800.99  1763.4   917.1
#Mann= 3 , 0 , 0
       0     .07       0  1285.1    .045       0  1342.8     .08       0
Bank Sta=1285.1,1342.8
XS Rating Curve= 0 ,0
Exp/Cntr=0.3,0.1

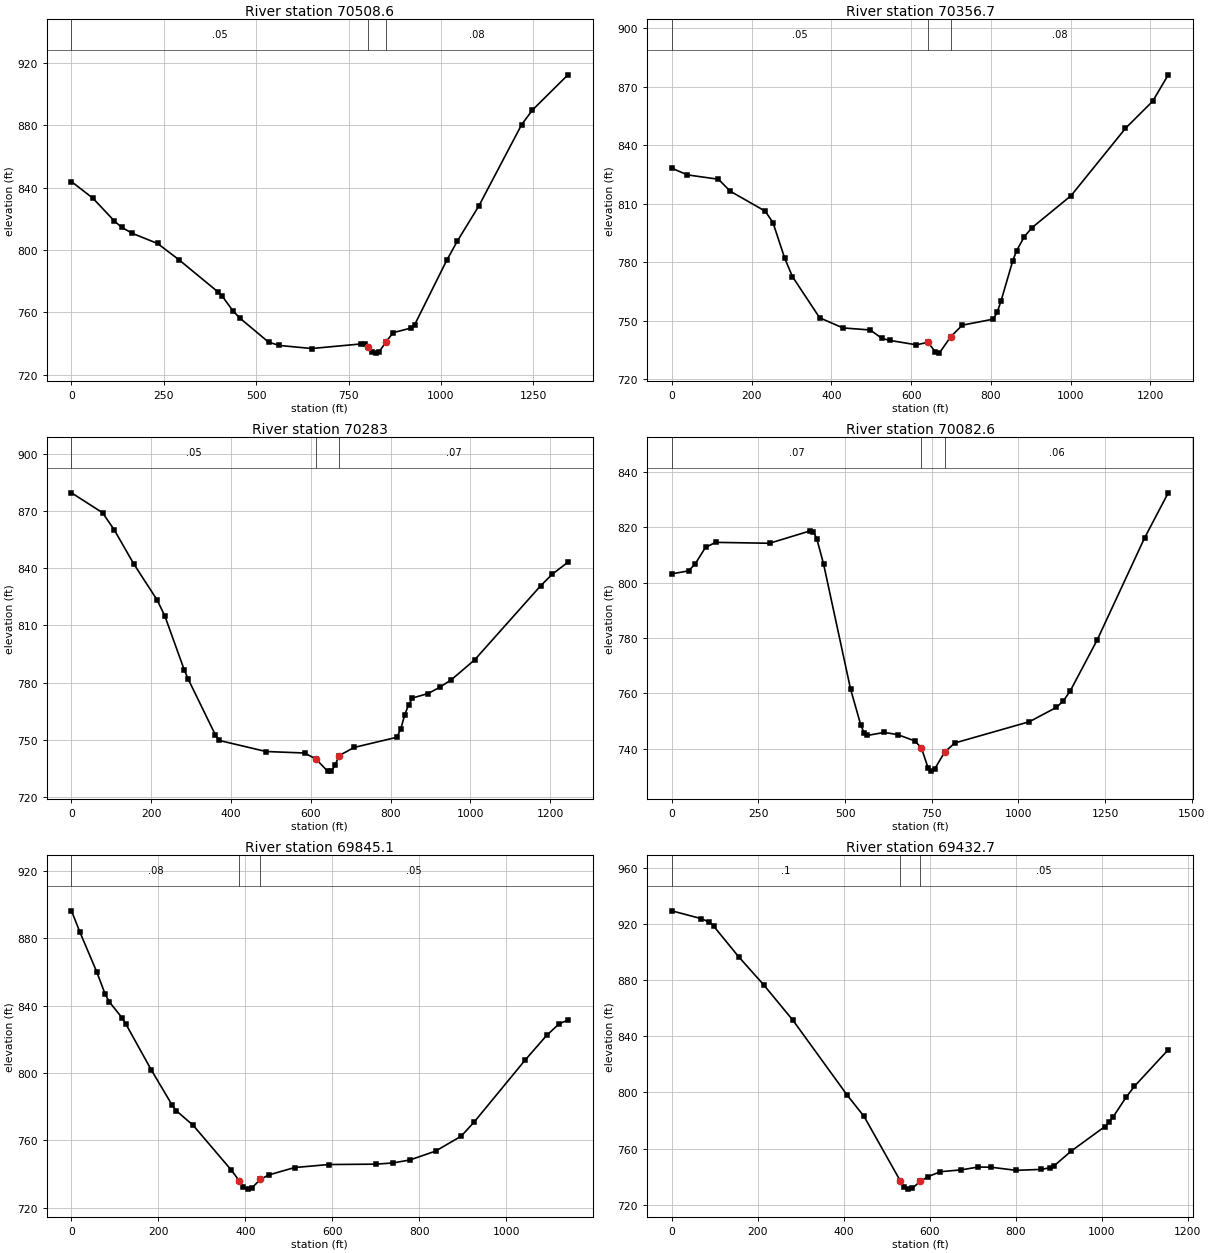
Type RM Length L Ch R = 1 ,70508.6 ,145.9,151.9,157.9
XS GIS Cut Line= 4
     1904949.103      634015.243     1905329.311      634554.305
     1905412.644       634819.93     1905712.123      635093.368
#Sta/Elev= 30
       0  843.91    58.2  833.19   116.4  818.52   135.8  814.56   164.9  810.67
   232.8  804.19     291   793.7   397.7  772.84   407.4  770.58   436.5  761.06
   455.9  756.24   533.6  740.81   562.6  738.73     650  736.75   784.4  739.72
     794  739.52   803.6  737.59   813.2   734.7   822.8   733.8   832.4   734.5
   851.6  741.25   870.8  746.95   918.8  749.89   928.4  751.86  1015.3  793.29
  1044.3  805.75  1102.2  828.16  1218.1  880.41    1247  889.73  1343.6  912.45
#Mann= 3 , 0 , 0
       0     .05       0   803.6    .045       0   851.6     .08       0
Bank Sta=803.6,851.6
XS Rating Curve= 0 ,0
Exp/Cntr=0.3,0.1

Type RM Length L Ch R = 1 ,70356.7 ,73.7,73.7,73.7
XS GIS Cut Line= 4
      1905003.79      634127.222      1905222.54      634606.388
     1905230.353      634817.326     1905631.394      635127.222
#Sta/Elev= 30
       0  828.27      39  824.84     117   822.6   146.3   816.5   234.1  806.26
   253.6  800.41   282.9  782.24   302.4  772.73   370.7  751.57   429.2  746.38
   497.5  745.32   526.7  741.05   545.9  740.01   613.1  737.72   641.9  738.99
   661.1   734.1   670.7  733.46   699.4  741.88   728.2  747.79     806  750.88
   815.8  754.45   825.5  760.23   854.8   780.8   864.5  785.97     884  793.24
   903.5  797.85    1001  814.19  1137.4  848.69  1205.7  862.62  1244.6  876.13
#Mann= 3 , 0 , 0
       0     .05       0   641.9    .045       0   699.4     .08       0
Bank Sta=641.9,699.4
XS Rating Curve= 0 ,0
Exp/Cntr=0.3,0.1

Type RM Length L Ch R = 1 ,70283   ,216.9,200.4,184.2
XS GIS Cut Line= 4
     1904930.873      634148.055     1905149.623      634627.222
     1905157.436      634838.159     1905558.478      635148.055
#Sta/Elev= 30
       0  879.47      78  869.01   107.3  860.03   156.1  842.22   214.6  823.34
   234.1  814.91   282.9  786.55   292.6  781.82   360.9  752.52   370.7  749.68
   487.7   743.9   584.3  743.11   613.1  739.93   641.9  733.63   651.5  733.62
   661.1  736.78   670.7  741.74     709  746.06   815.8  751.37   825.5  755.73
   835.3   763.1     845  768.26   854.8  771.94   893.8  774.27     923  777.55
   952.2  781.49  1010.7  791.94  1176.4  830.82  1205.7  836.91  1244.6   843.1
#Mann= 3 , 0 , 0
       0     .05       0   613.1    .045       0   670.7     .07       0
Bank Sta=613.1,670.7
XS Rating Curve= 0 ,0
Exp/Cntr=0.3,0.1

Type RM Length L Ch R = 1 ,70082.6 ,255.8,237.5,226.2
XS GIS Cut Line= 4
     1904350.144      634343.368     1904876.186      634676.701
     1905045.457      634877.222     1905519.415      635150.659
#Sta/Elev= 30
       0  803.23    48.6  804.29    68.1  806.93    97.3  812.78   126.5   814.6
   282.2  814.28     399  818.74   408.7  818.38   418.4   815.9   437.9  806.81
   515.7  761.66   544.9  748.78   554.6  745.83   564.4  744.84     613  745.93
   651.9  745.13   700.5  742.88     720  740.42   739.4  733.14   749.1  731.94
   758.7  732.76     788  738.95   817.1  742.13  1031.7  749.79  1109.9  754.99
  1129.4  757.26    1149  760.76  1227.2  779.28    1364  816.17  1432.4   832.5
#Mann= 3 , 0 , 0
       0     .07       0     720    .045       0     788     .06       0
Bank Sta=720,788
XS Rating Curve= 0 ,0
Exp/Cntr=0.3,0.1

Type RM Length L Ch R = 1 ,69845.1 ,417,412.4,401.4
XS GIS Cut Line= 3
     1904427.596      634944.691     1904832.869      634944.704
     1905530.893      635180.542
#Sta/Elev= 30
       0  896.33    19.3  883.72    57.9   860.2    77.2  847.05    86.8  842.36
   115.8     833   125.4     829   183.3  802.02   231.6     781   241.2  777.61
   279.8  769.04   366.7  742.73     386  736.09   395.6  732.67   405.3  731.13
   415.1  731.83   434.7     737   454.4  739.59   513.3  743.94   591.9  745.73
     700  745.95   739.3  746.66   778.6  748.44   837.5   753.7   896.5  762.57
   925.9  770.82  1043.8  807.79  1092.9  822.33  1122.4   829.4  1142.1   831.4
#Mann= 3 , 0 , 0
       0     .08       0     386    .045       0   434.7     .05       0
Bank Sta=386,434.7
XS Rating Curve= 0 ,0
Exp/Cntr=0.3,0.1

Type RM Length L Ch R = 1 ,69432.7 ,210.9,211.5,210.7
XS GIS Cut Line= 4
     1904391.811      635327.743     1904857.957      635348.576
     1905021.816      635314.623     1905541.157      635275.548
#Sta/Elev= 30
       0  929.24      68  923.72    87.5  921.17    97.2  918.44   155.5  896.56
   213.9  876.52   281.9  851.29   408.3  797.91   447.2   782.9   531.7  736.94
     541  732.81   550.3  731.12   559.6  731.83   578.2   736.7   596.8   740.1
   624.6  743.51   673.3  744.83   712.6  746.84     742  746.74     801  744.49
     860  745.18   879.6  746.34   889.4  747.72   928.8  758.13  1007.4  775.66
  1017.2  778.72    1027  782.71  1056.5  796.41  1076.2  804.33  1154.8  830.36
#Mann= 3 , 0 , 0
       0      .1       0   531.7    .045       0   578.2     .05       0
Bank Sta=531.7,578.2
XS Rating Curve= 0 ,0
Exp/Cntr=0.3,0.1

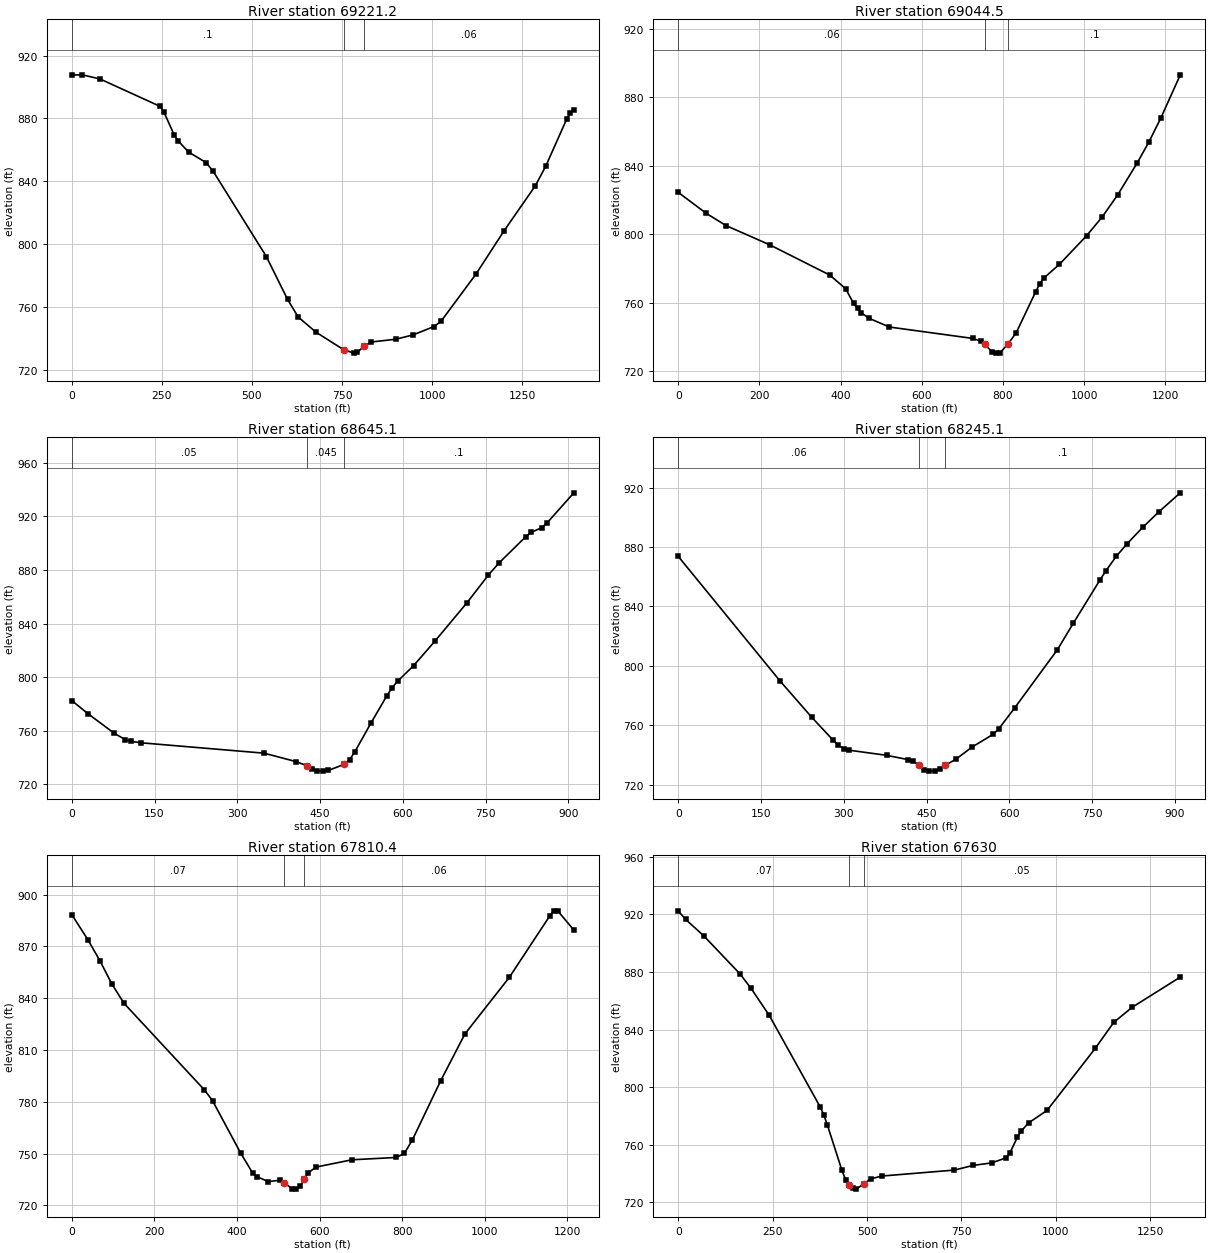
Type RM Length L Ch R = 1 ,69221.2 ,178.1,176.7,175.2
XS GIS Cut Line= 4
     1904300.665      635366.805     1904980.353      635520.451
     1905147.019       635476.18     1905652.228      635338.159
#Sta/Elev= 30
       0  907.62    29.4  907.75    78.5   905.1   245.4  887.66   255.2  884.29
   284.6  869.33   294.4  865.92   323.9   858.7     373   851.9   392.6  846.34
   539.8  792.24   598.7  765.01   628.1  753.83   677.2   744.2   754.3  733.01
   783.1  730.83   792.6  731.42   811.8  735.36     831  737.91   898.4  739.65
   946.9   742.4  1005.1  747.75  1024.5  751.07  1121.4  781.06    1199  808.45
  1286.3  837.26  1315.4  849.87  1373.6  879.82  1383.3  883.52    1393  885.25
#Mann= 3 , 0 , 0
       0      .1       0   754.3    .045       0   811.8     .06       0
Bank Sta=754.3,811.8
XS Rating Curve= 0 ,0
Exp/Cntr=0.3,0.1

Type RM Length L Ch R = 1 ,69044.5 ,396.3,399.4,402.6
XS GIS Cut Line= 4
     1904480.353      635908.472      1905097.54      635629.826
     1905321.687      635568.021     1905637.399      635482.525
#Sta/Elev= 30
       0  824.41    68.7  812.22   117.8  805.01   225.7  793.73   372.9  776.15
   412.2  768.18   431.8  759.62   441.6  756.61   451.4  753.94   471.1  750.73
   520.2  745.73   725.6  739.07     745  737.46   754.7  735.69     774  731.06
   783.7  730.48   793.4  730.82   812.8  736.01   832.2  742.19   880.6   766.4
   890.3  770.87     900  774.24   938.6  782.28  1005.9  799.07  1044.4  810.07
  1082.8  823.05    1131  841.78  1159.8  854.02  1188.7  867.82  1236.8  893.11
#Mann= 3 , 0 , 0
       0     .06       0   754.7    .045       0   812.8      .1       0
Bank Sta=754.7,812.8
XS Rating Curve= 0 ,0
Exp/Cntr=0.3,0.1

Type RM Length L Ch R = 1 ,68645.1 ,401.8,400,398.2
XS GIS Cut Line= 3
     1904806.144      636053.524     1905257.356       635994.94
     1905708.569      635936.355
#Sta/Elev= 30
       0  782.59      29  772.88    77.4  758.04    96.8  753.49   106.5  752.18
   125.8  751.06   348.5  743.33   406.6  737.02     426  734.03   435.6   731.7
   445.3  730.26     455  729.93   464.7  730.42   493.7  734.95   503.4  738.45
   513.1  744.37   542.1  765.69   571.2  786.24   580.8  792.26   590.5  797.01
   619.6  808.62   658.3  826.96   716.4   855.6   755.1  876.23   774.5   885.3
   822.9  904.87   832.6  908.06   851.9   911.6   861.6  915.22     910  937.57
#Mann= 3 , 0 , 0
       0     .05       0     426    .045       0   493.7      .1       0
Bank Sta=426,493.7
XS Rating Curve= 0 ,0
Exp/Cntr=0.3,0.1

Type RM Length L Ch R = 1 ,68245.1 ,437.6,434.7,431.7
XS GIS Cut Line= 3
     1904863.748      636485.644     1905308.714      636390.617
      1905753.68      636295.589
#Sta/Elev= 30
       0  873.69   183.9  790.18     242  765.49   280.7   750.1   290.4  746.65
   300.1  744.38   309.8  743.36   377.6  739.92   416.3  737.05     426  735.89
   435.6   733.1   445.3   730.1     455  729.29   464.7  729.42   474.4  730.98
     484  733.22   503.4  737.36   532.4  745.42   571.2  754.16   580.8  757.66
   609.9  771.86   687.3  810.97   716.4  828.95   764.8  858.07   774.5  863.66
   793.8  873.65   813.2  882.06   842.2  893.32   871.3   903.7     910  916.42
#Mann= 3 , 0 , 0
       0     .06       0   435.6    .045       0     484      .1       0
Bank Sta=435.6,484
XS Rating Curve= 0 ,0
Exp/Cntr=0.3,0.1

Type RM Length L Ch R = 1 ,67810.4 ,173.6,180.4,187
XS GIS Cut Line= 4
     1904865.769      636835.555     1905274.623      636840.763
     1905506.394      636778.263     1905946.498      636421.493
#Sta/Elev= 30
       0  888.45    38.9  873.89    68.2  861.65    97.4  848.06   126.6     837
   321.3  786.82   340.7  780.65   408.9  750.28   437.7  738.83   447.3  736.72
   476.1  733.74   504.9  734.61   514.5  733.04   533.7  729.61   543.3  729.41
   552.9  731.15   562.5     735   572.1  738.79   591.3  742.18   678.2   746.4
   785.7  747.76   805.2  750.07   824.8  758.01   893.1  792.16   951.8  819.29
  1059.2  852.03  1156.9  887.53  1166.6  890.52  1176.4  890.59  1215.5  879.45
#Mann= 3 , 0 , 0
       0     .07       0   514.5    .045       0   562.5     .06       0
Bank Sta=514.5,562.5
XS Rating Curve= 0 ,0
Exp/Cntr=0.3,0.1

Type RM Length L Ch R = 1 ,67630   ,518.5,513.4,508.2
XS GIS Cut Line= 4
     1904873.582       637007.43     1905277.228       636976.18
      1905535.04      636965.763     1906199.103      636905.868
#Sta/Elev= 30
       0  922.47    19.3  916.57    67.5  905.12   163.9  878.54   192.8  868.62
     241  849.83   375.9  786.23   385.6  780.63   395.2  773.46   433.5  742.12
   443.1  735.71   452.6  731.72   462.2  729.63   471.8   729.1   490.9  732.72
     510  736.22   538.6  738.18   731.5  742.33   780.5  745.58   829.6   747.3
   868.8  750.87   878.6  754.46   898.2   765.2     908  769.35   927.6  775.08
   976.6  783.76  1104.1  826.82  1153.1   844.9  1202.2  855.47  1329.6  876.44
#Mann= 3 , 0 , 0
       0     .07       0   452.6    .045       0   490.9     .05       0
Bank Sta=452.6,490.9
XS Rating Curve= 0 ,0
Exp/Cntr=0.3,0.1

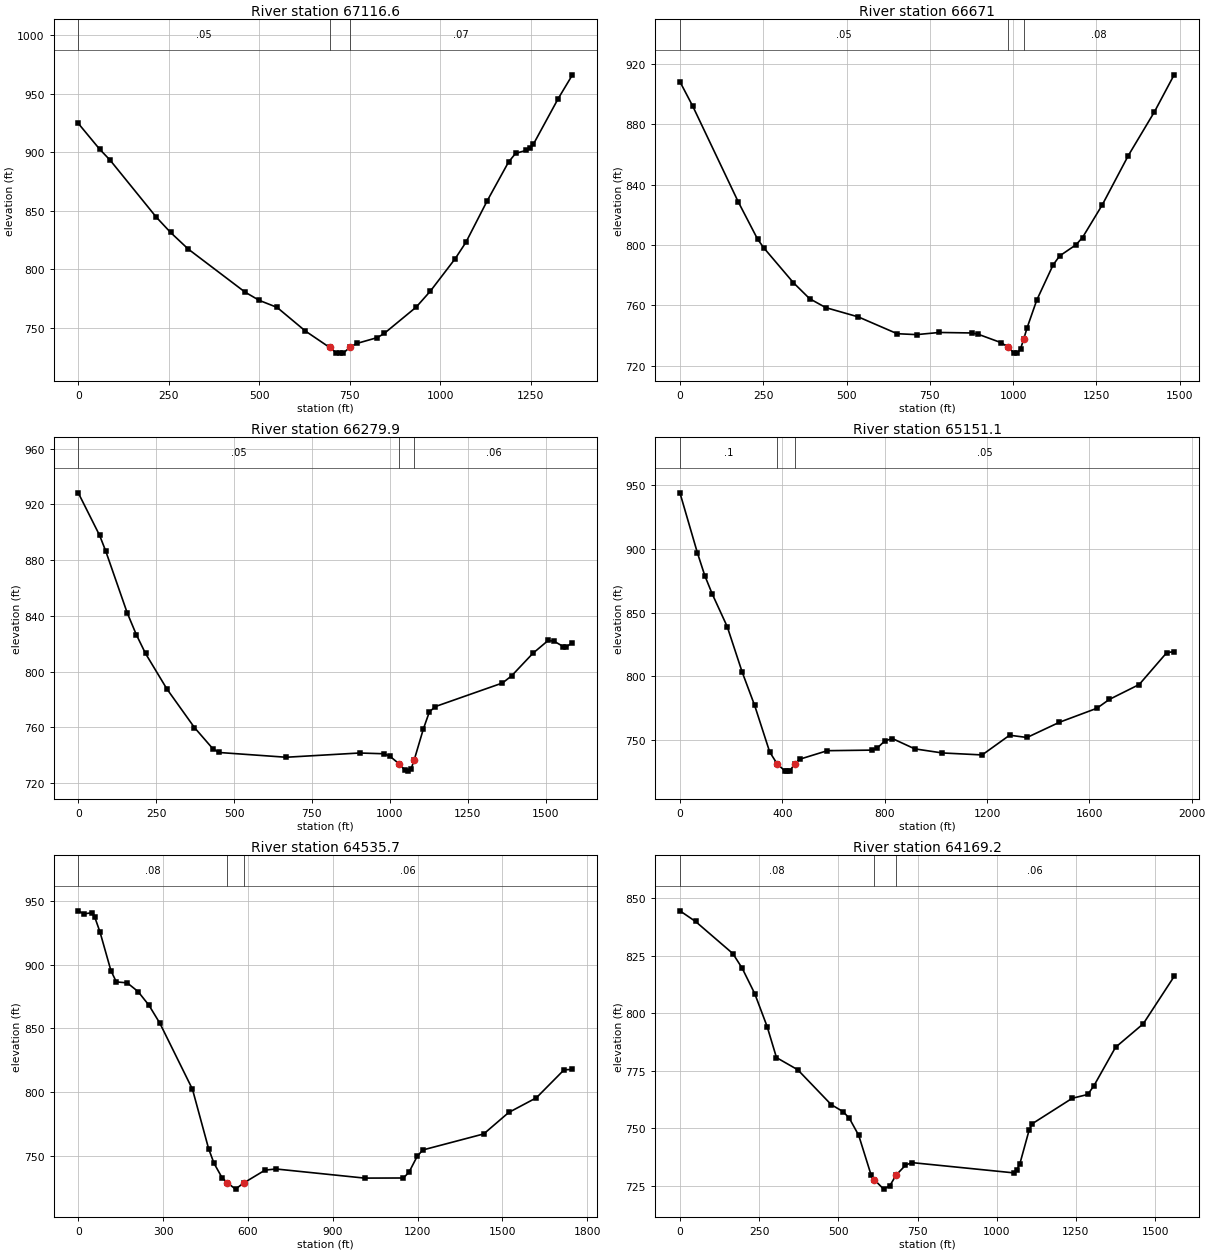
Type RM Length L Ch R = 1 ,67116.6 ,433.8,445.6,457.8
XS GIS Cut Line= 4
     1904907.147       637125.32     1905453.443      637472.708
     1905653.964       637418.02     1906159.172      637345.104
#Sta/Elev= 30
       0  924.58    58.8  902.64    88.3  893.06   215.8  844.44     255  831.48
   304.1  817.21     461  780.48   500.3  773.43   549.3  767.47   627.8  747.24
   694.6  733.26   713.5  728.58     723   728.4   732.4   728.4   751.3   733.6
   770.2   736.7   826.9  741.69   845.8  745.28   933.8  767.67     973  781.32
  1041.8  809.11  1071.2  822.99  1130.1  858.44    1189   891.5  1208.6  898.97
  1238.1  901.52  1247.9  903.16  1257.7  906.74  1326.4  945.78  1365.7  966.02
#Mann= 3 , 0 , 0
       0     .05       0   694.6    .045       0   751.3     .07       0
Bank Sta=694.6,751.3
XS Rating Curve= 0 ,0
Exp/Cntr=0.3,0.1

Type RM Length L Ch R = 1 ,66671   ,372.7,391.2,409.1
XS GIS Cut Line= 4
     1904873.582      637241.805     1905474.276       637824.27
     1905747.714      637897.187     1906109.693      637928.437
#Sta/Elev= 30
       0  908.07    38.9  891.68   175.1  828.52   233.5   803.7     253  797.76
   340.5  775.07   389.2  764.48   437.8  758.56   535.1  752.45   651.9  741.31
   710.2  740.71   778.3  742.13   875.8   741.8   895.3  740.93   963.6   735.4
   983.1   732.7  1002.6  728.61  1012.4  728.46  1022.1  731.26  1031.9  737.93
  1041.6  745.09  1070.9  763.59  1119.7  786.77  1139.4  792.76  1188.4  800.12
  1208.1  804.96    1267   826.4  1345.6  859.21  1424.1  888.19    1483   912.6
#Mann= 3 , 0 , 0
       0     .05       0   983.1    .045       0  1031.9     .08       0
Bank Sta=983.1,1031.9
XS Rating Curve= 0 ,0
Exp/Cntr=0.3,0.1

Type RM Length L Ch R = 1 ,66279.9 ,1135.9,1128.8,1122
XS GIS Cut Line= 4
     1904764.207      637267.847     1905295.457      638010.034
     1905399.623      638197.534     1905855.353      638140.243
#Sta/Elev= 30
       0  928.37    68.7  897.74    88.3  886.48     157  842.26   186.5  826.47
   215.9  812.99   284.6  787.49   372.9  759.81   431.8  744.62   451.5  741.88
   667.4  738.45   902.9   741.5     981  740.95  1000.5  739.19  1029.7  733.76
  1049.2  729.05    1059  728.48  1068.7   730.2  1078.5  736.56  1107.7  758.63
  1127.2  771.07  1146.8  774.88  1361.8  791.78  1391.1   796.9  1459.5   813.1
  1508.4  822.31  1527.9  821.75  1557.2  817.92    1567   817.8  1586.5  820.79
#Mann= 3 , 0 , 0
       0     .05       0  1029.7    .045       0  1078.5     .06       0
Bank Sta=1029.7,1078.5
XS Rating Curve= 0 ,0
Exp/Cntr=0.3,0.1

Type RM Length L Ch R = 1 ,65151.1 ,638.9,615.4,591.5
XS GIS Cut Line= 5
     1904344.936      637452.743     1904532.436       637663.68
     1904730.353      637853.784     1904876.186      638299.097
     1905774.623      638181.909
#Sta/Elev= 30
       0  944.16    68.1  897.14    97.3  879.01   126.5  864.56   184.9  838.96
   243.3  803.24     292  777.07   350.8  740.48   380.2  731.04   409.6  725.74
   419.4  725.41   429.2  725.62   448.8  731.05   468.4  734.79   576.2  741.48
   751.9  741.93   771.4  743.62   800.7  749.13     830  751.03   917.8  742.91
  1025.2   739.7  1181.1  738.14  1288.3  753.63  1356.5  751.86  1483.1  763.82
  1629.3   774.8    1678  781.76  1794.9   793.5  1902.1  818.46  1931.3  819.43
#Mann= 3 , 0 , 0
       0      .1       0   380.2    .045       0   448.8     .05       0
Bank Sta=380.2,448.8
XS Rating Curve= 0 ,0
Exp/Cntr=0.3,0.1

Type RM Length L Ch R = 1 ,64535.7 ,386,366.5,347
XS GIS Cut Line= 5
     1904110.561      638239.201     1904488.165       638382.43
     1904732.957      638304.305     1904883.998      638392.847
     1905774.623      638197.534
#Sta/Elev= 30
       0  942.11    19.2  939.71    48.1  940.58    57.7  937.58    76.9  925.49
   115.4  895.29   134.6  886.37   173.1  885.62   211.5  878.81     250  868.06
   288.5  853.99   403.9  802.18     461  755.57     480  744.15   508.5  732.81
   527.6   728.8   556.1  723.85   584.7  728.63   660.8  738.78   699.7  739.64
  1012.4   732.5  1149.6  732.58  1169.2  736.94  1198.6  749.55  1218.3  754.55
    1434  767.15  1522.2  783.95  1620.2   795.5  1718.3  817.49  1747.7  817.68
#Mann= 3 , 0 , 0
       0     .08       0   527.6    .045       0   584.7     .06       0
Bank Sta=527.6,584.7
XS Rating Curve= 0 ,0
Exp/Cntr=0.3,0.1

Type RM Length L Ch R = 1 ,64169.2 ,127.7,109.2,90.7
XS GIS Cut Line= 5
     1904477.748      638741.805     1904764.207      638845.972
     1904891.811      638642.847     1904985.127      638436.684
     1905743.373      638218.368
#Sta/Elev= 30
       0  844.58    49.2  839.96   167.2  825.96   196.6  819.59     236   808.6
   275.3  794.23   304.8  780.72     372  775.42   477.5  760.27   515.9  757.13
   535.1  754.25   564.4  746.88   603.7  729.54   613.6  727.59   643.1  723.49
   662.8     725   682.4   729.6     712  733.88   731.6  735.04  1053.5  730.57
  1063.2  731.82    1073   734.5  1102.2  749.12  1111.9  751.92  1238.6  763.04
  1287.3  764.67  1306.8  768.46    1375  785.19  1462.6  795.43    1560  816.02
#Mann= 3 , 0 , 0
       0     .08       0   613.6    .045       0   682.4     .06       0
Bank Sta=613.6,682.4
XS Rating Curve= 0 ,0
Exp/Cntr=0.3,0.1