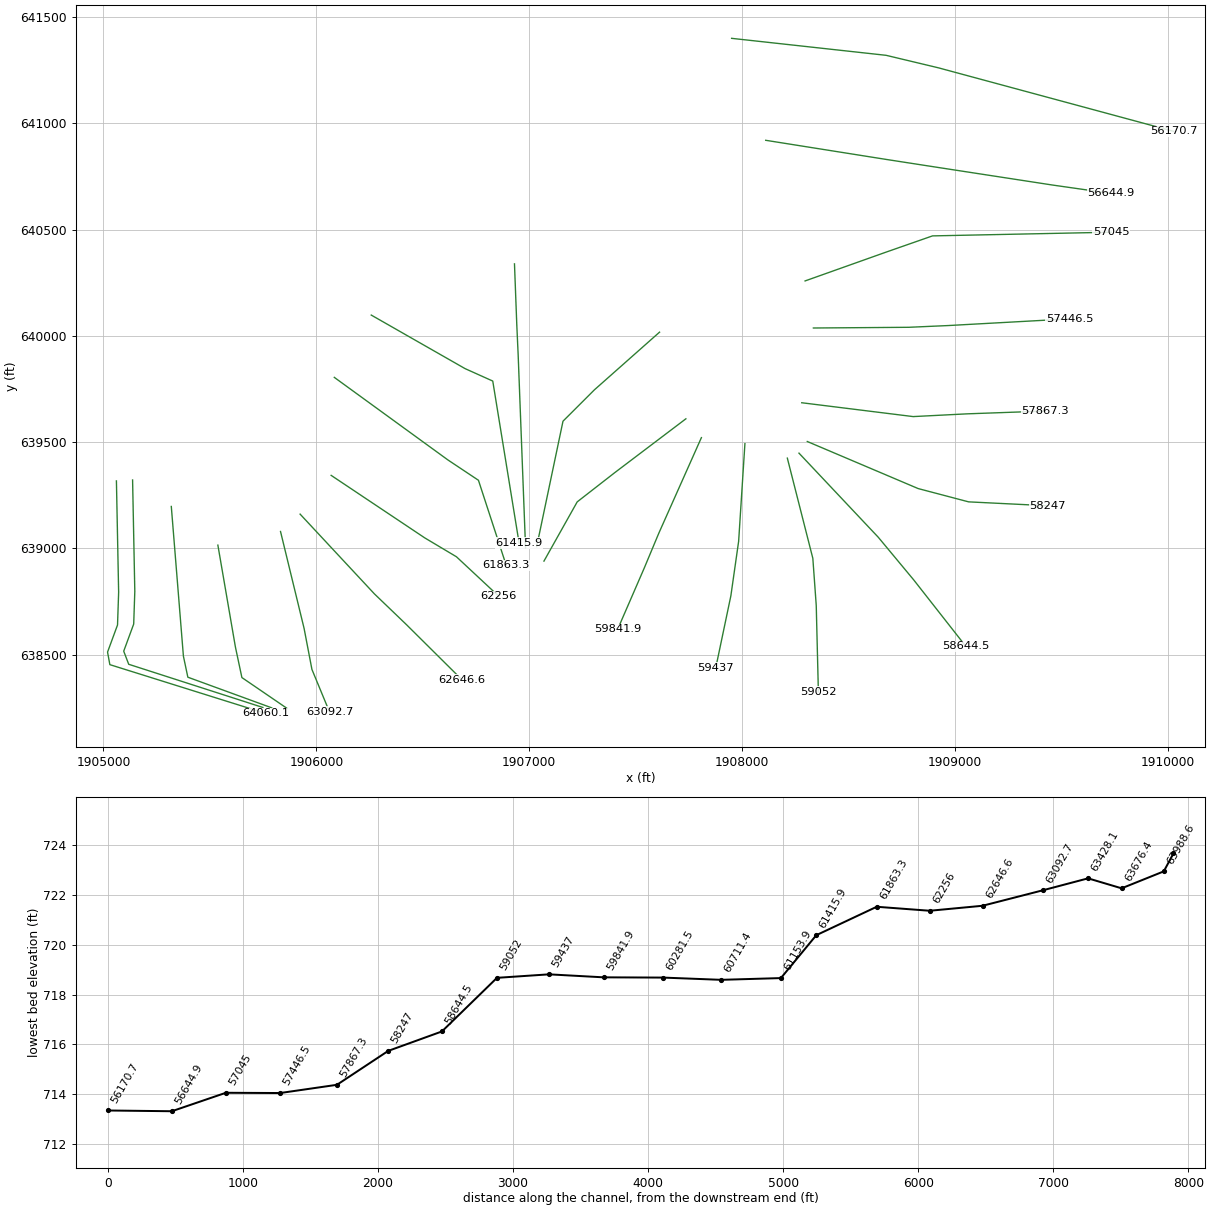
HEC-RAS study HenryFork.prj: HenryFork

--- HenryFork.g01 (geometry) --- (continued)

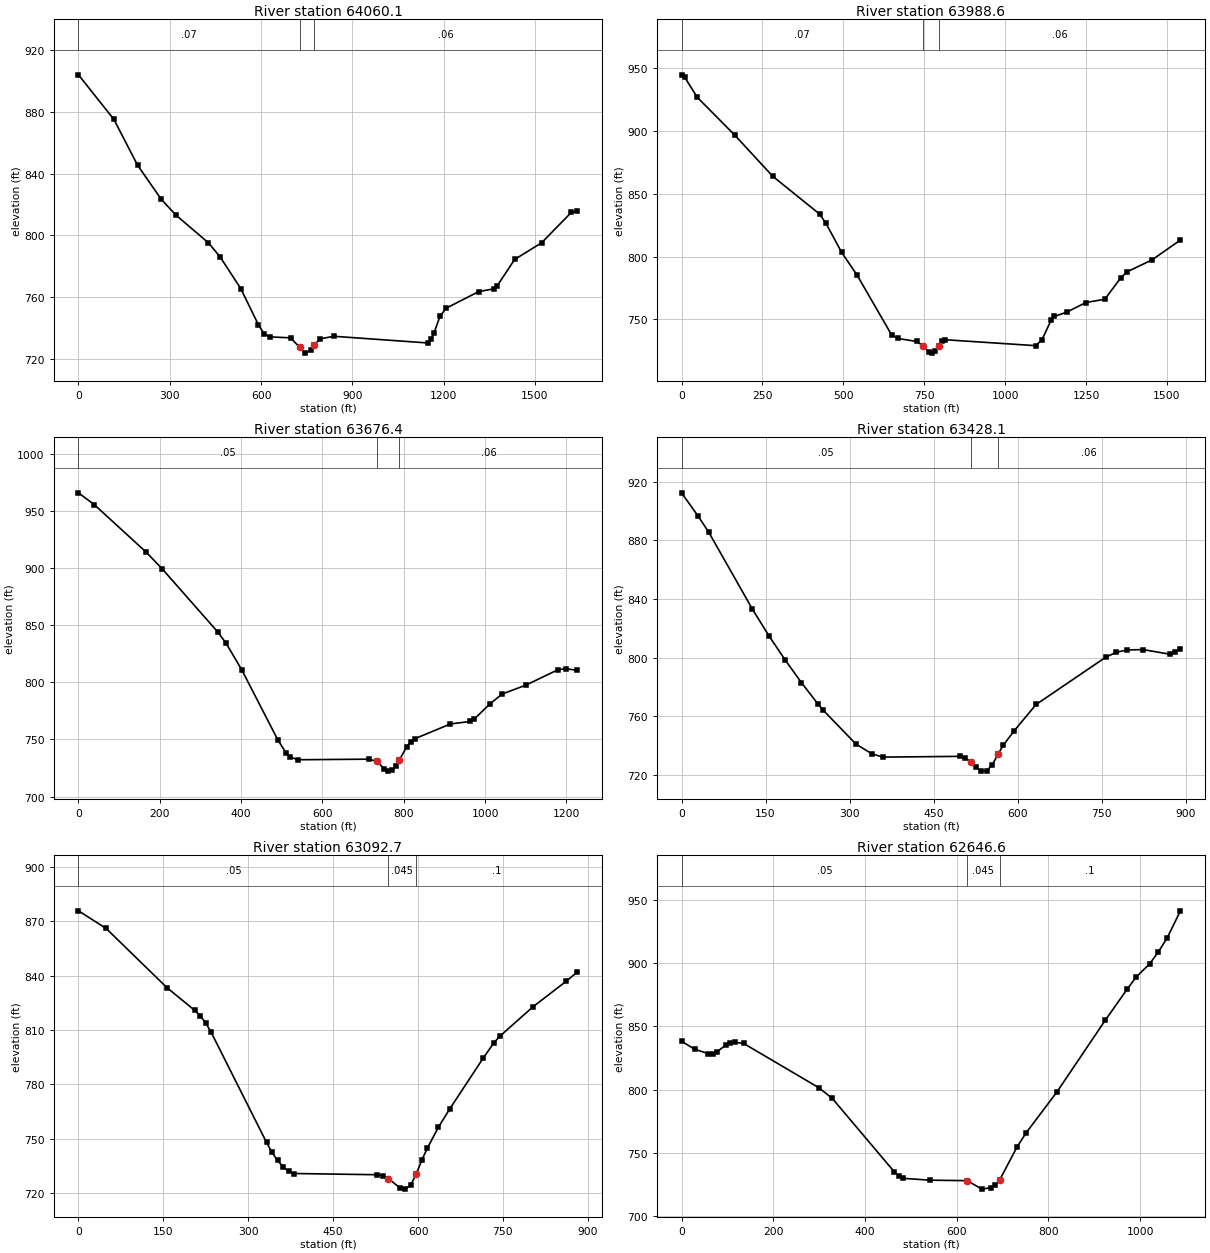
Type RM Length L Ch R = 1 ,64060.1 ,70.6,71.5,72.4
XS GIS Cut Line= 6
     1905061.082       639317.76     1905071.498      638793.888
      1905066.29      638640.243     1905019.415      638512.638
     1905030.266      638453.611     1905761.169      638224.444
#Sta/Elev= 30
       0  904.09   116.4  875.16   194.1  845.54   271.7  823.46   320.2  813.15
   426.9   795.2   465.8  785.93   533.6   765.4   591.2  742.04   610.4  736.01
   629.7  734.16   697.1  733.59   726.3   727.5   745.7  723.66   765.1  725.59
   774.8  729.14   794.2  732.91   839.4  734.58  1148.6  730.24  1158.5  732.58
  1168.3  736.75  1187.9  747.52  1207.6  752.75  1315.6  763.58  1364.7  765.33
  1374.5  766.88  1433.4  784.42  1521.8  795.19    1620     815  1639.6  815.66
#Mann= 3 , 0 , 0
       0     .07       0   726.3    .045       0   774.8     .06       0
Bank Sta=726.3,774.8
XS Rating Curve= 0 ,0
Exp/Cntr=0.3,0.1

Type RM Length L Ch R = 1 ,63988.6 ,299.5,312.2,324.9
XS GIS Cut Line= 6
     1905137.037        639322.1     1905147.453      638798.229
     1905142.245      638644.583      1905095.37      638516.979
     1905118.807      638455.347     1905749.016      638252.222
#Sta/Elev= 30
       0  944.91     9.7  943.05    48.5  927.03     165  896.68   281.4   864.1
   426.9  833.79   446.4  826.43   494.9  803.26   543.2  784.87   648.9  737.58
   668.1  734.65   726.3  732.26   745.7   728.9   765.1  723.53   774.8  722.94
   784.5  724.85   794.2  729.01   803.9  732.64   813.6  733.64  1093.8   728.9
  1113.3  733.36  1142.5  749.51  1152.2  752.18  1191.2  755.73  1249.6  763.32
    1308  765.91  1356.7   782.8  1376.2  787.73  1454.1  797.34  1541.7  813.19
#Mann= 3 , 0 , 0
       0     .07       0   745.7    .045       0   794.2     .06       0
Bank Sta=745.7,794.2
XS Rating Curve= 0 ,0
Exp/Cntr=0.3,0.1

Type RM Length L Ch R = 1 ,63676.4 ,248.1,248.3,248.2
XS GIS Cut Line= 4
     1905318.894      639197.534     1905375.752      638493.541
     1905396.585      638394.583     1905790.682      638250.486
#Sta/Elev= 30
       0  966.17    39.2   955.7   166.8  914.05     206  899.48   343.3  843.89
     363  834.32   402.2  810.58   490.5  749.42   510.1   738.5   519.9  734.69
   539.5  732.24   715.5  732.74   733.9  730.72   752.2  724.24   761.4  722.26
   770.6  722.83   779.8  726.36     789  731.93   807.4  743.78   817.2  748.03
   826.9  750.62   914.8  763.62   963.6   765.8   973.3   767.9  1012.3  781.34
  1041.6  789.78  1100.2  797.63  1178.2  810.98  1197.8  812.13    1227  810.49
#Mann= 3 , 0 , 0
       0     .05       0   733.9    .045       0     789     .06       0
Bank Sta=733.9,789
XS Rating Curve= 0 ,0
Exp/Cntr=0.3,0.1

Type RM Length L Ch R = 1 ,63428.1 ,335.8,335.4,334.9
XS GIS Cut Line= 4
     1905537.644      639015.677      1905620.11      638536.076
     1905650.492      638392.847     1905863.165      638247.447
#Sta/Elev= 30
       0   912.3    29.2  896.68    48.7  885.41   126.5  833.07   155.7  815.04
   184.9  798.48   214.1  782.97   243.3  768.54     253  764.14   311.4  741.08
   340.6   734.3   360.1  732.21   496.4  732.73   506.2   731.7   515.9  728.94
   525.7  725.19   535.4  722.66   545.2  723.05     555   727.1   564.7     734
   574.5  740.34     594  750.25     633  768.07   757.1  800.23   776.2  803.67
   795.3  805.22   823.9  805.48   871.6  802.35   881.1   803.5   890.7  805.94
#Mann= 3 , 0 , 0
       0     .05       0   515.9    .045       0   564.7     .06       0
Bank Sta=515.9,564.7
XS Rating Curve= 0 ,0
Exp/Cntr=0.3,0.1

Type RM Length L Ch R = 1 ,63092.7 ,432,446,459.9
XS GIS Cut Line= 4
     1905831.915      639079.913     1905942.592      638624.184
     1905979.485      638431.041      1906061.95      638231.388
#Sta/Elev= 30
       0  875.75    48.8  866.04   156.3  833.36   205.2  820.86     215  817.87
   224.7   813.9   234.5  808.68   332.2  747.98     342  742.44   351.7  737.99
   361.5  734.52   371.3  731.96     381   730.8     528  730.12   537.8  729.59
   547.6  728.01   567.3  723.03   577.1  722.18     587  724.44   596.8  730.54
   606.6  738.19   616.4  744.78   636.1  756.42   655.8  766.34   714.7   794.3
   734.3  803.04   744.2  806.48   803.1   822.8     862  836.96   881.6  842.05
#Mann= 3 , 0 , 0
       0     .05       0   547.6    .045       0   596.8      .1       0
Bank Sta=547.6,596.8
XS Rating Curve= 0 ,0
Exp/Cntr=0.3,0.1

Type RM Length L Ch R = 1 ,62646.6 ,387.2,390.6,395.6
XS GIS Cut Line= 4
     1905923.929       639161.51     1906272.887       638786.51
     1906424.241      638641.006     1906683.768         638383.
#Sta/Elev= 30
       0  838.29      29  831.97      58  828.53    67.7  828.43    77.3  829.99
    96.6  835.26   106.3  836.85     116  837.52   135.3  836.59   299.6   801.6
   328.6  793.27   463.9  735.29   473.6  731.84   483.2   730.1   540.9  728.64
   622.9  728.23   655.4  721.56   674.5  722.72     684   724.6   693.6   728.6
   731.8  754.87   751.1  765.75   818.5  798.13   924.4  854.99   972.6  879.73
   991.8  889.08  1020.7  899.29    1040  908.82  1059.3  919.98  1088.2  941.25
#Mann= 3 , 0 , 0
       0     .05       0   622.9    .045       0   693.6      .1       0
Bank Sta=622.9,693.6
XS Rating Curve= 0 ,0
Exp/Cntr=0.3,0.1

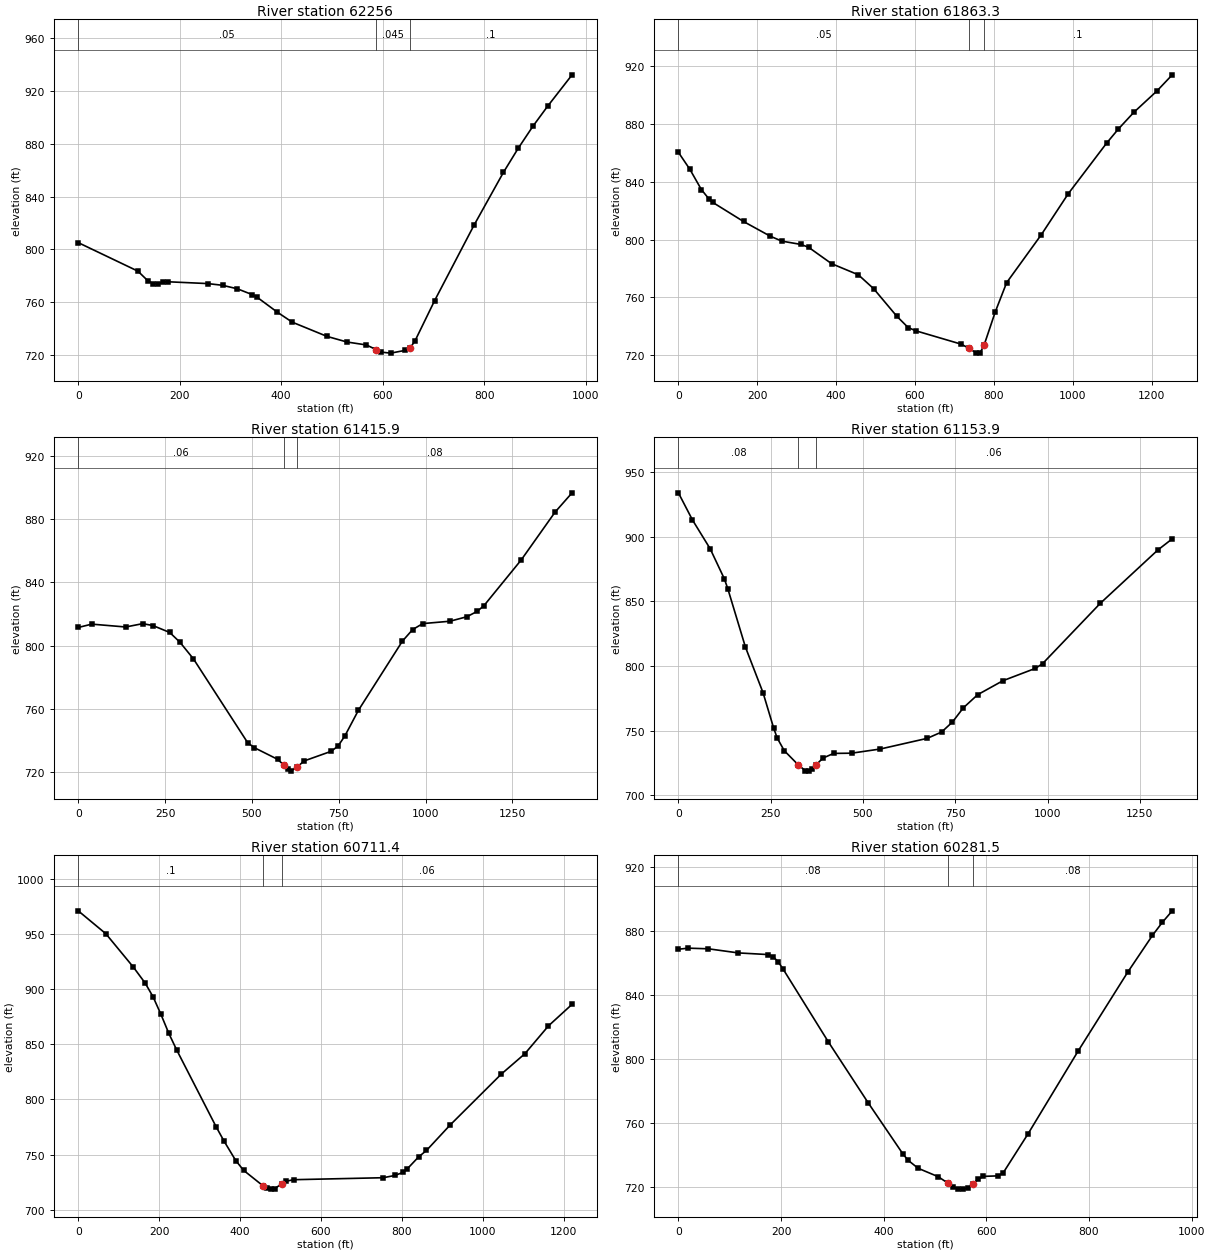
Type RM Length L Ch R = 1 ,62256   ,390.9,392.7,390.1
XS GIS Cut Line= 4
     1906069.762      639343.802     1906509.867      639049.531
     1906658.304      638960.989     1906856.221      638776.093
#Sta/Elev= 30
       0  805.13   117.6   783.5   137.3  776.17   147.1  774.12   156.9  773.86
   166.7  775.27   176.5  775.46   254.9  774.09   284.3  772.79   313.7   770.1
   343.1  765.68     353  763.58   392.2  752.43   421.6  744.85   490.2  734.05
   529.4   729.8   567.8  727.55     587  724.05   596.6  722.13   615.8  721.36
   644.6  723.49   654.2   725.4   663.8  730.81   702.3  761.22   779.6  818.15
   837.7  858.31   866.7  876.51   895.7  893.24   924.7  908.43   973.1  932.34
#Mann= 3 , 0 , 0
       0     .05       0     587    .045       0   654.2      .1       0
Bank Sta=587,654.2
XS Rating Curve= 0 ,0
Exp/Cntr=0.3,0.1

Type RM Length L Ch R = 1 ,61863.3 ,443.7,447.4,451.7
XS GIS Cut Line= 4
     1906084.519      639804.739     1906618.373      639416.284
     1906761.603      639320.798     1906891.811      638921.493
#Sta/Elev= 30
       0   860.4    29.1  848.65    58.3  834.64    77.7  828.09    87.4  825.72
   165.1  812.56     233  802.39   262.2  798.99   310.7   796.7   330.1  794.74
   388.4   783.4   456.3   775.7   495.2  766.08   553.4  747.18   582.6  739.22
     602  736.97   717.6  727.69   736.7  724.86   755.9  721.52   765.4  721.92
     775  726.86   803.7  750.14   832.4  770.26   920.3  803.41   988.6  831.74
  1086.3  866.88  1115.6  876.47  1154.7  887.99  1213.3  902.76  1252.4     914
#Mann= 3 , 0 , 0
       0     .05       0   736.7    .045       0     775      .1       0
Bank Sta=736.7,775
XS Rating Curve= 0 ,0
Exp/Cntr=0.3,0.1

Type RM Length L Ch R = 1 ,61415.9 ,287,262,236.7
XS GIS Cut Line= 4
      1906258.13      640097.708     1906698.669      639845.972
     1906828.877      639787.378     1906952.575      639025.659
#Sta/Elev= 30
       0  811.44      39  813.56   136.6  811.75   185.4  813.86   214.7  812.69
   263.4  808.28   292.7  802.13   331.8  791.51   487.9  738.38   507.4  735.21
     574  727.87   593.1  724.02   602.6  721.42   612.1  720.38   631.1  723.12
   650.2  726.82   728.3  732.94   747.9  736.24   767.4  742.57   806.5  758.87
   933.5  802.82   962.8  810.12   992.1  813.91  1070.2   815.4    1119  818.25
  1148.4  821.63  1167.9  825.21  1275.4  854.25    1373   884.6  1421.9   896.8
#Mann= 3 , 0 , 0
       0     .06       0   593.1    .045       0   631.1     .08       0
Bank Sta=593.1,631.1
XS Rating Curve= 0 ,0
Exp/Cntr=0.3,0.1

Type RM Length L Ch R = 1 ,61153.9 ,461.4,442.5,423.8
XS GIS Cut Line= 4
     1906930.873      640338.593     1906941.724      640052.135
     1906948.235      639908.906     1906982.957      639001.788
#Sta/Elev= 30
       0  934.14    38.2  913.08      86  890.87   124.2  867.72   133.8  859.94
   181.6  814.69   229.3  779.38     258  752.07   267.6  744.32   286.7  734.52
   324.9  723.45     344  718.96   353.6  718.66   363.1  719.96   372.7   723.5
   391.8  728.78   420.5  732.38   469.1  732.55   547.2   735.8   674.1  744.05
   713.1  748.95   742.4  756.68   771.7  767.62   810.7  777.84     879  788.65
   966.9  798.21   986.4  801.84  1142.6  848.51  1298.8  889.88  1337.8  898.52
#Mann= 3 , 0 , 0
       0     .08       0   324.9    .045       0   372.7     .06       0
Bank Sta=324.9,372.7
XS Rating Curve= 0 ,0
Exp/Cntr=0.3,0.1

Type RM Length L Ch R = 1 ,60711.4 ,430.5,429.9,428.4
XS GIS Cut Line= 4
     1907612.297      640017.413     1907306.307      639746.145
     1907158.738      639598.576      1907035.04      639008.298
#Sta/Elev= 30
       0  971.08    68.2  950.31   136.3  919.99   165.5   905.5     185  893.05
   204.5  877.08   223.9  859.89   243.4  844.82   340.8   775.2   360.2  762.27
   389.4  744.49   408.9   735.6   456.4   721.7   465.8  719.44   475.3  718.59
   485.5   719.1   503.8  723.48   513.3  725.69   532.2  727.14   753.8  728.94
     783  731.01   802.4  733.76   812.2  736.54   841.4  747.86   860.8  753.67
   919.2  776.75  1045.6  822.91    1104  841.42  1162.4  866.74  1220.7  886.26
#Mann= 3 , 0 , 0
       0      .1       0   456.4    .045       0   503.8     .06       0
Bank Sta=456.4,503.8
XS Rating Curve= 0 ,0
Exp/Cntr=0.3,0.1

Type RM Length L Ch R = 1 ,60281.5 ,429.7,439.6,449.4
XS GIS Cut Line= 4
     1907735.995      639609.861     1907402.662      639357.256
     1907225.578      639219.236     1907069.328       638940.59
#Sta/Elev= 30
       0  868.66    19.4  869.32    58.4  868.92   116.7  866.35   175.1  865.31
   184.8  863.95   194.5  860.76   204.2  856.13   291.8  810.92   369.6  772.72
   437.8   740.5   447.5  736.74     467  731.73   506.1  726.46   525.6  722.34
   535.4   720.1   545.1  718.82   554.9  718.68   564.7  719.43   574.4  722.15
   584.2  724.86   593.9  726.66   623.2  726.97     633  728.95   681.5  753.38
   778.3  804.73   875.1  854.14   923.5  877.24   942.9  885.46   962.2  892.66
#Mann= 3 , 0 , 0
       0     .08       0   525.6    .045       0   574.4     .08       0
Bank Sta=525.6,574.4
XS Rating Curve= 0 ,0
Exp/Cntr=0.3,0.1

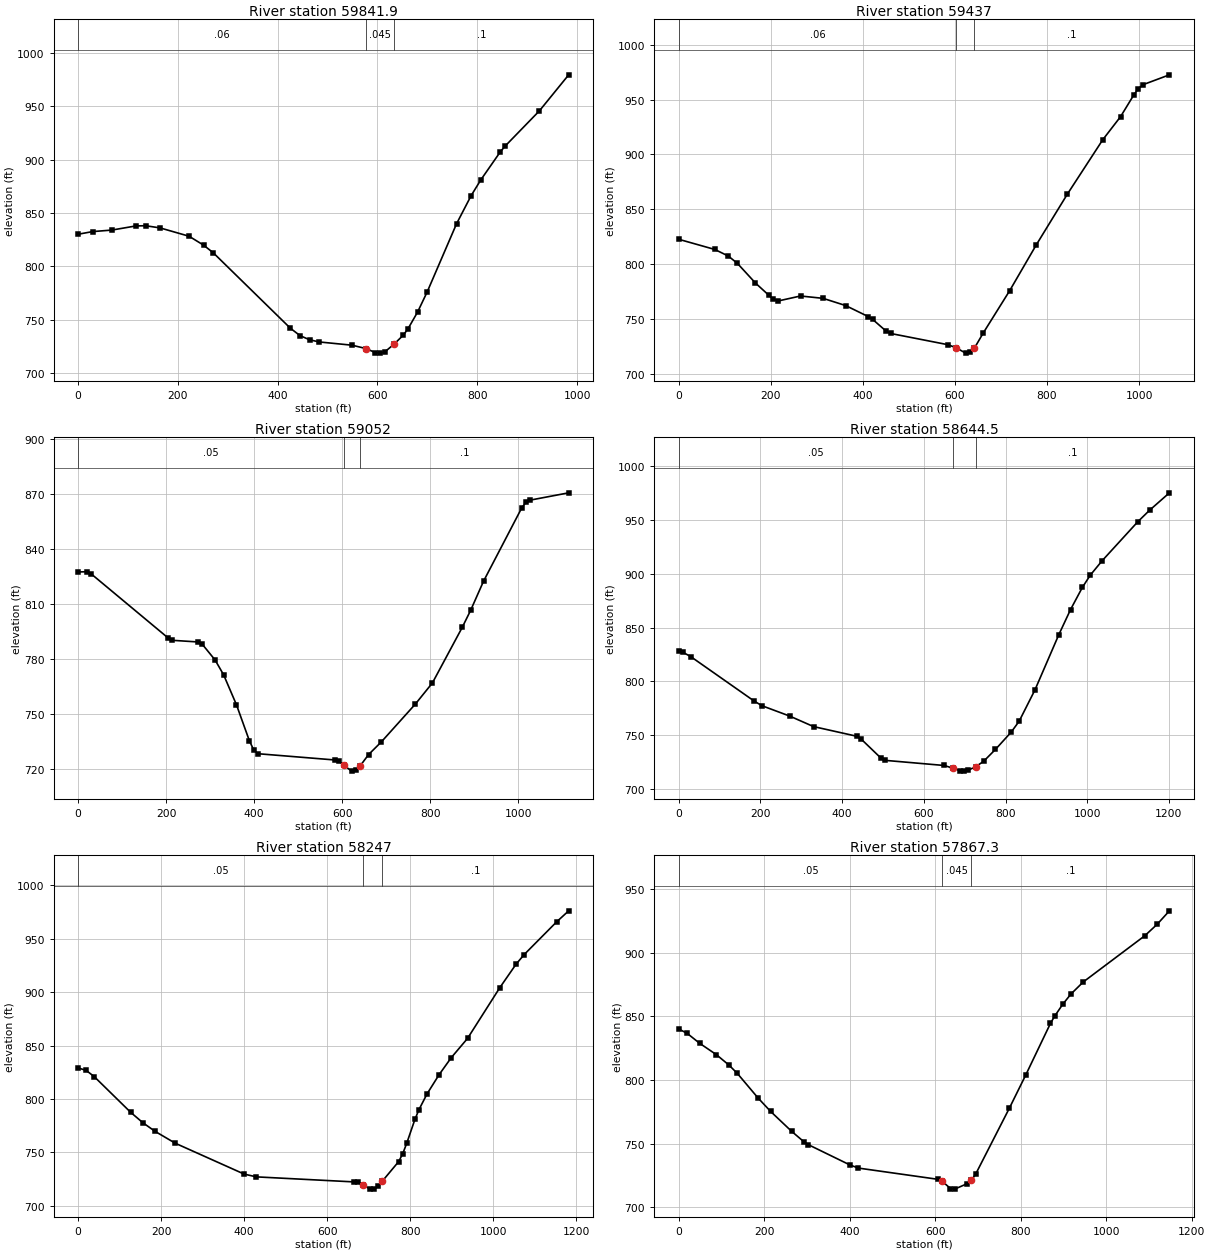
Type RM Length L Ch R = 1 ,59841.9 ,399.3,405,410.7
XS GIS Cut Line= 4
     1907808.912      639521.319     1907608.391      639070.798
     1907540.036      638906.976     1907415.682      638620.277
#Sta/Elev= 30
       0  830.18      29  832.66    67.7   834.1     116  837.98   135.4  838.17
   164.4  836.12   222.4  828.32   251.4     820   270.7  812.89   425.4  742.07
   444.8   735.1   464.1  731.19   483.5  729.16   549.2  726.12   577.2  722.94
   595.9  719.13   605.2  718.69   614.6  719.82   633.3  727.13     652  735.66
   661.3  741.62   680.4   757.2   699.9  776.38   758.5  840.03   787.8  866.48
   807.4  881.38   846.4   907.6   856.2  913.02   924.6  945.96   983.2  979.69
#Mann= 3 , 0 , 0
       0     .06       0   577.2    .045       0   633.3      .1       0
Bank Sta=577.2,633.3
XS Rating Curve= 0 ,0
Exp/Cntr=0.3,0.1

Type RM Length L Ch R = 1 ,59437   ,380.1,384.9,389.7
XS GIS Cut Line= 4
     1908013.339      639493.049     1907983.814      639033.687
     1907947.367      638777.771     1907876.202      638438.092
#Sta/Elev= 30
       0  822.58    78.4   813.3   107.7  807.28   127.3  800.65   166.5  782.73
   195.9  771.46   205.7  768.07   215.5  766.33   264.4   770.9   313.4  768.76
   362.4   762.2   411.3  752.18   421.1  749.59   450.5  738.84   460.3  736.72
   584.8  726.49   603.1  723.59   623.1  718.81   632.6  719.57   642.2  723.34
   661.4  737.15   718.8  775.71   776.6  817.48   844.1  863.71   921.3  913.49
   959.8  934.42   988.7  954.32   998.4  959.94    1008  963.46  1065.9  972.54
#Mann= 3 , 0 , 0
       0     .06       0   603.1    .045       0   642.2      .1       0
Bank Sta=603.1,642.2
XS Rating Curve= 0 ,0
Exp/Cntr=0.3,0.1

Type RM Length L Ch R = 1 ,59052   ,393.3,407.6,421.6
XS GIS Cut Line= 4
     1908212.557      639424.965     1908332.349      638953.611
     1908348.344      638732.257     1908358.391      638326.006
#Sta/Elev= 30
       0   827.4    19.4  827.53    29.2  826.47   204.3  791.43     214  790.09
   272.4  789.19   282.1  787.96   311.3  779.34   330.7  771.24   359.9  754.86
   389.1  735.31   398.8  730.35   408.5  728.18   582.8  724.77   592.5  724.14
   604.2  721.81   621.4  718.67   631.1  719.14   640.7  721.48     660  727.72
     689  734.63   766.3  755.29     805  766.82   872.8  797.17   892.1  806.58
   921.1  822.33  1008.2   862.5  1017.9   865.5  1027.6  866.65  1114.6  870.61
#Mann= 3 , 0 , 0
       0     .05       0   604.2    .045       0   640.7      .1       0
Bank Sta=604.2,640.7
XS Rating Curve= 0 ,0
Exp/Cntr=0.3,0.1

Type RM Length L Ch R = 1 ,58644.5 ,383.6,397.5,411.6
XS GIS Cut Line= 4
     1908267.245      639448.402     1908639.789      639052.691
     1908806.307      638852.048     1909051.099      638539.548
#Sta/Elev= 30
       0  827.82     9.7  827.06    29.1     823   184.4  781.67   203.8  777.28
   271.7  767.66     330  757.91   436.7  748.86   446.4  746.33     495  728.61
   504.7  726.55   649.7  721.77   671.7  719.22   688.3   716.9     698  716.52
   707.7  717.19     727  720.66   746.3  725.64   775.3  736.71   813.9  752.81
   833.3  762.91     872  792.02   930.1  843.09   959.1  866.66   988.2  887.38
  1007.6  898.74  1036.6  912.13  1123.7  948.28  1152.8  959.06  1201.2   975.2
#Mann= 3 , 0 , 0
       0     .05       0   671.7    .045       0     727      .1       0
Bank Sta=671.7,727
XS Rating Curve= 0 ,0
Exp/Cntr=0.3,0.1

Type RM Length L Ch R = 1 ,58247   ,372.6,379.7,386.6
XS GIS Cut Line= 4
     1908306.307       639503.09     1908827.141      639281.736
      1909064.12      639219.236     1909433.912      639201.006
#Sta/Elev= 30
       0  829.07    19.5  826.76      39   820.9   126.8   787.5   156.1   777.8
   185.4  769.76   234.2  758.62     400  729.78   429.3   727.2     664   722.5
   673.8  721.96   686.4  719.44   703.2  715.77     713  715.74   722.8  718.46
   732.6  723.23   771.8  741.47   781.6  748.78   791.4  758.75     811  780.96
   820.8  790.12   840.2   804.8   869.5  822.92   898.7  838.78   937.7  856.67
  1015.6  904.24  1054.6  926.11  1074.1  935.08    1152  965.58  1181.2  975.96
#Mann= 3 , 0 , 0
       0     .05       0   686.4    .045       0   732.6      .1       0
Bank Sta=686.4,732.6
XS Rating Curve= 0 ,0
Exp/Cntr=0.3,0.1

Type RM Length L Ch R = 1 ,57867.3 ,421,420.8,420.7
XS GIS Cut Line= 4
     1908280.266      639685.381     1908803.703      639620.277
     1909058.912      639633.298     1909423.495      639646.319
#Sta/Elev= 30
       0  840.06    19.5  836.67    48.8  828.85    87.9  819.93   117.2   811.8
   136.8  805.26   185.6  785.85   214.9  775.34   263.7  759.83     293  751.46
   302.8  749.31   400.5  733.34     420  730.91   606.1  722.09   615.9  720.61
   635.6  714.87   645.4  714.38   674.9  718.71   684.7  721.32   694.6  726.22
   773.2  777.82   811.8  804.04   869.4  844.42     879  849.97   898.2  859.46
   917.4   867.5   946.2  876.98  1090.2  913.27    1119  922.21  1147.8  932.83
#Mann= 3 , 0 , 0
       0     .05       0   615.9    .045       0   684.7      .1       0
Bank Sta=615.9,684.7
XS Rating Curve= 0 ,0
Exp/Cntr=0.3,0.1

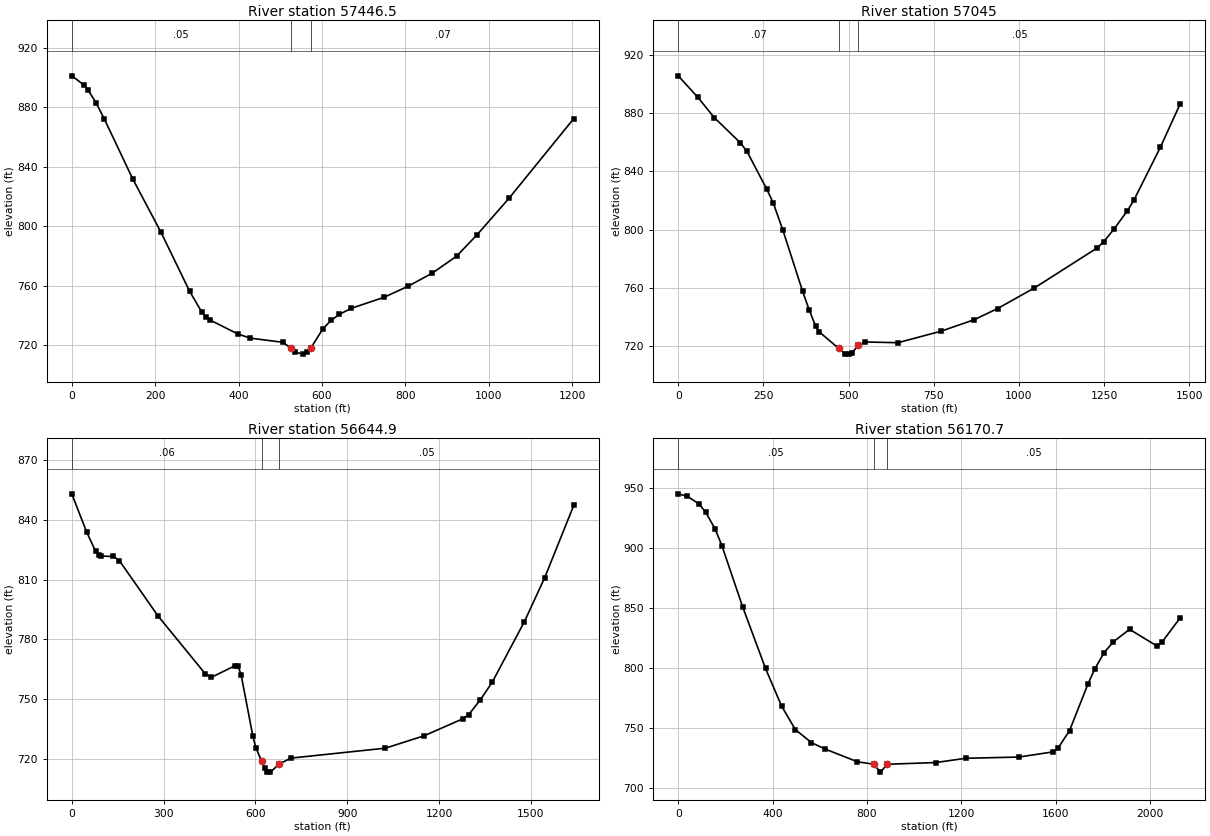
Type RM Length L Ch R = 1 ,57446.5 ,394.9,401.5,408.1
XS GIS Cut Line= 4
     1908334.953      640036.944     1908782.828      640040.259
     1908966.253      640048.359     1909537.644      640079.855
#Sta/Elev= 30
       0  901.14    29.2  894.99      39  891.64    58.4  882.92    77.9  872.22
     146  831.94   214.2  795.82   282.4  756.38   311.6  742.35   321.3  739.03
     331  737.04   399.2  727.46   428.4  724.78   505.9  722.01   525.2  718.13
   534.9  715.46   554.2  714.05   563.8  715.43   573.5  718.29   602.5  731.22
   621.8  736.73   641.2  740.72   670.3  744.85   747.9  752.17   806.1  759.64
   864.3  768.48   922.5  779.86     971  794.07  1048.6   818.9  1203.8  872.45
#Mann= 3 , 0 , 0
       0     .05       0   525.2    .045       0   573.5     .07       0
Bank Sta=525.2,573.5
XS Rating Curve= 0 ,0
Exp/Cntr=0.3,0.1

Type RM Length L Ch R = 1 ,57045   ,411.1,400.1,389.1
XS GIS Cut Line= 4
     1908295.891      640258.298     1908676.099      640393.715
     1908894.525      640470.161     1909733.391      640487.465
#Sta/Elev= 30
       0  905.97    57.7  891.12   105.7  877.21   182.6  859.74   201.8  853.83
   259.5  828.02   278.7   818.5   307.5  799.35   365.2  757.38   384.4  744.57
   403.6  733.23   413.2  729.54   471.1  718.03   490.4  714.36     500  714.06
   509.7  714.97     529  720.08   548.2  722.43   644.8  721.94   771.6  729.86
   869.2  737.81   937.5   745.5  1044.8  759.56  1230.2   787.3  1249.7   791.7
  1278.9   800.1    1318   812.7  1337.5   820.1  1415.5  856.66  1474.1  886.86
#Mann= 3 , 0 , 0
       0     .07       0   471.1    .045       0     529     .05       0
Bank Sta=471.1,529
XS Rating Curve= 0 ,0
Exp/Cntr=0.3,0.1

Type RM Length L Ch R = 1 ,56644.9 ,476,474.2,472.4
XS GIS Cut Line= 5
     1908110.995      640919.756     1908676.533      640829.855
     1908912.365      640793.321     1909459.256      640709.144
     1909732.586      640670.105
#Sta/Elev= 30
       0  853.04    48.5  833.91    77.6  824.24    87.4  822.47    97.1   821.8
   135.9  821.58   155.3  819.56   281.5  791.79   436.8  762.57   456.2  760.91
   533.8  766.78   543.5  766.38   553.2  762.31   591.7  731.46   601.3  725.65
   620.4  718.93   629.9  715.43   639.5  713.52     649  713.32   677.6  717.36
   715.8  720.35  1024.8  725.35    1151  731.54  1277.2  740.05  1296.7  742.14
  1335.5  749.68  1374.1   758.5  1478.9  788.79  1545.5  810.97  1640.7  847.36
#Mann= 3 , 0 , 0
       0     .06       0   620.4    .045       0   677.6     .05       0
Bank Sta=620.4,677.6
XS Rating Curve= 0 ,0
Exp/Cntr=0.3,0.1

Type RM Length L Ch R = 1 ,56170.7 ,258,256.1,254.4
XS GIS Cut Line= 4
     1907950.839      641399.299     1908676.533      641319.438
     1908923.061       641260.41     1910027.228      640961.799
#Sta/Elev= 30
       0  945.32    38.9   943.2    87.6  936.99   116.8   929.8   155.8  916.24
     185  902.14   272.6   851.3   369.9  799.74     438  768.38   496.4  748.76
   564.6  737.93     623  732.52   759.3  721.98   827.6  719.98   856.8  713.35
   886.1  719.92  1091.1  721.33  1218.2  724.89  1443.1  725.92  1589.7  730.27
  1609.3  733.35  1658.1  747.97  1736.4     787  1765.7  799.58  1804.8  813.06
  1843.9     822  1912.3  832.36  2029.6  818.36  2049.2  821.55  2127.4   842.1
#Mann= 3 , 0 , 0
       0     .05       0   827.6    .045       0   886.1     .05       0
Bank Sta=827.6,886.1
XS Rating Curve= 0 ,0
Exp/Cntr=0.3,0.1