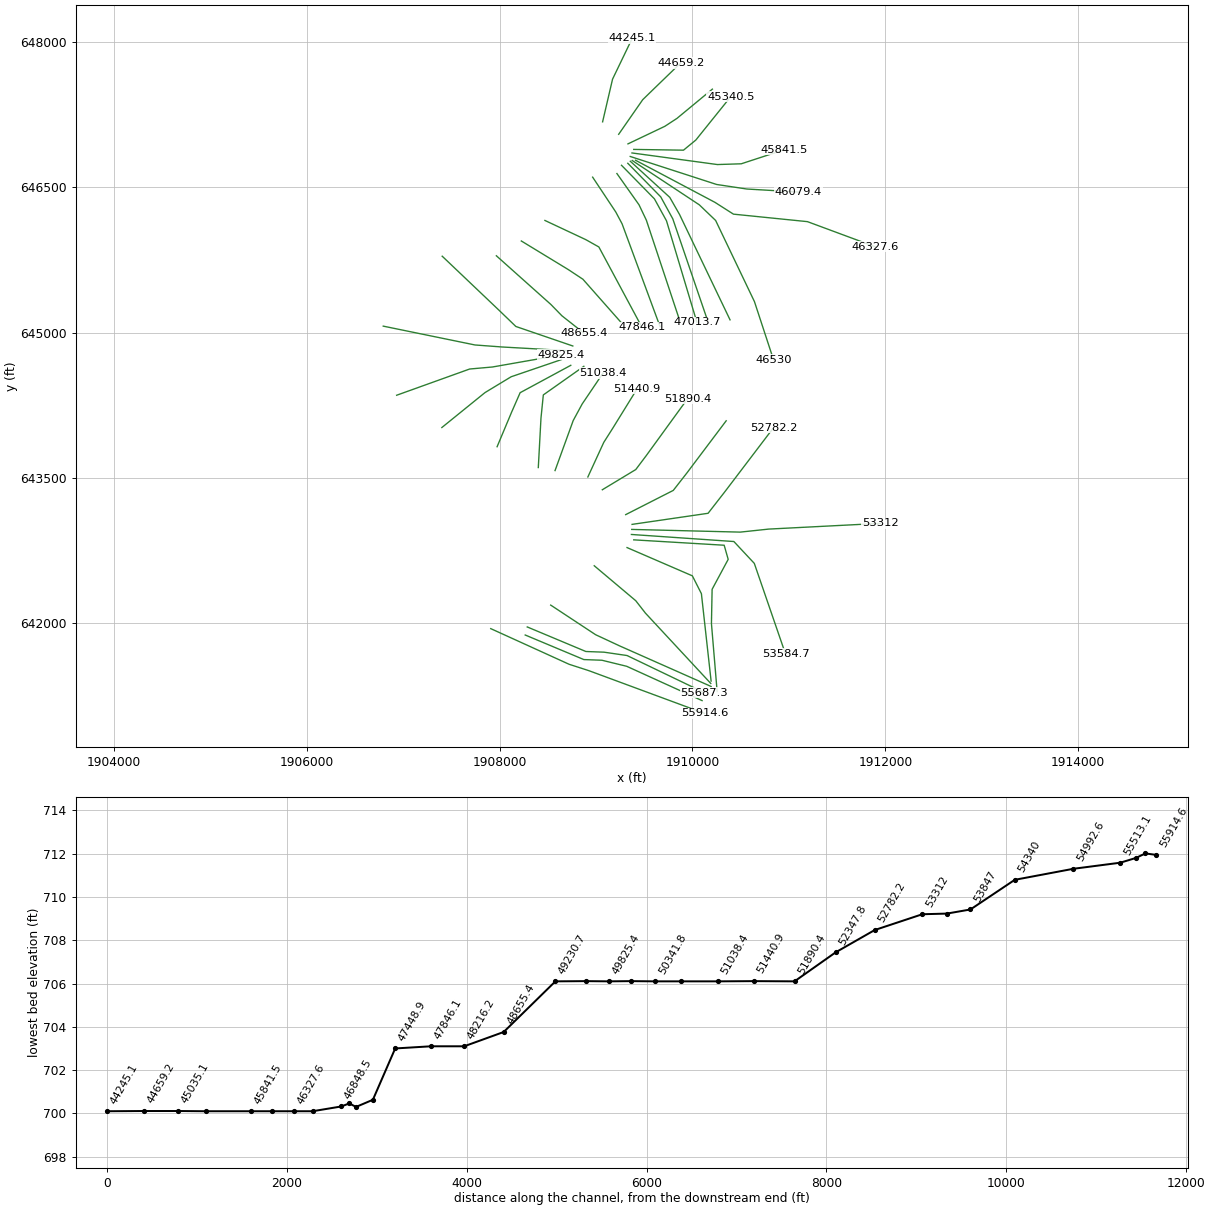
HEC-RAS study HenryFork.prj: HenryFork

--- HenryFork.g01 (geometry) --- (continued)

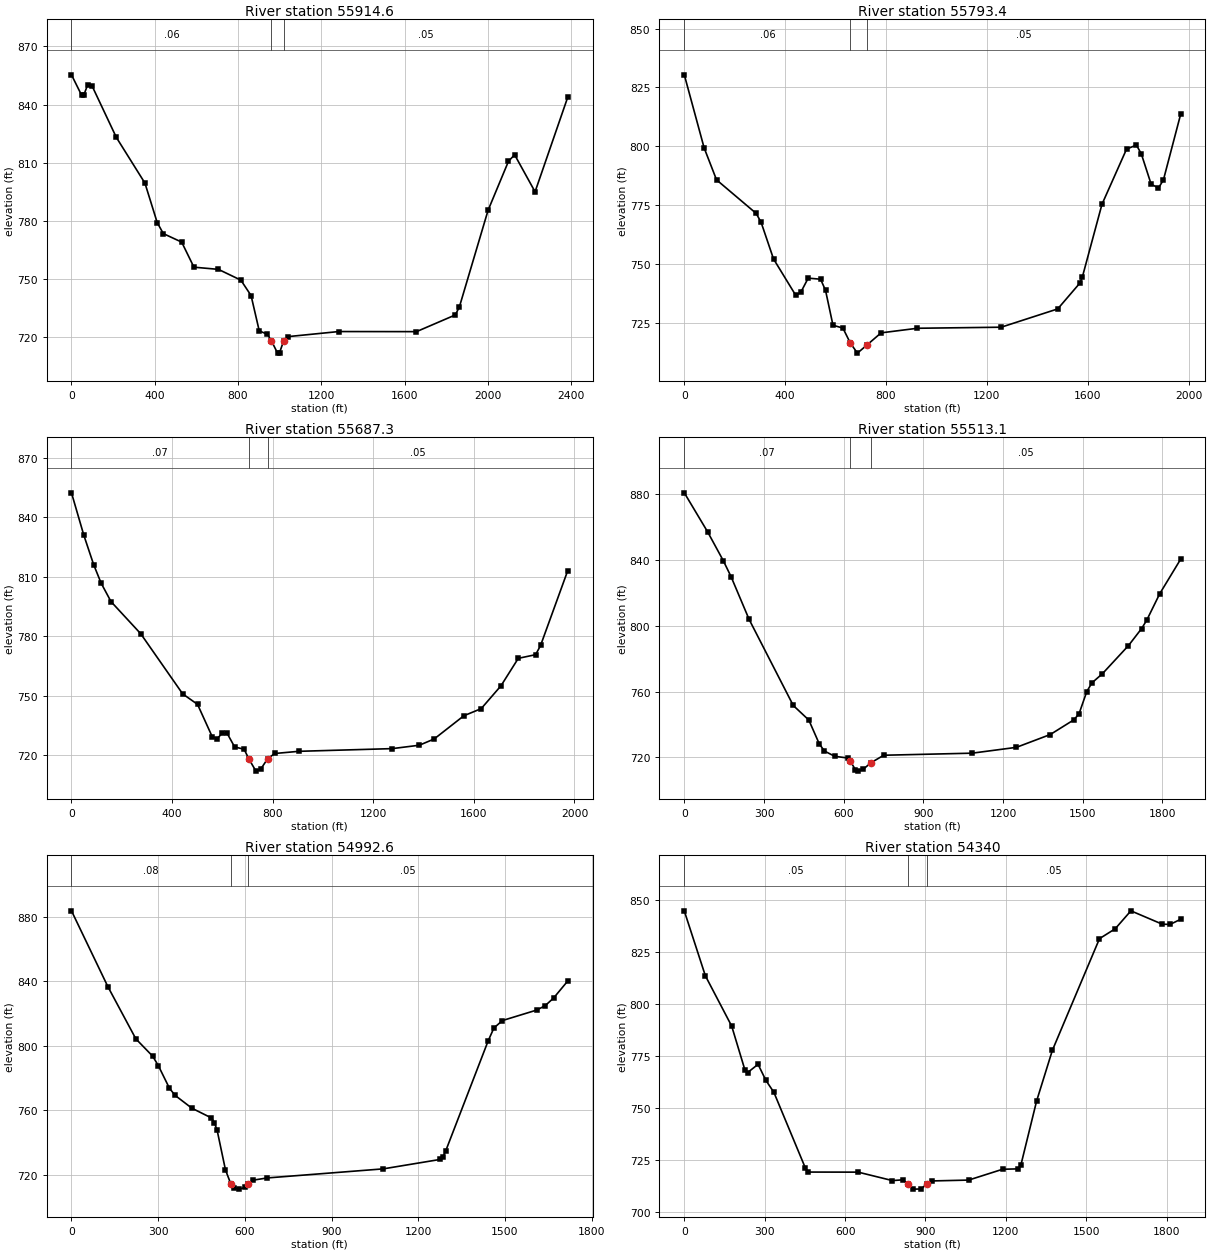
Type RM Length L Ch R = 1 ,55914.6 ,108,121.2,130.6
XS GIS Cut Line= 4
     1907909.172      641944.438     1908721.672      641576.383
     1908926.533       641510.41      1910124.45      641069.438
#Sta/Elev= 30
       0  855.33      49  844.74    58.8  844.82    78.4  850.34      98  849.81
   215.6  823.06   352.9  799.52   411.7  779.22   441.1  773.52   529.3  769.14
   588.1  756.22   705.7   755.1   813.6  749.54   862.6   741.6   901.8  723.41
   940.9  721.66   960.5  718.24   989.8  711.94   999.6  712.22  1019.2  718.31
  1038.7  720.43  1283.9  723.06  1657.1  723.01  1843.6  731.62  1863.3  735.83
  2000.8  785.51  2098.9  810.79  2128.4  814.14  2226.6  795.06  2383.7  843.86
#Mann= 3 , 0 , 0
       0     .06       0   960.5    .045       0  1019.2     .05       0
Bank Sta=960.5,1019.2
XS Rating Curve= 0 ,0
Exp/Cntr=0.3,0.1

Type RM Length L Ch R = 1 ,55793.4 ,111.2,106.1,104.6
XS GIS Cut Line= 5
     1908266.811      641878.466      1908874.45      641624.994
      1909061.95      641618.049     1909318.894      641555.549
     1910100.144      641201.383
#Sta/Elev= 30
       0  830.32    78.6  799.27   127.8  785.68     285  771.41   304.6  767.61
   353.8  752.05   442.2  736.54   461.8  737.84   491.3  743.89   540.5  743.43
   560.1  738.68   589.6  723.86   628.9  722.67   658.4   716.3   686.5  712.01
   724.1  715.44   780.4  720.63   924.4  722.58  1256.7  723.03  1480.9  730.81
  1568.6  741.77  1578.3  744.25  1656.3  775.26  1753.8  798.73  1792.8  800.47
  1812.3  796.76  1851.3  783.84  1880.5   782.2    1900  785.63  1968.2  813.48
#Mann= 3 , 0 , 0
       0     .06       0   658.4    .045       0   724.1     .05       0
Bank Sta=658.4,724.1
XS Rating Curve= 0 ,0
Exp/Cntr=0.3,0.1

Type RM Length L Ch R = 1 ,55687.3 ,184,174.2,164.9
XS GIS Cut Line= 5
     1908287.644      641961.799     1908895.283      641708.327
     1909082.783      641701.383     1909322.367       641666.66
     1910120.978      641284.716
#Sta/Elev= 30
       0  852.42    49.1  830.99    88.4  816.05   117.9  806.78   157.2  797.45
   275.2  781.24   442.2  750.82   501.2  745.54   560.1  729.06   579.8  728.26
   599.4  730.97   619.1  730.85   648.6  724.05   686.5  722.84   705.3  717.97
   733.4   711.8   752.2  712.77   780.4  718.14   808.5  720.71   904.1  721.81
    1275  723.17  1383.2  724.89  1442.2  728.05  1560.2  739.78  1629.1  743.37
  1707.8  754.92  1776.6  768.79  1845.5  770.64  1865.2  775.28  1973.4  813.16
#Mann= 3 , 0 , 0
       0     .07       0   705.3    .045       0   780.4     .05       0
Bank Sta=705.3,780.4
XS Rating Curve= 0 ,0
Exp/Cntr=0.3,0.1

Type RM Length L Ch R = 1 ,55513.1 ,532.2,520.5,508.3
XS GIS Cut Line= 4
       1908530.7      642187.494     1908995.978      641881.938
     1909242.572      641767.415     1910193.894      641347.216
#Sta/Elev= 30
       0  880.84    87.9  857.08   146.5  839.66   175.8  829.94   244.1  803.82
   410.2  751.51   468.8  742.64   507.8  728.29   527.3  723.82   566.4  720.59
   614.9  719.57   624.6  717.71     644  712.52   653.7  711.58   673.2  712.67
   702.3  716.63   750.8  721.24  1083.6   722.5  1250.4  726.05    1378  733.85
  1466.3  742.75  1485.9  746.36  1515.3     760  1534.9   765.3  1574.2  770.83
  1672.3  787.94  1721.4  798.23    1741  803.37    1790   819.5  1868.5  840.42
#Mann= 3 , 0 , 0
       0     .07       0   624.6    .045       0   702.3     .05       0
Bank Sta=624.6,702.3
XS Rating Curve= 0 ,0
Exp/Cntr=0.3,0.1

Type RM Length L Ch R = 1 ,54992.6 ,656.6,652.6,648.1
XS GIS Cut Line= 4
     1908982.089      642593.744     1909412.644      642232.633
     1909513.339       642104.16     1910190.422      641378.466
#Sta/Elev= 30
       0  883.56     126  836.61   222.8  804.31     281  793.59   300.4   787.8
   339.1  773.74   358.5  769.35   416.6   761.4   484.4  755.36   494.1  752.52
   503.8  747.98   532.9  723.26   552.2  714.17   561.9  711.95   581.1   711.3
   600.4  712.37     610   714.6   629.2  716.87   677.2  718.22  1078.9  723.84
  1275.5  729.66  1285.3  731.16  1295.1   734.9  1442.5  803.23  1462.2  811.09
  1491.7  815.65  1609.6  822.11  1639.1  824.78  1668.6  829.59  1717.7  840.14
#Mann= 3 , 0 , 0
       0     .08       0   552.2    .045       0     610     .05       0
Bank Sta=552.2,610
XS Rating Curve= 0 ,0
Exp/Cntr=0.3,0.1

Type RM Length L Ch R = 1 ,54340   ,497.4,493,488.6
XS GIS Cut Line= 4
     1909322.367      642781.244      1909999.45      642489.577
       1910093.2      642305.549     1910193.894      641402.771
#Sta/Elev= 30
       0  844.93    78.6  813.68   176.9   789.4   226.1  768.31   235.9  766.96
   275.2  770.99   304.7  763.18   334.2   757.5   452.2  720.84     462  719.02
   648.8  718.98   776.6  714.91   815.9  715.28   835.6  713.08   855.2  710.79
   884.8  710.86   904.4  713.41   924.1  714.74    1061  715.15    1188  720.38
  1246.6  720.56  1256.3  722.54  1314.9  753.36  1373.5  777.71  1549.4  831.59
    1608  836.35  1666.6  845.01  1783.8  838.56  1813.1  838.46  1852.1  840.93
#Mann= 3 , 0 , 0
       0     .05       0   835.6    .045       0   904.4     .05       0
Bank Sta=835.6,904.4
XS Rating Curve= 0 ,0
Exp/Cntr=0.3,0.1

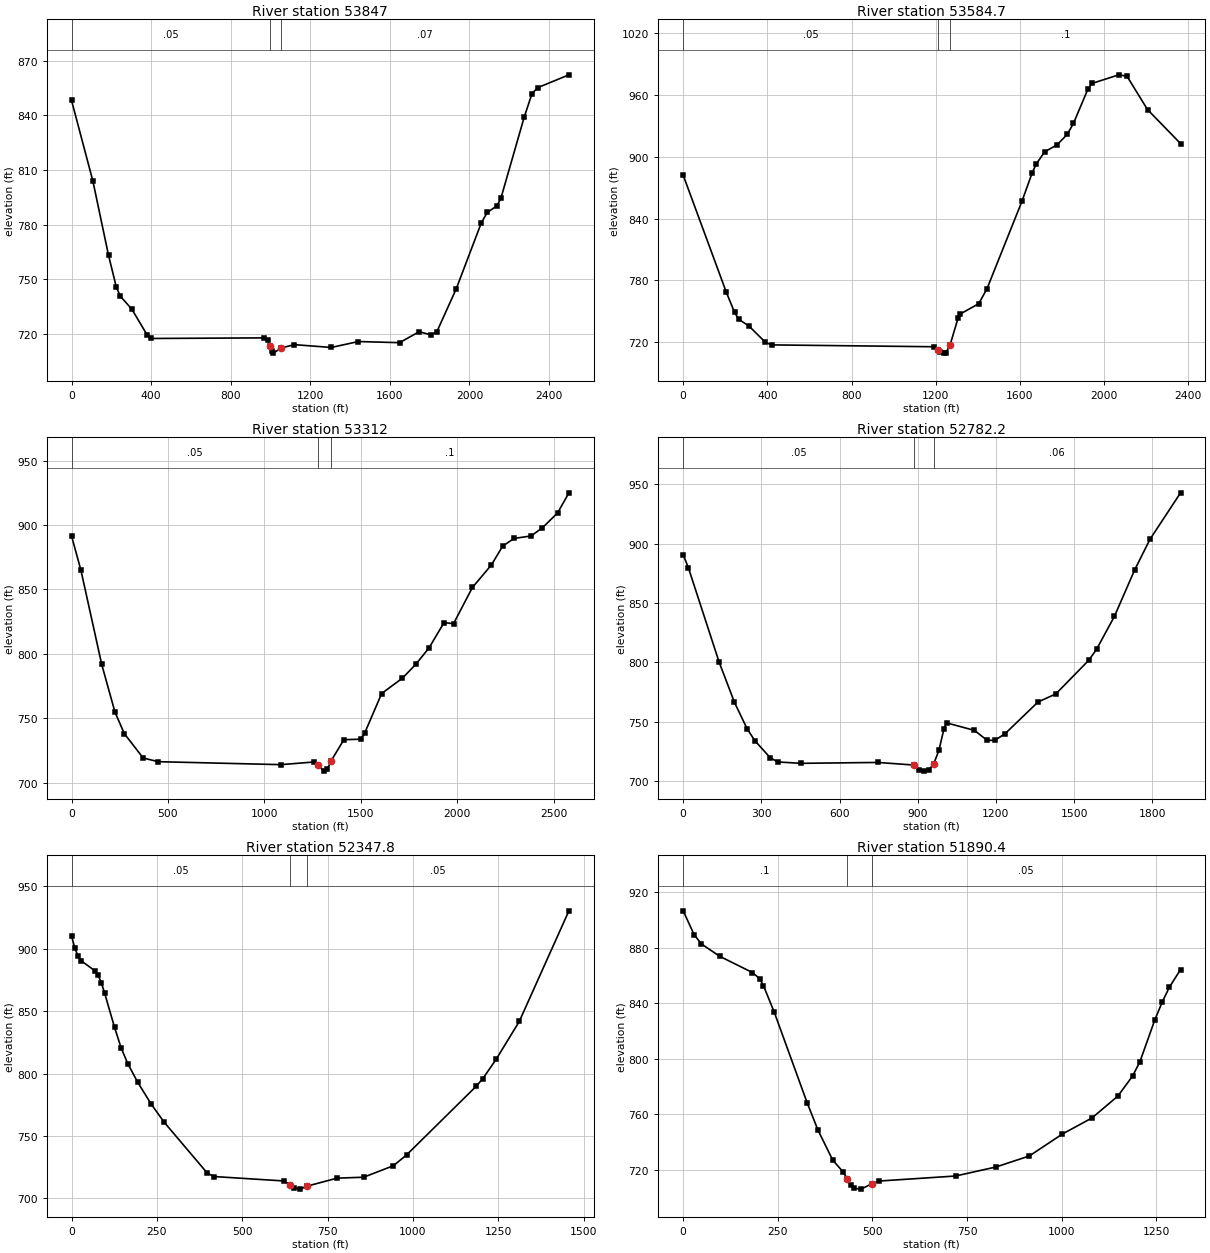
Type RM Length L Ch R = 1 ,53847   ,255,262.3,274.6
XS GIS Cut Line= 6
     1909391.811      642861.105     1910329.311      642805.549
     1910370.978      642659.716     1910204.311      642350.688
     1910197.367      641996.521     1910256.394      641295.133
#Sta/Elev= 30
       0  848.25   107.6  803.82   185.9  763.16     225  745.77   244.6  740.79
   303.3  733.52   381.5  719.14   401.1  717.47   967.6   717.8   986.5  716.59
     996   713.6  1005.5  710.34    1015  709.42  1052.9  712.22  1120.1  714.08
  1305.4  712.53  1441.9  715.79  1648.6  715.16    1747  721.16  1805.9  719.48
  1835.3  720.97    1933  744.57  2060.1  781.11  2089.4   786.7  2138.3  790.35
  2157.9  794.42  2275.2  839.04  2314.3  851.98  2343.6  855.29    2500  862.32
#Mann= 3 , 0 , 0
       0     .05       0     996    .045       0  1052.9     .07       0
Bank Sta=996,1052.9
XS Rating Curve= 0 ,0
Exp/Cntr=0.3,0.1

Type RM Length L Ch R = 1 ,53584.7 ,251.5,272.8,294
XS GIS Cut Line= 4
     1909367.505       642916.66     1910430.005      642843.744
     1910641.811      642618.049     1910964.728      641684.021
#Sta/Elev= 30
       0  882.28   205.2  768.29   244.3  748.76   263.8  742.14   312.7  735.55
   390.8   719.7   420.1  717.24  1190.7  715.43  1210.1  712.73  1219.8  710.11
  1239.1  709.23  1248.8  709.68  1268.1  717.35  1306.8  743.85  1316.5  747.28
  1403.9  757.27    1443  771.66  1609.4  856.85  1658.3  884.69  1677.8   893.2
    1717  904.88  1775.7  911.64  1824.6  921.88    1854  932.51  1922.5  965.82
    1942  971.39  2069.2  979.78  2108.4  978.42  2206.2   945.9  2362.8  912.98
#Mann= 3 , 0 , 0
       0     .05       0  1210.1    .045       0  1268.1      .1       0
Bank Sta=1210.1,1268.1
XS Rating Curve= 0 ,0
Exp/Cntr=0.3,0.1

Type RM Length L Ch R = 1 ,53312   ,511.6,529.8,548.1
XS GIS Cut Line= 4
     1909370.978      642968.744     1910495.978      642940.966
     1910791.117      642972.216     1911947.367      643031.244
#Sta/Elev= 30
       0  891.53    48.9   864.8   156.6  791.89   225.1  755.04     274  738.21
   371.8  719.36   450.1  716.52  1086.2  714.22  1259.4  716.31  1278.5  714.21
  1307.2   709.2  1326.4  710.47  1345.5  716.92  1412.6  733.57  1500.6  733.95
  1520.2  738.58  1608.6  769.37  1716.5   781.3  1785.2  791.92  1853.8  804.61
  1932.3  824.36  1981.4   823.5  2079.5  851.61  2177.6  868.99  2236.5  883.66
  2295.4  889.59  2383.7  891.51  2442.5  897.88    2521   909.3  2579.9  924.94
#Mann= 3 , 0 , 0
       0     .05       0  1278.5    .045       0  1345.5      .1       0
Bank Sta=1278.5,1345.5
XS Rating Curve= 0 ,0
Exp/Cntr=0.3,0.1

Type RM Length L Ch R = 1 ,52782.2 ,434.4,434.4,434.3
XS GIS Cut Line= 4
      1909374.45      643020.827     1910162.644       643135.41
     1910336.255      643357.633     1910839.728      644017.355
#Sta/Elev= 30
       0  890.56    19.7  879.81   137.7  800.38   196.7   766.4   245.8  743.91
   275.3  734.03   334.3  719.67   363.8  716.17   452.3  715.03   747.3  715.78
     884   713.6   903.4  709.08   922.9  708.47   942.3  709.34   961.8  714.87
   981.2  725.91  1000.7  744.13  1010.4   749.1  1117.5  742.75  1166.4  734.37
  1195.6  734.42  1234.7  739.87  1361.6  766.65    1430  773.46  1556.9  801.91
  1586.2  811.01  1654.5  838.62  1732.6   877.9  1791.2  903.57  1908.4  942.65
#Mann= 3 , 0 , 0
       0     .05       0     884    .045       0   961.8     .06       0
Bank Sta=884,961.8
XS Rating Curve= 0 ,0
Exp/Cntr=0.3,0.1

Type RM Length L Ch R = 1 ,52347.8 ,456.8,457.3,457.7
XS GIS Cut Line= 4
     1909308.478      643121.521     1909801.533      643371.521
     1909940.422      643548.605     1910350.144      644090.271
#Sta/Elev= 30
       0  910.24     9.7  900.41    19.4  893.92    29.1  890.18    67.9  882.45
    77.6  879.03    87.3  872.74      97  864.38   126.1  836.96   145.5  820.37
   164.9  807.87     194  792.98   232.8  775.78   271.6  760.95   397.6   720.3
     417  717.53   621.3     714   640.9  710.85   650.7  708.46   670.2  707.44
   689.8  709.82   777.9  716.24   855.5  716.97   942.8  726.18   981.6  734.87
  1185.4  789.83  1204.8  795.99  1243.6  811.31  1311.5  841.72    1457  930.37
#Mann= 3 , 0 , 0
       0     .05       0   640.9    .045       0   689.8     .05       0
Bank Sta=640.9,689.8
XS Rating Curve= 0 ,0
Exp/Cntr=0.3,0.1

Type RM Length L Ch R = 1 ,51890.4 ,447.7,449.5,451.3
XS GIS Cut Line= 4
     1909066.019      643378.375     1909412.644      643586.799
     1909520.283       643729.16     1909950.839      644319.438
#Sta/Elev= 30
       0  906.47    28.9  889.34    48.2  882.62    96.3  873.76     183  862.03
   202.2  857.61   211.9  852.69   240.8  833.32   327.4  768.29   356.3  748.44
   394.8  727.09   423.2  718.23   432.6  713.74     442  708.99   451.4  706.64
   470.2   706.1   498.4  710.03   517.2  711.92   719.3  715.54   826.5  722.07
   914.2  729.97  1001.8  745.81  1079.8  757.37    1148  773.08  1186.9   787.5
  1206.4  797.93  1245.4  827.77  1264.8  840.56  1284.3   851.6  1313.6  864.16
#Mann= 3 , 0 , 0
       0      .1       0   432.6    .045       0   498.4     .05       0
Bank Sta=432.6,498.4
XS Rating Curve= 0 ,0
Exp/Cntr=0.3,0.1

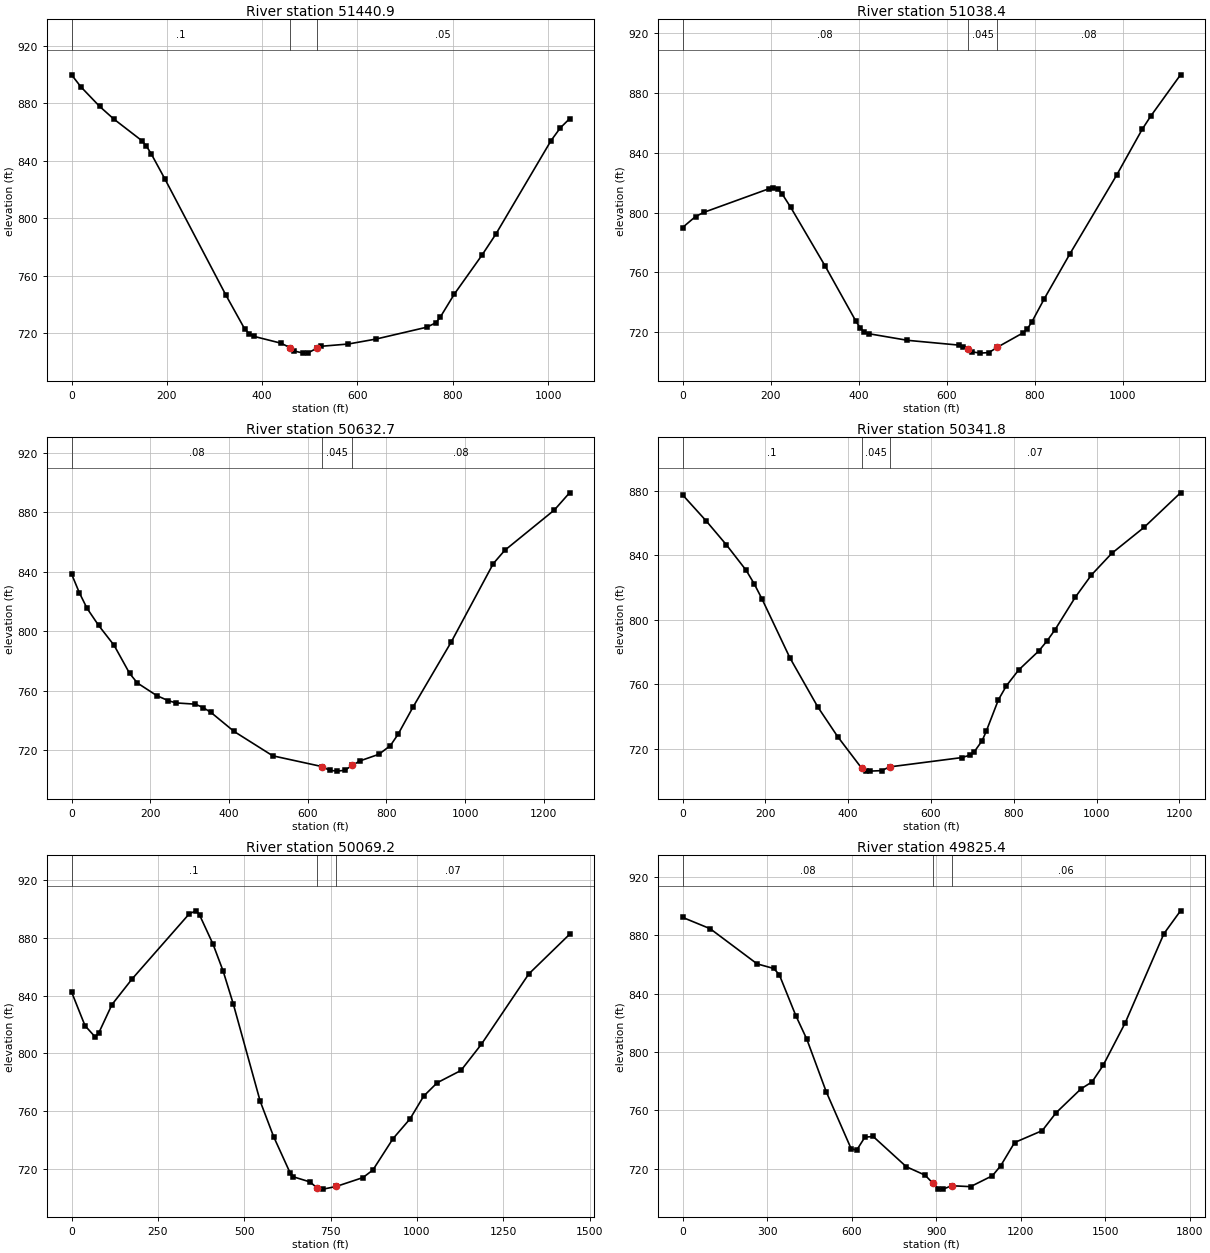
Type RM Length L Ch R = 1 ,51440.9 ,400.9,402.5,404
XS GIS Cut Line= 4
     1908916.117       643510.41     1909080.785      643867.014
     1909176.533      644017.355     1909426.533      644420.133
#Sta/Elev= 30
       0   899.9    19.6  891.52    58.9  877.91    88.4  869.18   147.3   854.1
   157.1  850.26   166.9  845.06   196.4  827.06     324  746.44   363.3  722.96
   373.2  719.52     383  717.76   439.7  713.01   458.5  709.91   467.8  707.54
   486.6  706.11     496  706.21   514.7  709.55   524.1  710.89   580.7  712.45
   638.8   715.9   745.2  724.14   764.5  727.22   774.2  731.39   803.2  747.18
   861.3  774.34   890.3  788.91  1006.4  854.16  1025.7  862.95  1045.1   869.3
#Mann= 3 , 0 , 0
       0      .1       0   458.5    .045       0   514.7     .05       0
Bank Sta=458.5,514.7
XS Rating Curve= 0 ,0
Exp/Cntr=0.3,0.1

Type RM Length L Ch R = 1 ,51038.4 ,396.5,405.7,414.4
XS GIS Cut Line= 4
     1908575.839      643576.383      1908764.27      644093.172
     1908857.089      644263.883     1909073.978      644583.684
#Sta/Elev= 30
       0  790.03    29.5  797.38    49.1  800.26   196.4  815.98   206.3  816.65
   216.1  815.66   225.9  812.63   245.6  803.56   324.2  764.12   392.9  727.86
   402.7   723.2   412.6  720.24   422.4   719.1   510.8  714.66   627.8  711.45
   637.5  710.44   647.2  708.58   656.9  706.96   676.4   706.1   695.8  706.49
   715.2  710.09   773.4  719.68     783  722.38   792.7  726.66   821.7  742.58
   879.6  772.43   985.9  825.12  1043.8   855.7  1063.2   864.5  1130.8  892.09
#Mann= 3 , 0 , 0
       0     .08       0   647.2    .045       0   715.2     .08       0
Bank Sta=647.2,715.2
XS Rating Curve= 0 ,0
Exp/Cntr=0.3,0.1

Type RM Length L Ch R = 1 ,50632.7 ,298,290.9,283.6
XS GIS Cut Line= 4
     1908402.228      643607.633     1908430.005      644118.049
     1908454.311      644357.633      1908874.45      644652.771
#Sta/Elev= 30
       0  838.45    19.7  825.91    39.3  815.42    68.8  803.91   108.1  790.57
   147.4  771.76   167.1   765.3   216.3  756.83   245.8   753.4   265.4   751.9
   314.6  751.05   334.2  748.76   353.9  745.58   412.9  732.75   511.2  716.38
   636.4  709.16   655.7  706.64   674.9   706.1   694.2  706.66   713.4  709.99
   732.7  712.96     781  717.41   810.1  723.22   829.5  730.77   868.2  749.37
   965.1  792.98  1071.7  845.46  1100.7  854.33  1226.7   881.4  1265.4  892.95
#Mann= 3 , 0 , 0
       0     .08       0   636.4    .045       0   713.4     .08       0
Bank Sta=636.4,713.4
XS Rating Curve= 0 ,0
Exp/Cntr=0.3,0.1

Type RM Length L Ch R = 1 ,50341.8 ,286.6,272.6,258.7
XS GIS Cut Line= 4
     1907975.144       643822.91      1908124.45      644177.077
     1908213.848      644380.355     1908739.033      644663.188
#Sta/Elev= 30
       0  877.36    57.6  861.03   105.7  846.43   153.7  830.56     173  822.25
   192.2  812.69   259.4  776.29   326.7  745.89   374.7  727.49   432.6  707.96
   442.3  706.34   451.9   706.1   480.9  706.41   500.2  708.72   674.9   714.5
   694.4  716.03   704.2  717.93   723.8  724.99   733.5  730.73   762.9  750.26
   782.4  759.04   811.8  768.74   860.7  780.62   880.2   786.7   899.8  793.75
   948.7  813.88   987.8   827.7  1036.7  841.05  1114.9  857.18  1202.9  878.58
#Mann= 3 , 0 , 0
       0      .1       0   432.6    .045       0   500.2     .07       0
Bank Sta=432.6,500.2
XS Rating Curve= 0 ,0
Exp/Cntr=0.3,0.1

Type RM Length L Ch R = 1 ,50069.2 ,254.5,243.8,233.1
XS GIS Cut Line= 4
     1907402.228      644020.827     1907850.144      644381.938
     1908120.978      644545.133     1908641.811      644722.216
#Sta/Elev= 30
       0   842.5      39  819.15    68.3  811.42      78  813.78     117  833.81
   175.5  851.59   341.3  896.73   360.8  898.65   370.6  895.77   409.6  875.55
   438.8  856.98   468.1  834.29   546.1   766.9   584.9  742.47   632.8  717.31
   642.4   714.6   690.3  711.09   709.5  707.17   728.7  706.11     767  708.01
   843.6   714.1   872.4  719.35   930.8  741.09     980  754.75  1019.3  770.43
  1058.6  779.72  1127.3   788.2  1186.3  806.28  1323.8  855.01  1441.7  882.38
#Mann= 3 , 0 , 0
       0      .1       0   709.5    .045       0     767     .07       0
Bank Sta=709.5,767
XS Rating Curve= 0 ,0
Exp/Cntr=0.3,0.1

Type RM Length L Ch R = 1 ,49825.4 ,263.1,259.7,256.2
XS GIS Cut Line= 4
     1906933.478       644354.16     1907690.422      644624.994
     1907926.533      644645.827     1908641.811      644770.827
#Sta/Elev= 30
       0  892.36      98  884.59   264.7  860.48   323.5  857.33   343.1  853.19
     402  825.02   441.2  808.78   509.8  772.91     598  733.92   617.7  732.73
   647.1  741.71   676.5  742.18   794.1  721.46   860.8  715.66   889.3  709.96
   908.2  706.35   924.6   706.1   955.6  708.43    1022   707.8  1099.8   715.3
  1129.3   722.2  1178.3  738.02  1276.5   746.2  1325.5  758.43  1413.8  774.81
  1453.1  779.58  1492.3  790.84  1570.8  820.04  1708.2  881.18  1767.1  896.84
#Mann= 3 , 0 , 0
       0     .08       0   889.3    .045       0   955.6     .06       0
Bank Sta=889.3,955.6
XS Rating Curve= 0 ,0
Exp/Cntr=0.3,0.1

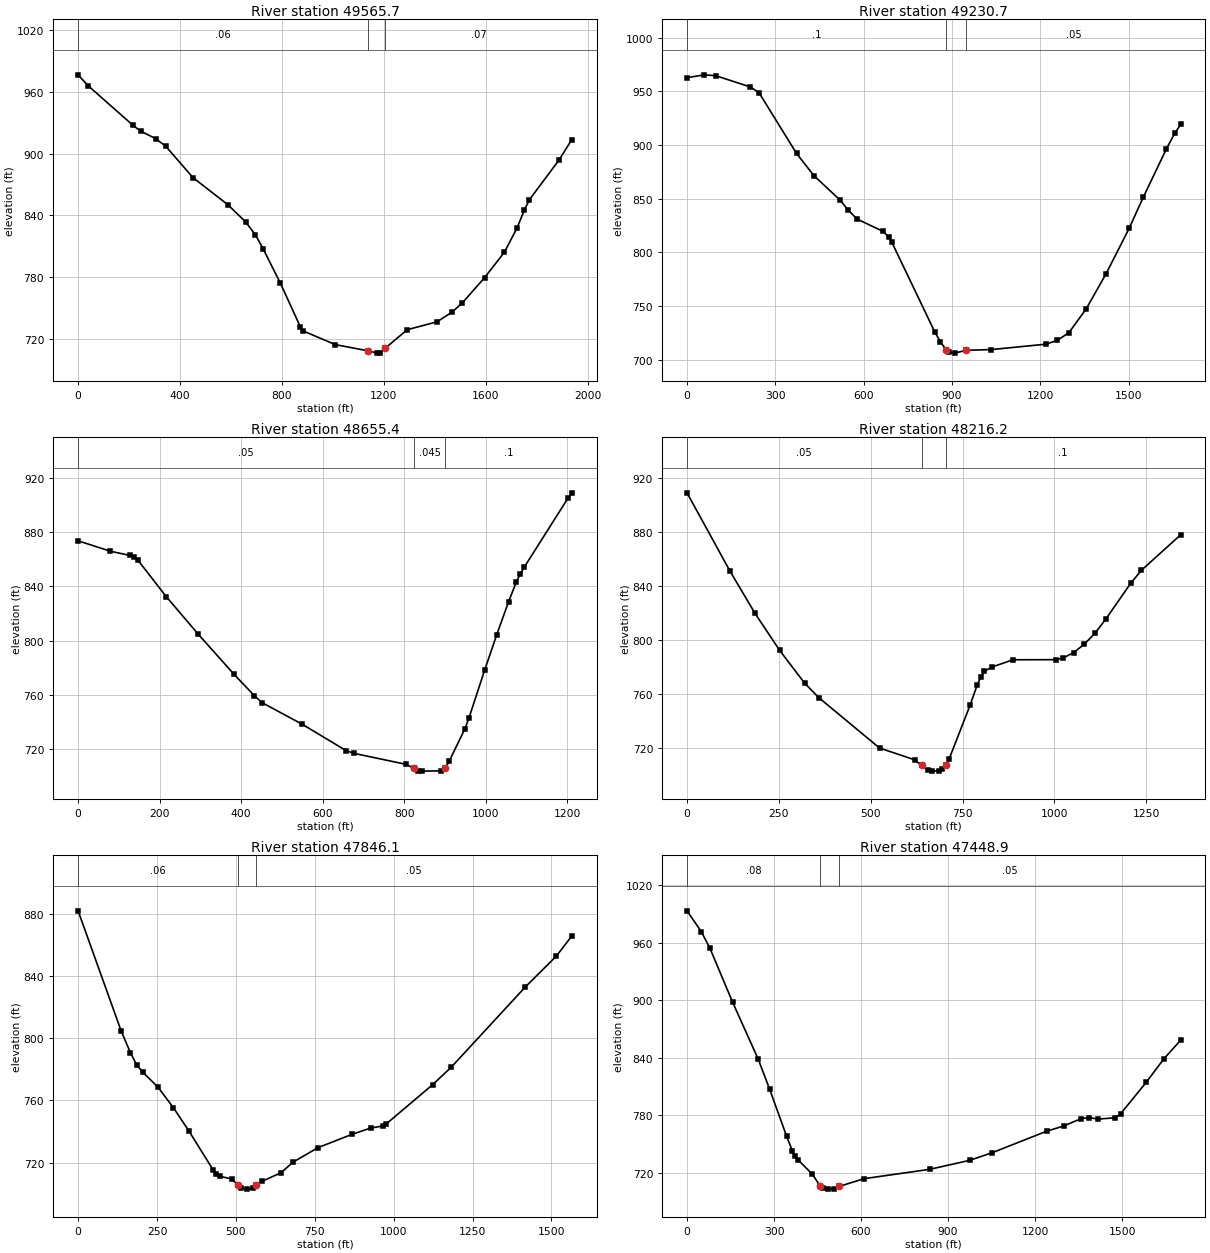
Type RM Length L Ch R = 1 ,49565.7 ,350.7,335,319
XS GIS Cut Line= 4
     1906794.589      645067.702     1907745.978      644873.258
     1908027.228      644852.424     1908711.255       644814.23
#Sta/Elev= 30
       0   976.8    39.2  966.23   215.8  927.62   245.2   922.1   304.1  914.75
   343.3  907.53   451.2  876.78   588.5  850.35   657.2  833.87   696.4  821.02
   725.8  807.86   794.5  773.96     873  731.34   882.8  727.76    1010  714.37
  1136.4  708.43  1175.3  706.11    1185  706.46  1204.4  710.64  1292.2  728.91
  1409.7  736.61  1468.4  746.11  1507.5  754.71  1595.6  779.48  1673.9   804.4
  1722.8  827.71  1752.2  845.49  1771.8  855.36  1889.2  894.37  1938.2  913.82
#Mann= 3 , 0 , 0
       0     .06       0  1136.4    .045       0  1204.4     .07       0
Bank Sta=1136.4,1204.4
XS Rating Curve= 0 ,0
Exp/Cntr=0.3,0.1

Type RM Length L Ch R = 1 ,49230.7 ,575.5,575.3,574.8
XS GIS Cut Line= 4
       1907405.7      645789.924     1907995.978      645230.896
     1908169.589       645064.23     1908759.867      644862.841
#Sta/Elev= 30
       0  962.83    58.8  965.51      98  964.67   215.5  954.18   244.9  948.73
   372.2  892.21     431  871.59   519.1  848.99   548.5  839.14   577.9  831.08
   666.1  819.54   685.6  814.04   695.4  809.71   841.9  725.72   861.1   716.5
   880.4  709.36     890  707.18   909.2   706.1   947.8  708.71  1034.4  709.43
  1219.3  714.43  1258.3  718.06  1297.3  725.13  1355.7  747.16    1424  780.24
  1501.9  822.32  1550.6  851.73  1628.6  896.47  1657.8  911.48  1677.3  919.25
#Mann= 3 , 0 , 0
       0      .1       0   880.4    .045       0   947.8     .05       0
Bank Sta=880.4,947.8
XS Rating Curve= 0 ,0
Exp/Cntr=0.3,0.1

Type RM Length L Ch R = 1 ,48655.4 ,433.8,439.2,443.7
XS GIS Cut Line= 4
     1907967.332      645794.265     1908532.436       645291.66
     1908647.019      645174.473     1908876.186      644994.785
#Sta/Elev= 30
       0  873.62    78.6  865.97   127.7  862.81   137.5  861.51   147.3  859.12
   216.1  832.52   294.6   804.8     383  775.03   432.2  759.46   451.8  754.21
     550   738.3   658.1  718.81   677.7  716.82   804.5  708.77   823.8  705.77
   833.4   704.2     843  703.76   891.2  703.99   900.9  706.12   910.5  711.04
   949.3  735.11     959  742.97   997.8  778.48    1027   804.2  1056.1   828.6
  1075.5  843.46  1085.2  849.38  1094.9  854.25  1201.7  904.97  1211.4     909
#Mann= 3 , 0 , 0
       0     .05       0   823.8    .045       0   900.9      .1       0
Bank Sta=823.8,900.9
XS Rating Curve= 0 ,0
Exp/Cntr=0.3,0.1

Type RM Length L Ch R = 1 ,48216.2 ,398.7,370.2,406.3
XS GIS Cut Line= 4
     1908226.012      645947.042     1908715.596      645650.167
     1908864.881      645551.793      1909258.13      645108.501
#Sta/Elev= 30
       0  909.27   116.4  851.56   184.4  820.28   252.3   792.5   320.2  768.25
   359.1  757.45     524  720.23   619.6  711.48   638.4  707.31   655.5  703.67
   666.7   703.1   685.5  703.36   694.9  704.67   704.3  707.52   713.7  712.24
   770.8  752.12   790.2  767.16   799.9  772.97   809.6  777.07   829.1  780.12
   887.4   785.6  1003.9  785.66  1023.4   786.8  1052.5  790.97  1081.6  797.16
  1110.8  805.34  1139.9   815.7  1207.9  842.34  1237.1  851.94  1343.9  878.22
#Mann= 3 , 0 , 0
       0     .05       0   638.4    .045       0   704.3      .1       0
Bank Sta=638.4,704.3
XS Rating Curve= 0 ,0
Exp/Cntr=0.3,0.1

Type RM Length L Ch R = 1 ,47846.1 ,410,397.2,384.4
XS GIS Cut Line= 4
     1908470.804      646158.848     1908894.415      645960.931
     1909030.117       645885.04      1909476.88      645056.417
#Sta/Elev= 30
       0  881.74   136.4  804.64   165.6  790.77   185.1  782.99   204.6  778.24
   253.3   768.5     302  755.35   350.7  740.56   428.6   715.2   438.3  712.68
   448.1  711.33     487  709.68   506.4  705.68   516.2  703.86   535.6   703.1
     555   703.8   564.7  705.68   584.2  708.24   642.7  713.61   681.9  720.53
   760.3  729.75   868.2  738.29     927  742.31   966.3  743.63   976.1   744.9
  1123.2  770.13    1182  781.28  1417.3  832.91  1515.4  852.68  1564.4  865.61
#Mann= 3 , 0 , 0
       0     .06       0   506.4    .045       0   564.7     .05       0
Bank Sta=506.4,564.7
XS Rating Curve= 0 ,0
Exp/Cntr=0.3,0.1

Type RM Length L Ch R = 1 ,47448.9 ,249.1,248,247
XS GIS Cut Line= 4
     1908965.596      646605.896     1909205.179      646246.521
     1909270.786      646124.364      1909664.38      645063.362
#Sta/Elev= 30
       0  993.35    49.1  971.72    78.5  954.68   157.1  898.08   245.4  838.63
   284.7  807.41   343.6  758.01   363.2  742.95     373  737.24   382.8  733.53
   431.9  718.66   459.6  706.06   468.9  703.71   486.8     703   505.9  703.47
   524.4  705.81   609.9  713.88   836.3  723.63     974  732.98  1052.8  741.07
  1239.7   763.4  1298.8  768.88  1357.8  776.43  1387.3   777.7  1416.9  776.03
  1475.9  777.46  1495.6  781.86  1584.1  814.76  1643.2  838.64  1702.2   858.5
#Mann= 3 , 0 , 0
       0     .08       0   459.6    .045       0   524.4     .05       0
Bank Sta=459.6,524.4
XS Rating Curve= 0 ,0
Exp/Cntr=0.3,0.1

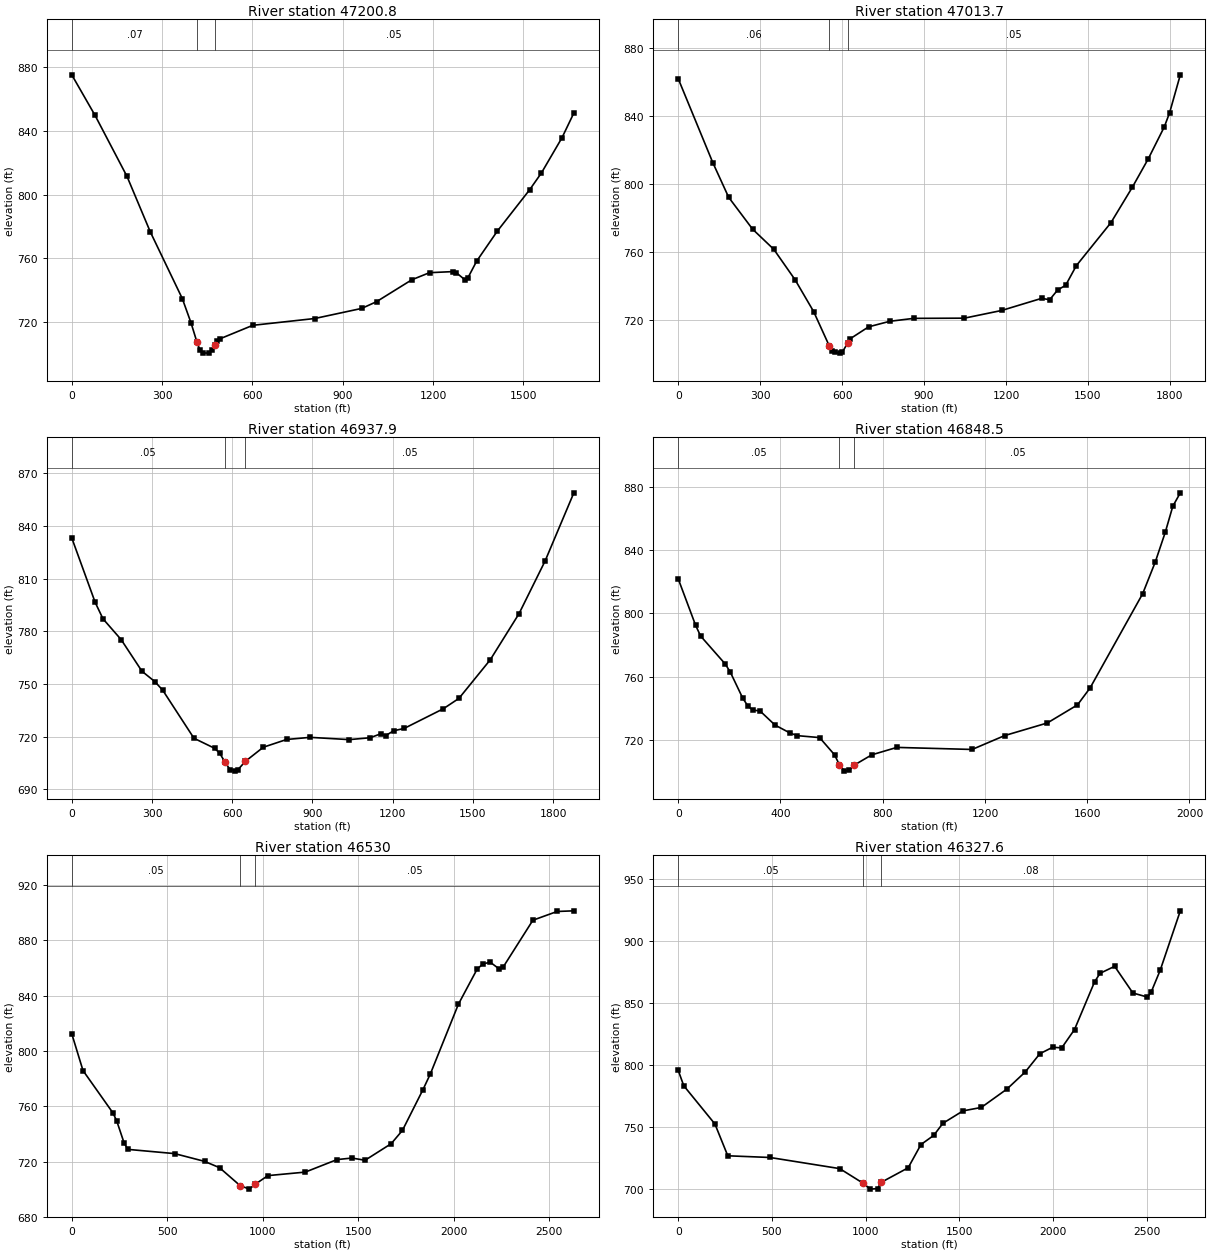
Type RM Length L Ch R = 1 ,47200.8 ,184.9,187.1,189.3
XS GIS Cut Line= 4
     1909217.332      646643.223     1909446.498      646320.306
     1909522.522      646161.691     1909869.242       645122.39
#Sta/Elev= 30
       0  875.02    77.3  849.61   183.5  811.35   260.8  776.61     367  734.86
     396  719.64   415.5  707.67   425.3  702.75   435.1  700.76   454.6  700.63
   464.4  702.38   474.2  705.81   483.9   708.5   493.7  709.72   601.2  718.06
   806.6  722.31   963.2  728.66  1012.1  732.86  1129.4   746.6  1188.1  751.04
  1266.4  751.72  1276.2  751.15  1305.5  746.62  1315.3   747.7  1344.7  758.26
  1413.1  777.01  1520.7     803  1559.9  813.56  1628.3  835.66  1667.5   851.1
#Mann= 3 , 0 , 0
       0     .07       0   415.5    .045       0   474.2     .05       0
Bank Sta=415.5,474.2
XS Rating Curve= 0 ,0
Exp/Cntr=0.3,0.1

Type RM Length L Ch R = 1 ,47013.7 ,75.8,75.8,75.8
XS GIS Cut Line= 4
     1909265.075      646728.292     1909606.221      646381.938
     1909731.221      646155.376     1910046.325      645108.501
#Sta/Elev= 30
       0  861.98   126.4   812.6   184.7   792.1   272.2  773.35     350  761.44
   427.8  743.53   495.7   724.8   553.2  704.48   562.8  701.81   572.4  700.68
   591.6   700.3   601.2  701.06   620.3  706.17   629.9   708.8     697  715.79
   774.2  719.05     862  720.78  1047.5   720.9  1184.2  725.44  1330.6  732.58
  1359.9  731.76  1389.2  737.53  1418.4  740.26  1457.5  751.83  1584.4  777.22
  1662.5  798.03    1721  814.83  1779.6  833.62  1799.1  841.99  1838.2  864.28
#Mann= 3 , 0 , 0
       0     .06       0   553.2    .045       0   620.3     .05       0
Bank Sta=553.2,620.3
XS Rating Curve= 0 ,0
Exp/Cntr=0.3,0.1

Type RM Length L Ch R = 1 ,46937.9 ,88,89.5,90.9
XS GIS Cut Line= 4
     1909330.179      646749.126     1909671.325      646402.771
     1909796.325      646176.209      1910164.38      645105.028
#Sta/Elev= 30
       0   833.3    87.5  796.59   116.7  787.23   184.7  775.37   262.5  757.36
   311.1   751.4   340.3  746.52     457  719.18   534.1  713.48   553.2  710.66
   572.4  705.74   591.6  701.38   610.7  700.46   620.3  701.08   649.1  706.02
   716.2  714.07   803.5  718.49   891.4   719.7  1037.8  718.41    1116  719.48
    1155   721.7  1174.5  720.75  1203.8  723.45  1242.9  724.77  1389.4  735.98
  1447.9   741.9  1565.1   763.9  1672.5  790.13  1770.2   820.2  1877.6  858.99
#Mann= 3 , 0 , 0
       0     .05       0   572.4    .045       0   649.1     .05       0
Bank Sta=572.4,649.1
XS Rating Curve= 0 ,0
Exp/Cntr=0.3,0.1

Type RM Length L Ch R = 1 ,46848.5 ,309,318.5,331.1
XS GIS Cut Line= 4
     1909356.221      646769.959     1909765.075      646397.563
     1909866.637       646220.48     1910390.075      645132.806
#Sta/Elev= 30
       0  821.87    67.9  792.56    87.3  785.79   184.3  767.98   203.8  762.88
   252.3  746.47   271.7  741.69   291.1  738.97   320.2  738.33   378.4  729.47
   436.6  724.48   465.7  722.76     553  721.52   611.4  710.67   630.8  704.23
   650.2  700.32   669.7  700.91   689.1  704.18   757.2  710.63   855.3  715.32
  1149.7  714.02  1277.3  722.81  1444.1  730.78  1561.9  742.21    1611  752.86
    1817  812.52  1866.1  832.49  1905.4  851.36  1934.8  867.79  1964.2  876.29
#Mann= 3 , 0 , 0
       0     .05       0   630.8    .045       0   689.1     .05       0
Bank Sta=630.8,689.1
XS Rating Curve= 0 ,0
Exp/Cntr=0.3,0.1

Type RM Length L Ch R = 1 ,46530   ,202.4,202.4,198.9
XS GIS Cut Line= 5
     1909376.186      646777.771     1910071.498      646320.306
     1910240.769      646158.848     1910643.097      645321.241
     1910841.433      644719.394
#Sta/Elev= 30
       0   812.5    58.8  785.89   215.4  755.28     235   749.6   274.2  733.45
   293.8  728.86   538.6   725.8   695.2  720.19   773.6  715.63     881   702.7
   929.8   700.1     959  703.49  1027.2  709.88  1222.7  712.42    1389  721.48
  1467.3  722.59  1535.7  720.98  1672.7  732.98  1731.4  742.57    1839  772.07
  1878.1  783.58  2024.7  833.92  2122.2  859.14  2151.4  862.88  2190.4  864.36
  2239.2  859.31  2258.7  860.69  2414.7  894.66  2541.4  900.98  2629.1  901.45
#Mann= 3 , 0 , 0
       0     .05       0     881    .045       0     959     .05       0
Bank Sta=881,959
XS Rating Curve= 0 ,0
Exp/Cntr=0.3,0.1

Type RM Length L Ch R = 1 ,46327.6 ,239,248.2,257.5
XS GIS Cut Line= 5
      1909410.04      646780.376     1910232.957      646346.348
     1910425.665      646223.952     1911192.914      646146.544
      1911896.12      645886.929
#Sta/Elev= 30
       0  795.69    29.4  783.38   195.9  752.52   264.4  726.95   489.7  725.58
   861.8  716.62   987.4  704.78  1025.5   700.1  1063.5  700.57  1082.6  705.52
    1227  717.28  1295.3     736  1363.6  743.39  1412.4  753.12  1519.8  763.12
  1617.4  765.88  1754.1  780.68  1851.7  794.44  1929.8  809.15  1997.9  814.33
  2046.6  813.88  2114.8  828.63  2221.8  867.02    2251  873.89  2328.9  879.53
  2426.3  858.04  2504.2  854.75  2523.6  858.69  2572.3  876.47  2679.4  924.22
#Mann= 3 , 0 , 0
       0     .05       0   987.4    .045       0  1082.6     .08       0
Bank Sta=987.4,1082.6
XS Rating Curve= 0 ,0
Exp/Cntr=0.3,0.1

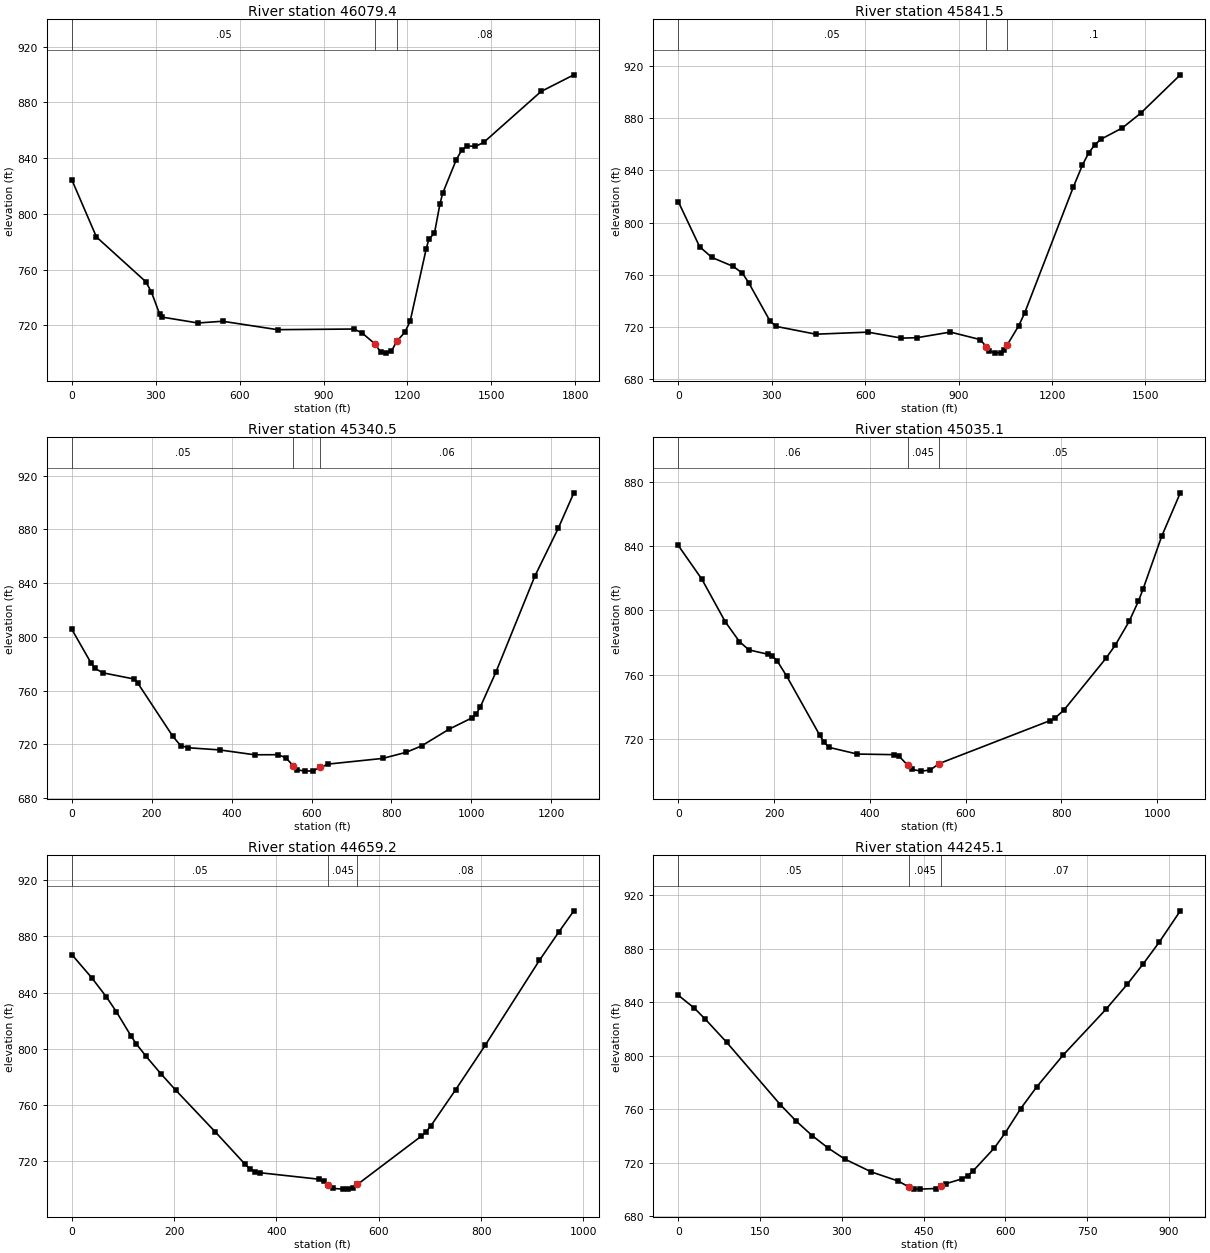
Type RM Length L Ch R = 1 ,46079.4 ,233.8,237.9,242.1
XS GIS Cut Line= 4
     1909355.353      646819.438     1910251.186      646530.376
     1910563.686      646483.501     1911100.144      646452.251
#Sta/Elev= 30
       0  824.53    88.2  783.42   264.7  751.31   284.4  744.05   313.8  728.26
   323.6  725.92     451  721.73   539.3  722.96   735.4  716.93  1008.3  717.39
  1037.1  714.67    1085  706.49  1104.1  700.74  1123.2   700.1  1142.4  701.44
  1161.6   708.5  1190.3  715.05  1209.4  722.82  1267.1  775.06  1276.8  782.02
  1296.4   786.1  1315.9  806.94  1325.7  814.72  1374.6  838.91  1394.1  845.79
  1413.6  848.75    1443  848.41  1472.3  851.23  1677.4  887.79  1794.7  899.75
#Mann= 3 , 0 , 0
       0     .05       0    1085    .045       0  1161.6     .08       0
Bank Sta=1085,1161.6
XS Rating Curve= 0 ,0
Exp/Cntr=0.3,0.1

Type RM Length L Ch R = 1 ,45841.5 ,486.1,501,515.1
XS GIS Cut Line= 4
     1909373.582      646855.896     1910258.998      646736.105
     1910506.394      646743.917     1910954.311      646889.751
#Sta/Elev= 30
       0  816.08    68.7  781.51     108  773.31   176.7  766.43   206.2  761.24
   225.8  754.12   294.6  724.69   314.2  720.55   441.8  714.59   608.8  716.15
   716.8  711.59   765.8  711.87   873.8  716.21   969.6  710.46   988.7  705.15
   998.2  701.87  1017.2   700.1  1036.3   700.5  1045.8  702.34  1055.3  705.96
  1093.4   721.1  1112.4  730.89  1268.6  827.17    1298  844.05  1317.6  853.14
  1337.3  859.43  1356.9  863.72  1425.6  872.33  1484.5  883.57  1612.1  913.02
#Mann= 3 , 0 , 0
       0     .05       0   988.7    .045       0  1055.3      .1       0
Bank Sta=988.7,1055.3
XS Rating Curve= 0 ,0
Exp/Cntr=0.3,0.1

Type RM Length L Ch R = 1 ,45340.5 ,307.8,305.4,303.7
XS GIS Cut Line= 4
     1909391.811      646892.355     1909907.436      646884.542
      1910035.04      646988.709     1910397.019      647436.626
#Sta/Elev= 30
       0  805.67    48.6  780.36    58.4  776.49    77.8  773.24   155.7  768.65
   165.4  765.48     253  725.94   272.4  719.09   291.9  717.48   369.7  715.89
   457.3  712.27   515.7  712.32   535.1  710.16   554.4  704.07   564.1  701.07
   583.5   700.1   602.9  700.33   622.3  702.86   641.6  705.34     778  709.56
   836.6  714.08   875.6  718.91     944  731.28  1002.5  739.89  1012.3  742.87
    1022   747.7  1061.1  773.62  1158.7  845.17  1217.3  880.78  1256.3  907.17
#Mann= 3 , 0 , 0
       0     .05       0   554.4    .045       0   622.3     .06       0
Bank Sta=554.4,622.3
XS Rating Curve= 0 ,0
Exp/Cntr=0.3,0.1

Type RM Length L Ch R = 1 ,45035.1 ,371.6,375.9,380.2
XS GIS Cut Line= 4
     1909331.915      646949.646     1909713.999      647130.777
     1909839.728      647212.667     1910206.915      647514.751
#Sta/Elev= 30
       0  840.41    49.2  819.47    98.3  792.89   127.8  780.62   147.5  775.46
   186.8  772.79   196.7  771.62   206.5  768.66   226.2  759.28     295   722.7
   304.8  717.95   314.7  714.89   373.7  710.73     451  710.34   460.4  709.59
   479.1  703.79   488.5  701.14   507.2  700.11     526  700.77   544.8  704.79
   776.7  731.55   786.4  732.99   805.8  738.22   893.1  770.24   912.5  778.36
   941.6  793.21     961   805.8   970.7  813.32  1009.6  846.14  1048.4  873.09
#Mann= 3 , 0 , 0
       0     .06       0   479.1    .045       0   544.8     .05       0
Bank Sta=479.1,544.8
XS Rating Curve= 0 ,0
Exp/Cntr=0.3,0.1

Type RM Length L Ch R = 1 ,44659.2 ,401.1,414.1,422
XS GIS Cut Line= 4
     1909235.561      647048.605     1909484.917      647405.866
     1909600.144      647517.355     1909877.532      647784.652
#Sta/Elev= 30
       0  867.09    38.7  850.68    67.8  836.85    87.1   826.4   116.2  808.88
   125.9  803.58   145.2  794.62   174.3  782.17   203.3  770.49   280.8   740.7
   338.9  717.74   348.5  714.44   358.2  712.51   367.9  711.77   482.8  707.19
   492.3  705.55   501.7  702.74   511.1  700.62     530  700.11   539.4  700.23
   548.8  701.26   558.3  703.46   682.7  737.71   692.3  740.83     702  745.28
   750.1   770.8   807.9  802.45   913.8  862.87   952.3  883.37   981.2  898.18
#Mann= 3 , 0 , 0
       0     .05       0   501.7    .045       0   558.3     .08       0
Bank Sta=501.7,558.3
XS Rating Curve= 0 ,0
Exp/Cntr=0.3,0.1

Type RM Length L Ch R = 1 ,44245.1 ,404.7,397.1,394.5
XS GIS Cut Line= 3
     1909068.918      647177.037      1909172.06      647617.794
     1909376.014      648039.276
#Sta/Elev= 30
       0  845.26    29.5  835.56    49.2  827.48    88.6   810.1     187  763.43
   216.5  750.94     246  740.02   275.5  730.69   305.1  722.68   354.3  712.96
   403.5  706.16   423.1  701.69     433  700.36   442.8   700.1   472.2  700.56
   481.9   702.1   491.7  704.25     521  707.85   530.7  710.05   540.5  713.57
   579.5  730.76     599  741.74   628.2  760.39   657.5  776.62   706.3  800.58
   784.3  834.59   823.4  853.33   852.6  868.55   881.9  884.75   920.9  908.39
#Mann= 3 , 0 , 0
       0     .05       0   423.1    .045       0   481.9     .07       0
Bank Sta=423.1,481.9
XS Rating Curve= 0 ,0
Exp/Cntr=0.3,0.1