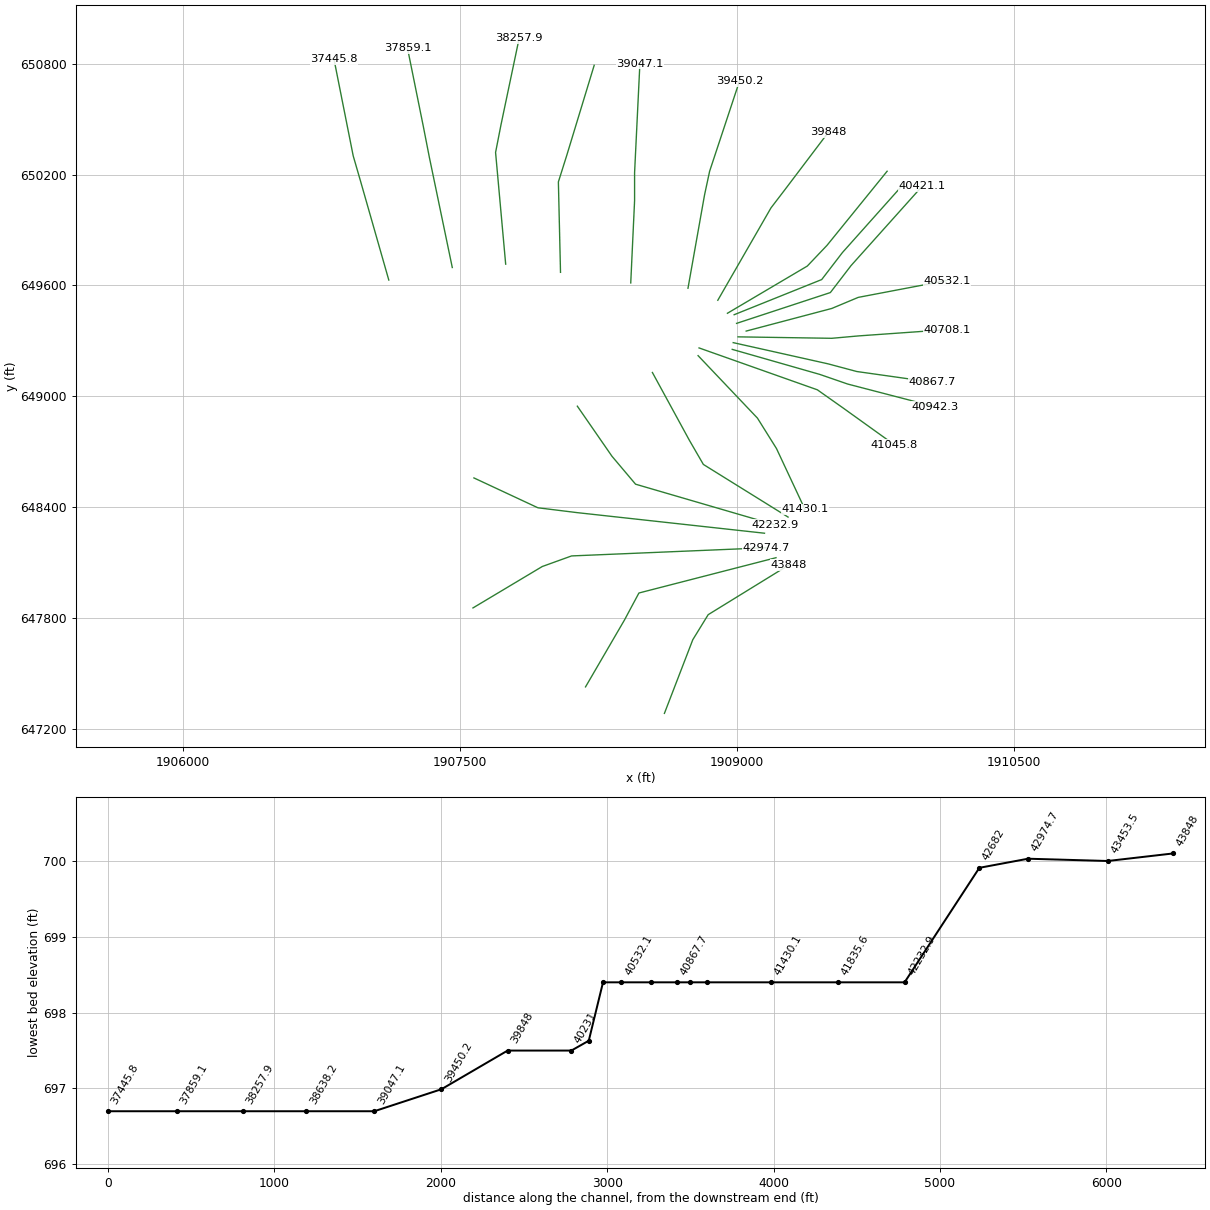
HEC-RAS study HenryFork.prj: HenryFork

--- HenryFork.g01 (geometry) --- (continued)

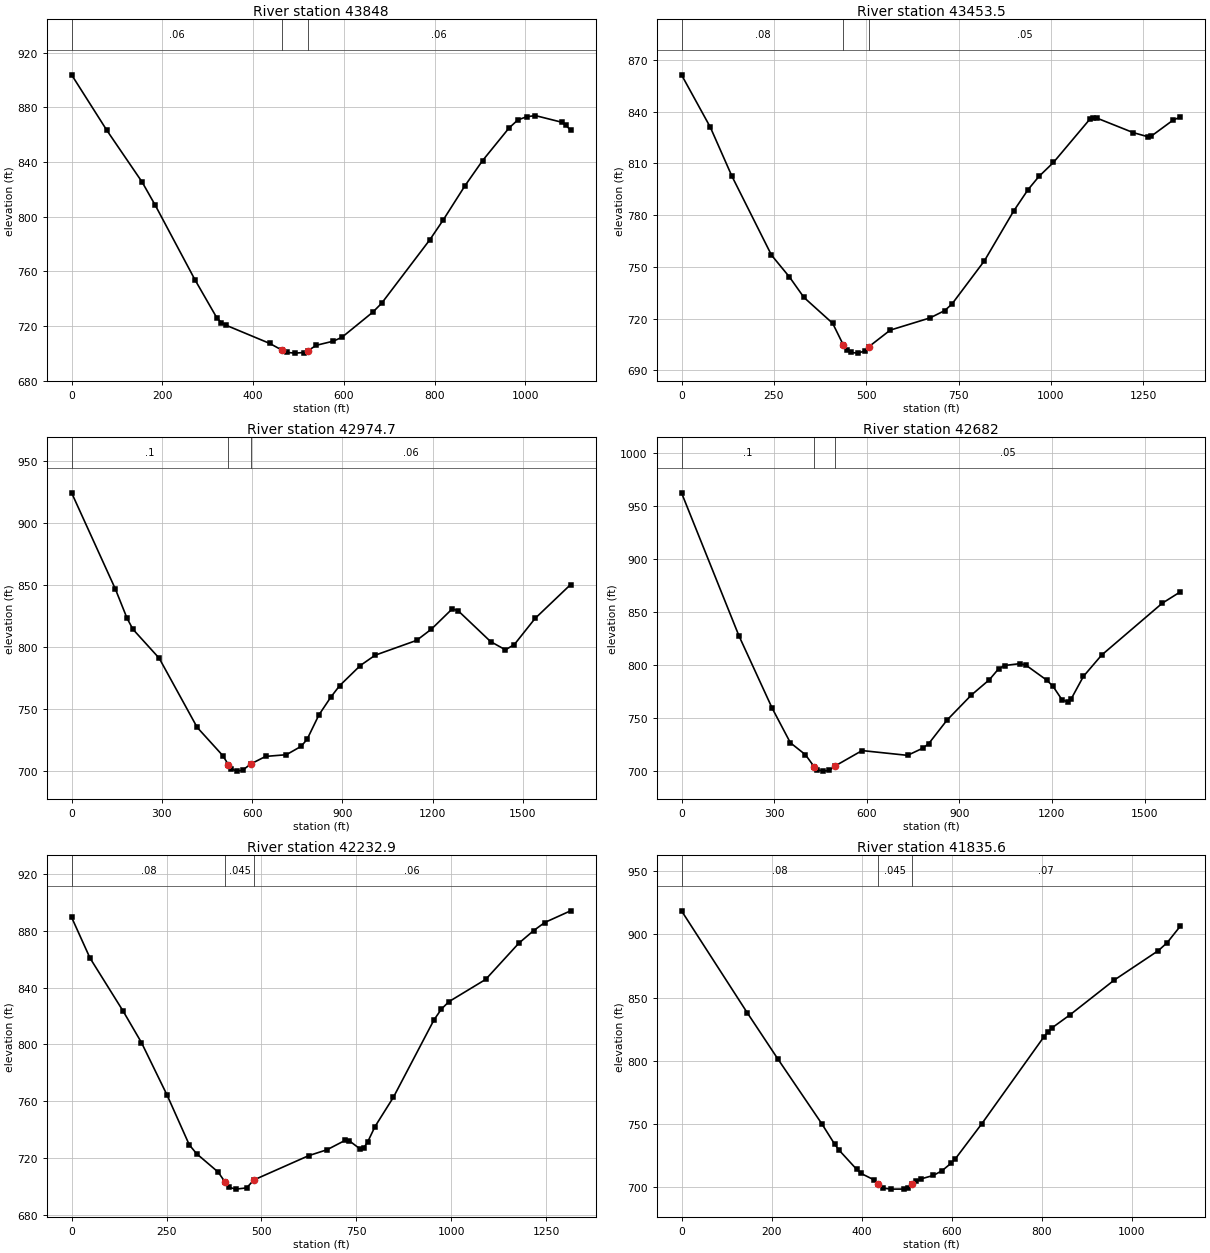
Type RM Length L Ch R = 1 ,43848   ,392.8,394.5,396.3
XS GIS Cut Line= 4
     1908607.957      647285.584     1908761.603      647684.021
     1908844.936      647819.438     1909282.079      648088.414
#Sta/Elev= 30
       0  903.83    77.6   863.2   155.3  825.35   184.4  808.29   271.8  753.78
   320.3  725.74     330   722.4   339.7   720.6   436.4  707.21   464.4  702.14
   473.8  700.63   492.5   700.1   511.2  700.54   520.6  701.84   539.3  705.86
   576.7  708.87   595.7  711.72   663.5  730.06   682.9  736.54   789.4  783.16
   818.5  797.46   866.9  822.75   905.6  841.11   963.7  864.89   983.1   870.8
  1002.5  873.14  1021.8  873.99  1079.9  869.13  1089.6  866.75  1099.3  863.22
#Mann= 3 , 0 , 0
       0     .06       0   464.4    .045       0   520.6     .06       0
Bank Sta=464.4,520.6
XS Rating Curve= 0 ,0
Exp/Cntr=0.3,0.1

Type RM Length L Ch R = 1 ,43453.5 ,495.3,478.8,462.1
XS GIS Cut Line= 4
     1908180.873      647428.813     1908391.811      647790.792
     1908469.936      647936.626     1909212.187      648127.589
#Sta/Elev= 30
       0  861.34      78  830.95   136.4   802.6   243.6   756.8   292.3  744.12
   331.3  732.32   409.2  717.28   438.4  704.61   448.2  701.79   457.9   700.4
   477.4     700   496.8   701.3   506.5   703.6   564.9  713.32   672.8  720.42
   712.1  724.61   731.8  728.35   820.2  753.58   898.8  782.24   938.1  794.77
   967.6  802.42  1006.9  810.54  1105.2  835.56    1115  836.59  1124.8  836.23
  1223.1  827.82  1262.4  825.47  1272.2  825.87  1331.2  835.14  1350.8  836.83
#Mann= 3 , 0 , 0
       0     .08       0   438.4    .045       0   506.5     .05       0
Bank Sta=438.4,506.5
XS Rating Curve= 0 ,0
Exp/Cntr=0.3,0.1

Type RM Length L Ch R = 1 ,42974.7 ,302.9,292.7,282.5
XS GIS Cut Line= 4
     1907571.498      647855.896     1907946.498      648079.855
     1908105.353      648137.146     1909157.428      648181.288
#Sta/Elev= 30
       0  924.01   145.6   846.5   184.4     823   203.8  814.22   291.2  790.89
   417.4  735.23   502.5  712.54   521.2  705.22   530.6  701.86   549.4  700.03
   568.1  700.71   596.3  705.89     645  711.88   713.9  713.23   763.1  720.01
   782.8  725.62   822.2   745.3   861.5  759.51     891  768.81   959.9  785.04
  1009.1  793.33  1146.9  805.25  1196.1   814.3    1265  830.54  1284.7  829.17
    1393  804.26  1442.2  797.66  1471.7  801.89  1540.6  822.88  1658.7  850.15
#Mann= 3 , 0 , 0
       0      .1       0   521.2    .045       0   596.3     .06       0
Bank Sta=521.2,596.3
XS Rating Curve= 0 ,0
Exp/Cntr=0.3,0.1

Type RM Length L Ch R = 1 ,42682   ,466.2,449.2,432.1
XS GIS Cut Line= 4
     1907576.707      648559.021     1907923.061      648397.563
     1908133.998      648371.521     1909149.743      648259.994
#Sta/Elev= 30
       0  962.65   186.2  827.54     294  759.14   352.7  726.68   401.5  715.39
   430.4  703.82   440.1  701.08   459.4  699.91   478.8   700.6   498.1  704.86
     585  719.31   732.2   714.8   781.4  721.52     801  725.91     860  748.02
   938.6  771.62   997.5  786.25    1027  796.39  1046.6  799.62  1095.8  801.37
  1115.4  800.03  1184.2  785.61  1203.9  779.82  1233.3  767.03    1253  765.29
  1262.8  768.26  1302.1  789.38  1361.1  809.46  1557.6  858.46  1616.5  869.24
#Mann= 3 , 0 , 0
       0      .1       0   430.4    .045       0   498.1     .05       0
Bank Sta=430.4,498.1
XS Rating Curve= 0 ,0
Exp/Cntr=0.3,0.1

Type RM Length L Ch R = 1 ,42232.9 ,401.3,397.2,393.1
XS GIS Cut Line= 4
     1908136.603      648947.042     1908324.103      648676.209
     1908451.707      648525.167     1909207.757      648304.795
#Sta/Elev= 30
       0  889.31    48.4  860.74   135.6   823.5   184.1   801.3   251.9  764.24
     310  729.52   329.4  723.26   385.9  710.42   404.7  703.23   414.1   699.7
     433   698.4   461.2  699.28     480  704.82   624.4  721.89     673  726.07
   721.6  732.79   731.3  732.39   760.5  726.55   770.2  727.61   779.9  731.47
   799.4  742.37     848  763.01   954.9  817.35   974.4  824.89   993.8  830.03
    1091  845.73  1178.5  871.21  1217.4  880.01  1246.6  885.69  1314.6  893.89
#Mann= 3 , 0 , 0
       0     .08       0   404.7    .045       0     480     .06       0
Bank Sta=404.7,480
XS Rating Curve= 0 ,0
Exp/Cntr=0.3,0.1

Type RM Length L Ch R = 1 ,41835.6 ,404.9,405.5,406.2
XS GIS Cut Line= 4
     1908542.853      649129.334     1908743.373      648762.146
     1908818.894      648631.938     1909277.422      648347.287
#Sta/Elev= 30
       0  918.66   145.9  838.06     214  801.45   311.4  750.29   340.5  733.84
   350.3  729.15   389.2  714.04   398.9  710.82   427.8  705.72   437.2  702.14
   446.6  699.29   465.4   698.4   493.6  698.44     503  699.55   512.4  702.26
   521.9  704.78   531.3  706.41   559.5  709.24   578.7  712.92   598.3  718.71
   608.2  722.29     667  750.06   804.4  818.55   814.2  822.94     824  826.25
   863.3  836.39   961.4  863.84  1059.5  887.17  1079.2  893.52  1108.6  906.68
#Mann= 3 , 0 , 0
       0     .08       0   437.2    .045       0   512.4     .07       0
Bank Sta=437.2,512.4
XS Rating Curve= 0 ,0
Exp/Cntr=0.3,0.1

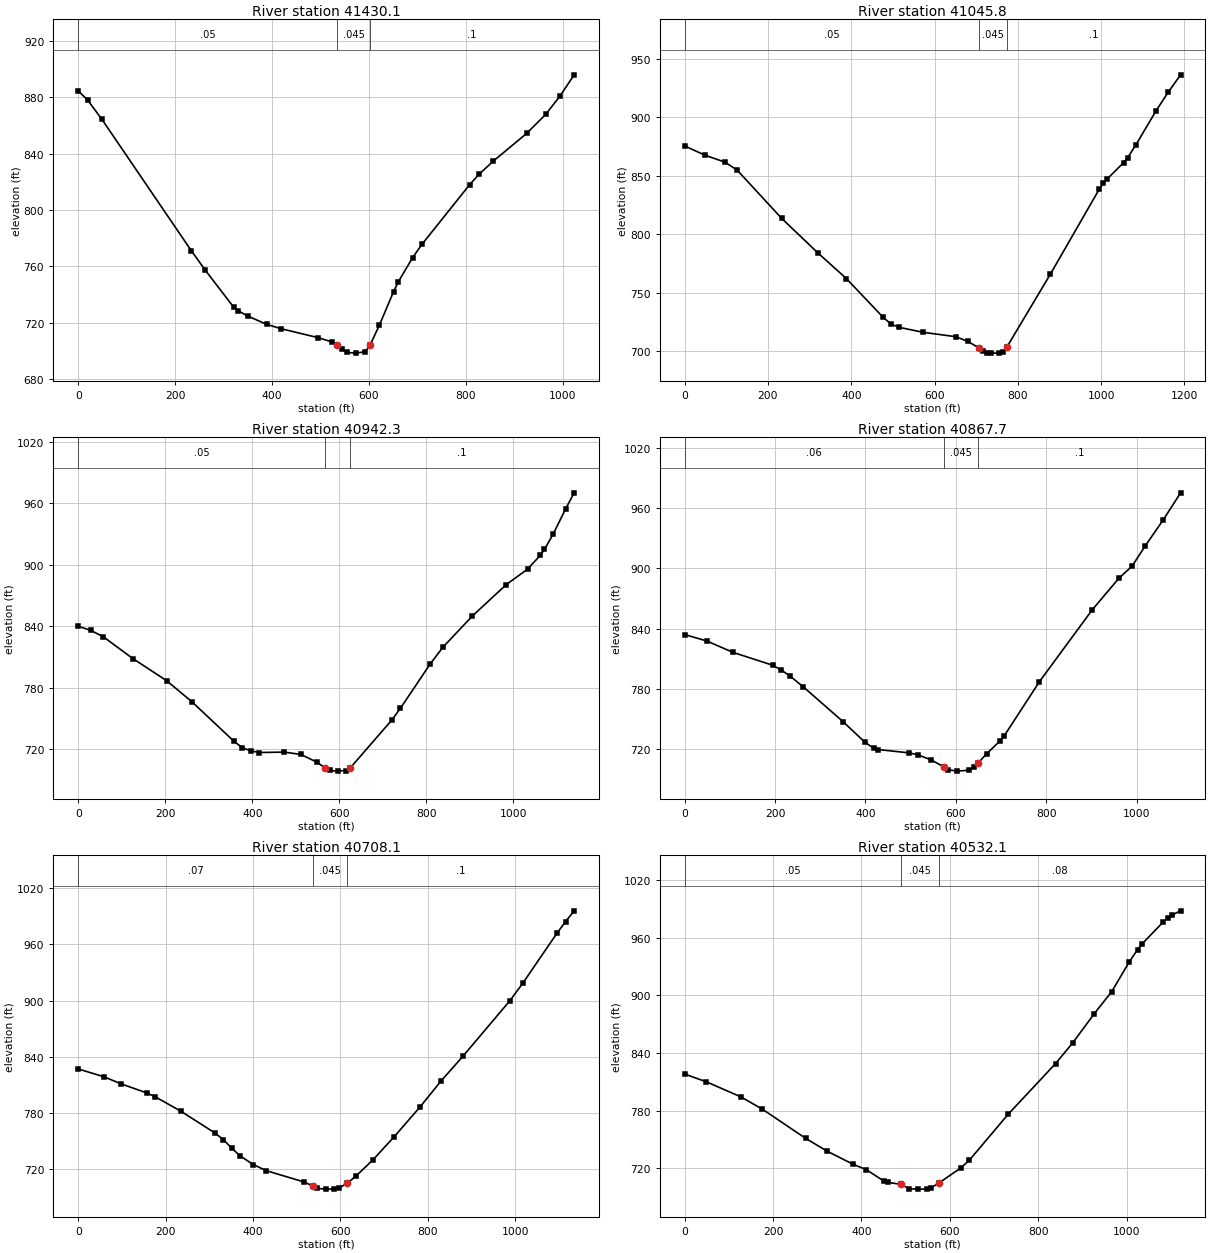
Type RM Length L Ch R = 1 ,41430.1 ,375.3,384.3,393.2
XS GIS Cut Line= 4
     1908790.248       649220.48     1909111.722       648882.44
     1909214.728      648717.876     1909368.838      648389.079
#Sta/Elev= 30
       0  884.48    19.4  877.98    48.6  864.46   233.2  771.21   262.4   757.2
   320.7   731.1   330.4  728.42   349.9  724.72   388.7  718.88   417.9  715.81
   495.6  709.34   524.7  706.23   534.4  704.52   544.2  701.09   553.9  698.93
   573.3   698.4   592.7   699.4   602.4  704.03   621.8   718.3   650.9  741.95
   660.6  748.88   690.1  766.05   709.7  775.64   807.8  817.82   827.5  825.32
   856.9  834.65   925.6  854.28   964.9  867.75   994.3  880.69  1023.8  895.88
#Mann= 3 , 0 , 0
       0     .05       0   534.4    .045       0   602.4      .1       0
Bank Sta=534.4,602.4
XS Rating Curve= 0 ,0
Exp/Cntr=0.3,0.1

Type RM Length L Ch R = 1 ,41045.8 ,97.2,103.6,109.9
XS GIS Cut Line= 4
     1908795.457      649262.146     1909436.082      649035.584
     1909574.104      648938.202     1909852.295      648738.853
#Sta/Elev= 30
       0  875.37    48.5  867.49    97.1  861.46   126.2  854.61     233  813.45
   320.3  783.84   388.3  762.05   475.7  729.27   495.1   723.3   514.5  720.44
   572.7  716.19   650.4  712.44   679.5  708.51   707.7   702.6     717  699.85
   726.4  698.55   735.8   698.4   754.6  698.42     764  699.76   773.4  703.47
   877.8  765.74   995.1  838.25  1004.9  843.31  1014.7  847.27  1053.8  861.09
  1063.6  865.35  1083.1  876.18    1132  905.51  1161.3  921.49  1190.7   936.1
#Mann= 3 , 0 , 0
       0     .05       0   707.7    .045       0   773.4      .1       0
Bank Sta=707.7,773.4
XS Rating Curve= 0 ,0
Exp/Cntr=0.3,0.1

Type RM Length L Ch R = 1 ,40942.3 ,73,74.6,76.2
XS GIS Cut Line= 4
     1908975.144      649254.334     1909449.103      649118.917
     1909600.144      649066.834     1910071.498      648944.438
#Sta/Elev= 30
       0  839.97      29  835.85      58  829.57   125.6  808.35     203  786.81
     261  766.26   357.6   727.7   376.9  721.28   396.3  718.27   415.6  716.59
   473.6  716.99   511.7  714.69   549.3  706.98   568.1  701.22   577.5  699.02
   596.3   698.4   615.1     699   624.5  701.24   720.9   748.4   740.4  759.77
   808.5  802.84   837.8  819.32   905.9     850   983.8  880.65  1032.5   895.7
  1061.8  909.17  1071.5  915.08    1091  929.57  1120.2   954.7  1139.7  970.28
#Mann= 3 , 0 , 0
       0     .05       0   568.1    .045       0   624.5      .1       0
Bank Sta=568.1,624.5
XS Rating Curve= 0 ,0
Exp/Cntr=0.3,0.1

Type RM Length L Ch R = 1 ,40867.7 ,151.7,159.6,167.5
XS GIS Cut Line= 4
     1908980.353      649290.792     1909493.373      649176.209
     1909649.623      649134.542     1910055.873      649077.251
#Sta/Elev= 30
       0  834.25    48.7  827.92   107.1  816.53   194.7  803.76   214.2  798.89
   233.6  792.81   262.8  782.12   350.4  747.66   399.1  727.05   418.6  721.07
   428.3  719.85   496.5  716.58   515.9  714.68   544.7  709.67   573.2  702.81
   582.7  699.94   601.8   698.4   630.3  699.34   639.8  702.06   649.3  706.43
   668.4   715.7   697.1  728.11   706.9   733.3     785  787.32   902.3  859.08
   960.9  890.22   990.2  902.38  1019.5  922.61  1058.6  948.04  1097.6  975.28
#Mann= 3 , 0 , 0
       0     .06       0   573.2    .045       0   649.3      .1       0
Bank Sta=573.2,649.3
XS Rating Curve= 0 ,0
Exp/Cntr=0.3,0.1

Type RM Length L Ch R = 1 ,40708.1 ,168.9,175.9,183
XS GIS Cut Line= 4
     1909006.394      649322.042     1909514.207       649314.23
      1909660.04      649327.251     1910139.207      649361.105
#Sta/Elev= 30
       0  826.83    58.6  818.53    97.7  810.97   156.3  801.32   175.8  797.19
   234.4  781.82   312.5  758.49   332.1   751.3   351.6  741.93   371.1  733.68
   400.4  724.72   429.7  718.19   517.6  705.94   537.2  701.53   546.9  699.21
   566.4   698.4     586  698.51   595.7  699.44   615.2  704.56   634.8  712.11
   673.9  729.49   722.9  754.43   781.7  786.06   830.8  814.38   879.8  840.22
   987.6  899.81    1017  918.43  1095.4     972    1115  984.38  1134.6  995.86
#Mann= 3 , 0 , 0
       0     .07       0   537.2    .045       0   615.2      .1       0
Bank Sta=537.2,615.2
XS Rating Curve= 0 ,0
Exp/Cntr=0.3,0.1

Type RM Length L Ch R = 1 ,40532.1 ,98.2,111,123.8
XS GIS Cut Line= 4
     1909050.665      649353.292     1909514.207      649475.688
     1909657.436      649535.584     1910136.603       649626.73
#Sta/Elev= 30
       0  818.05    48.9  810.04   127.2  794.34   176.1  781.47     274  751.13
   322.9  737.75   381.6  724.13   410.9   718.7   450.1  706.96   459.9  705.44
   489.1  703.38   508.5  698.72   527.9   698.4   547.4  698.44     557  699.58
   576.5  705.14     625  720.48   644.4  728.53   732.2  776.32   839.5  829.04
   878.6  850.76   927.3  881.04   966.4  903.76  1005.4  934.11  1024.9  947.56
  1034.6  953.14  1083.4  976.38  1093.2  980.32  1102.9  983.48  1122.4  987.82
#Mann= 3 , 0 , 0
       0     .05       0   489.1    .045       0   576.5     .08       0
Bank Sta=489.1,576.5
XS Rating Curve= 0 ,0
Exp/Cntr=0.3,0.1

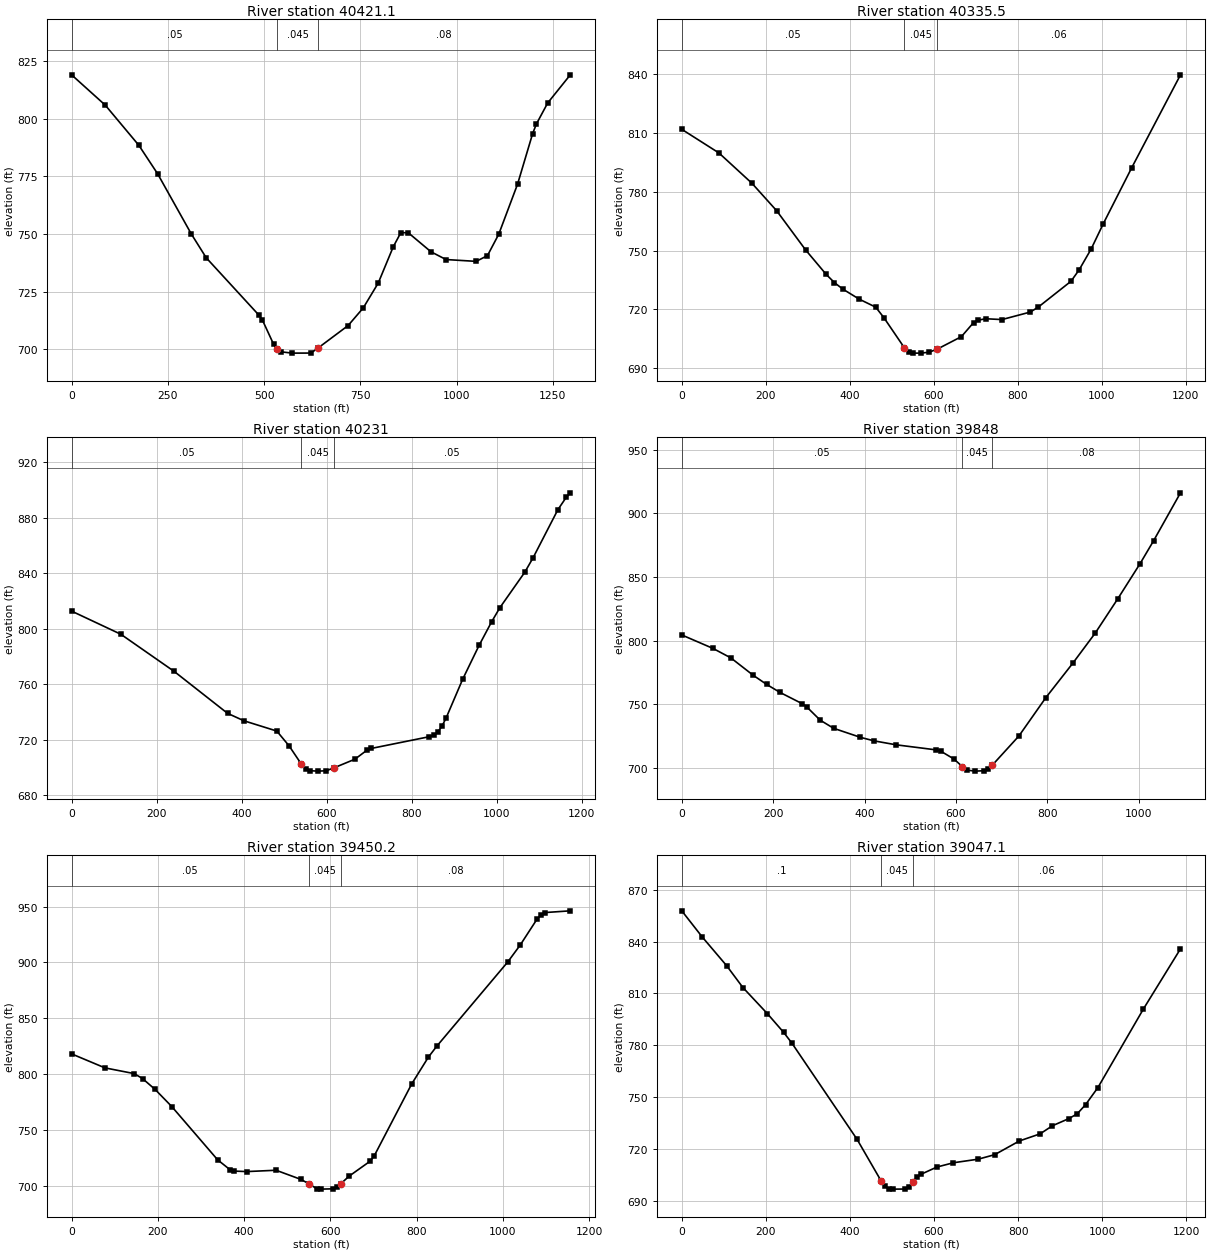
Type RM Length L Ch R = 1 ,40421.1 ,86.8,85.6,84.6
XS GIS Cut Line= 4
     1908998.582      649394.959     1909506.394      649561.626
     1909618.373      649707.459      1910003.79      650137.146
#Sta/Elev= 30
       0  818.98    87.5  805.84   174.9   788.4   223.5   776.1     311  750.02
   349.8   739.7   485.9  714.98   495.6  712.76   524.8  702.22   534.5   700.2
   544.1  698.96   573.2   698.4   621.6  698.43   640.9   700.7   718.3  710.35
   757.5  717.96   796.6  728.78   835.7  744.52   855.3  750.62   874.9  750.52
   933.6  742.31   972.7  738.95    1051  738.16  1080.3  740.65  1109.7  749.95
  1158.6  771.67  1197.7  793.55  1207.5  797.71  1236.8   806.8  1295.5  818.99
#Mann= 3 , 0 , 0
       0     .05       0   534.5    .045       0   640.9     .08       0
Bank Sta=534.5,640.9
XS Rating Curve= 0 ,0
Exp/Cntr=0.3,0.1

Type RM Length L Ch R = 1 ,40335.5 ,106.7,104.5,102.3
XS GIS Cut Line= 4
     1908985.561      649441.834     1909459.519      649631.938
     1909571.498      649777.771     1909899.623      650144.959
#Sta/Elev= 30
       0  811.88    88.4  799.82     167  784.34   225.9   770.3   294.6  750.35
   343.7  737.82   363.4  733.62     383  730.36   422.3  725.19   461.6   721.1
   481.2  715.69     530   700.3   539.7  698.37   549.4  697.64   568.7  697.63
   588.1  698.08   607.4   699.6   665.5  706.04   694.5  713.21   704.2  714.41
   723.5  715.18   762.1  714.76   829.7  718.61     849  721.21   926.3   734.3
   945.6  740.07   974.5  750.84  1003.5   763.8  1071.1  792.34    1187   839.7
#Mann= 3 , 0 , 0
       0     .05       0     530    .045       0   607.4     .06       0
Bank Sta=530,607.4
XS Rating Curve= 0 ,0
Exp/Cntr=0.3,0.1

Type RM Length L Ch R = 1 ,40231   ,380.6,383,385.1
XS GIS Cut Line= 4
     1908949.103      649449.646     1909381.394      649704.855
     1909488.165      649816.834     1909813.686      650217.876
#Sta/Elev= 30
       0  812.78   115.8  796.12   241.4  769.32   366.8  739.15   405.5  733.76
   482.7  726.38   511.7  715.67   540.7  702.46   550.4  699.09     560  697.81
   579.4   697.5   598.7  697.74     618  699.96   666.5   706.1   695.7  712.79
   705.5  713.88   841.9  722.33   851.6  723.24   861.4  725.64   871.1  729.79
   880.9  735.68   919.9  763.63   958.8  788.21   988.1  805.08  1007.6  815.29
    1066  840.75  1085.5  851.12    1144  885.87  1163.5   894.7  1173.2     898
#Mann= 3 , 0 , 0
       0     .05       0   540.7    .045       0     618     .05       0
Bank Sta=540.7,618
XS Rating Curve= 0 ,0
Exp/Cntr=0.3,0.1

Type RM Length L Ch R = 1 ,39848   ,387.8,397.8,407.8
XS GIS Cut Line= 4
     1908897.019      649519.959     1909185.007      650019.686
     1909258.998      650116.313     1909496.351      650429.527
#Sta/Elev= 30
       0  804.53    68.4  793.93   107.5  786.48   156.4  772.82   185.7  765.66
   215.1  759.34     264  750.42   273.7  747.91     303  737.54   332.4  731.15
     391  724.06   420.4  721.32   469.2  718.18   557.2  714.18     567  713.14
   595.5  707.07   614.2  701.02   623.6  698.32   642.3   697.5     661  697.81
   670.4  699.26   679.8  702.25   737.8  725.09   796.7   755.2   855.7  782.26
   904.8  805.94   953.9  832.76    1003  860.55  1032.5  878.48  1091.5  916.24
#Mann= 3 , 0 , 0
       0     .05       0   614.2    .045       0   679.8     .08       0
Bank Sta=614.2,679.8
XS Rating Curve= 0 ,0
Exp/Cntr=0.3,0.1

Type RM Length L Ch R = 1 ,39450.2 ,398.3,403.1,407.8
XS GIS Cut Line= 4
     1908735.561      649585.063       1908825.3      650090.096
     1908852.748      650217.876     1909014.207      650704.855
#Sta/Elev= 30
       0  818.08    77.4  805.55   145.2  800.42   164.5  795.98   193.6  786.29
   232.3  770.95   338.7  723.24   367.8  714.28   377.4  713.14   406.5   712.7
   474.2   713.9   531.6  705.74   550.3  701.82     569  697.25   578.3  696.99
   606.3  697.27   615.6  698.82     625  702.02   643.6  708.59     692  721.88
   701.7  726.61   788.8  791.14   827.6  815.21   846.9  824.92  1011.5  900.33
  1040.5  915.51  1079.2  938.53  1088.9  942.51  1098.6  944.64  1156.7  946.17
#Mann= 3 , 0 , 0
       0     .05       0   550.3    .045       0     625     .08       0
Bank Sta=550.3,625
XS Rating Curve= 0 ,0
Exp/Cntr=0.3,0.1

Type RM Length L Ch R = 1 ,39047.1 ,415.8,408.9,402
XS GIS Cut Line= 4
     1908425.665      649613.709     1908446.489      650059.106
     1908446.498      650210.063     1908475.144      650798.605
#Sta/Elev= 30
       0  857.79    48.5   842.7   106.6  826.05   145.4  813.38   203.6  798.26
   242.3  787.42   261.7  781.28   416.8  725.56   474.2  701.41   483.6  698.37
   493.1  696.94   502.5   696.7   530.8  696.75   540.2  697.84   549.7  700.97
   559.1  703.81   568.5  705.24   606.7  709.48   645.9  711.96   704.9  714.03
   744.2  716.64   803.1   724.6   852.2  728.69   881.6  733.39   920.9  737.55
   940.6  740.32   960.2  745.54   989.7  755.48  1097.7  800.88  1186.1  835.79
#Mann= 3 , 0 , 0
       0      .1       0   474.2    .045       0   549.7     .06       0
Bank Sta=474.2,549.7
XS Rating Curve= 0 ,0
Exp/Cntr=0.3,0.1

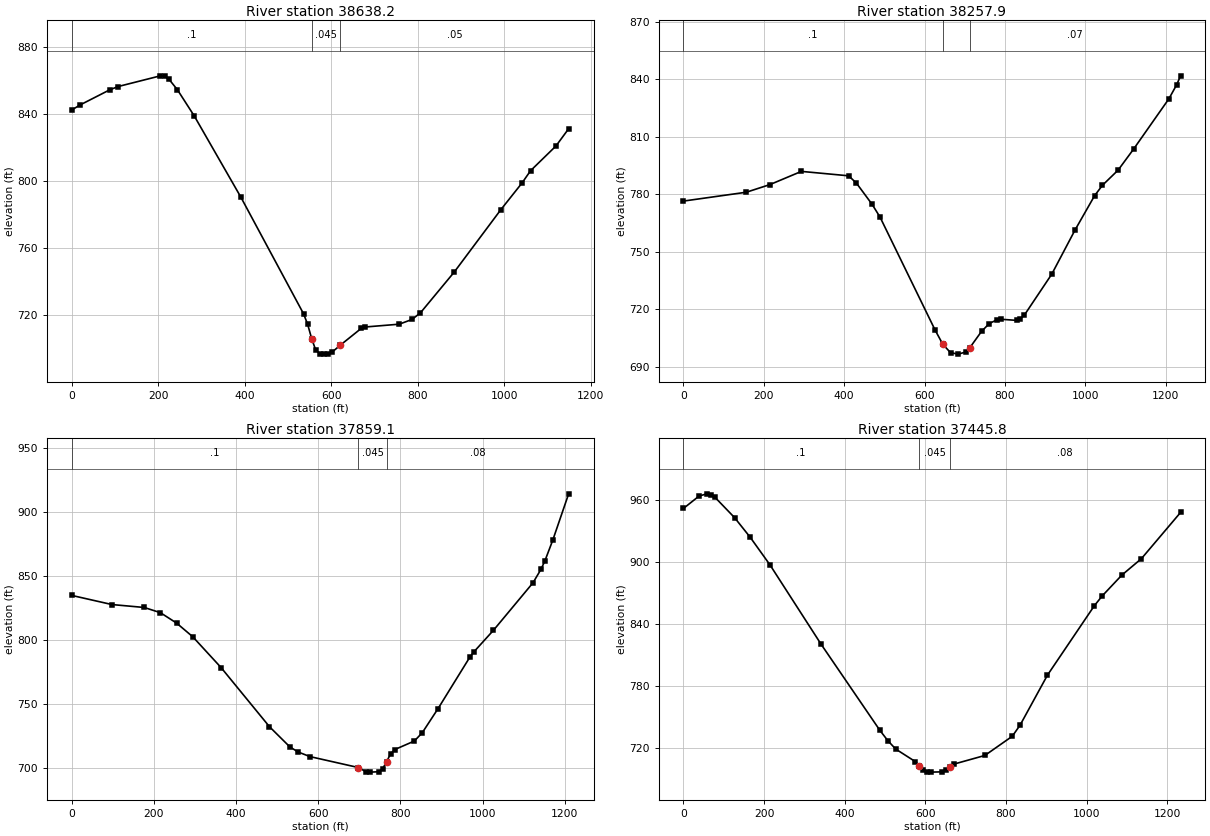
Type RM Length L Ch R = 1 ,38638.2 ,377.8,380.4,382.9
XS GIS Cut Line= 4
     1908045.457      649671.001     1908033.905      650160.007
     1908079.311      650303.813     1908227.748      650790.792
#Sta/Elev= 30
       0  842.15    19.6  845.22      88  854.22   107.6  856.22   205.4  862.61
   215.2  862.25     225  860.65   244.6  854.36   283.7  838.68   391.3  790.32
   536.3  720.74   545.7  714.51   555.1  705.88   564.5  699.06     574  696.95
   583.4   696.7   592.8  696.88   602.2  697.88   621.1  702.01   669.3  711.98
   679.1  712.88   757.4  714.55   786.8  717.35   806.4   721.3   884.7  745.67
   992.4  782.86  1041.4  798.78  1060.9  806.02  1119.7  820.79    1149  831.07
#Mann= 3 , 0 , 0
       0      .1       0   555.1    .045       0   621.1     .05       0
Bank Sta=555.1,621.1
XS Rating Curve= 0 ,0
Exp/Cntr=0.3,0.1

Type RM Length L Ch R = 1 ,38257.9 ,390.1,398.8,407.4
XS GIS Cut Line= 4
     1907748.582      649715.271     1907693.894      650319.438
     1907723.567      650470.867     1907821.498      650936.626
#Sta/Elev= 30
       0  776.44   156.6  781.06   215.3  785.04   293.5  791.91     411  789.61
   430.5  785.78   469.6  774.69   489.2  768.07   625.9  709.35   645.2  701.88
   664.5  697.47   683.8   696.7   703.1  697.85   712.7  700.09   741.7  708.54
     761  712.64   780.4  714.62   790.1  714.87   828.9  714.28   838.6  715.09
   848.4  717.08   916.4  738.35   974.6  761.47  1023.2  779.31  1042.6  784.68
  1081.5  792.57  1120.3   803.6  1207.8  829.71  1227.2  837.04  1236.9   841.7
#Mann= 3 , 0 , 0
       0      .1       0   645.2    .045       0   712.7     .07       0
Bank Sta=645.2,712.7
XS Rating Curve= 0 ,0
Exp/Cntr=0.3,0.1

Type RM Length L Ch R = 1 ,37859.1 ,411.2,413.2,415.3
XS GIS Cut Line= 4
     1907459.519      649697.042      1907335.29      650293.677
     1907303.269      650457.459     1907217.332      650881.938
#Sta/Elev= 30
       0  834.84    98.3  827.67   176.9  825.38   216.2  821.32   255.6  813.18
   294.9  802.51   363.7  778.46   481.6  732.19   530.8  716.54   550.4  712.56
   579.9  708.85   697.8  700.29   717.4  696.84   727.2   696.7   746.9     697
   756.7  699.22   766.5  704.87   776.3  711.02   785.9  714.27   834.1  721.02
   853.3   727.5   891.8   746.4   968.8  786.44   978.4  790.53  1026.5  807.56
  1122.8  844.73    1142  855.16  1151.7  861.86  1170.9  878.09  1209.4   914.2
#Mann= 3 , 0 , 0
       0      .1       0   697.8    .045       0   766.5     .08       0
Bank Sta=697.8,766.5
XS Rating Curve= 0 ,0
Exp/Cntr=0.3,0.1

Type RM Length L Ch R = 1 ,37445.8 ,401.1,401.7,402.3
XS GIS Cut Line= 4
     1907115.769      649629.334     1906963.018       650163.46
     1906923.061      650301.209     1906818.894      650824.646
#Sta/Elev= 30
       0  951.84      39  963.93    58.5     966    68.2  965.19      78  962.72
   126.7  942.99   165.7  923.88   214.4  897.35   341.1  820.59   487.3  737.02
   506.8  727.18   526.3  719.04   574.7  706.96   584.2   703.1   593.8  699.16
   603.4  697.13   612.9   696.7   641.6  696.97   651.2  698.41   660.7  701.54
   670.3  704.42   747.5  712.84   815.4   731.4   834.8  742.18   902.7   790.6
  1019.2  857.88  1038.6  867.28  1087.1  887.35  1135.6  903.26  1232.7  947.98
#Mann= 3 , 0 , 0
       0      .1       0   584.2    .045       0   660.7     .08       0
Bank Sta=584.2,660.7
XS Rating Curve= 0 ,0
Exp/Cntr=0.3,0.1