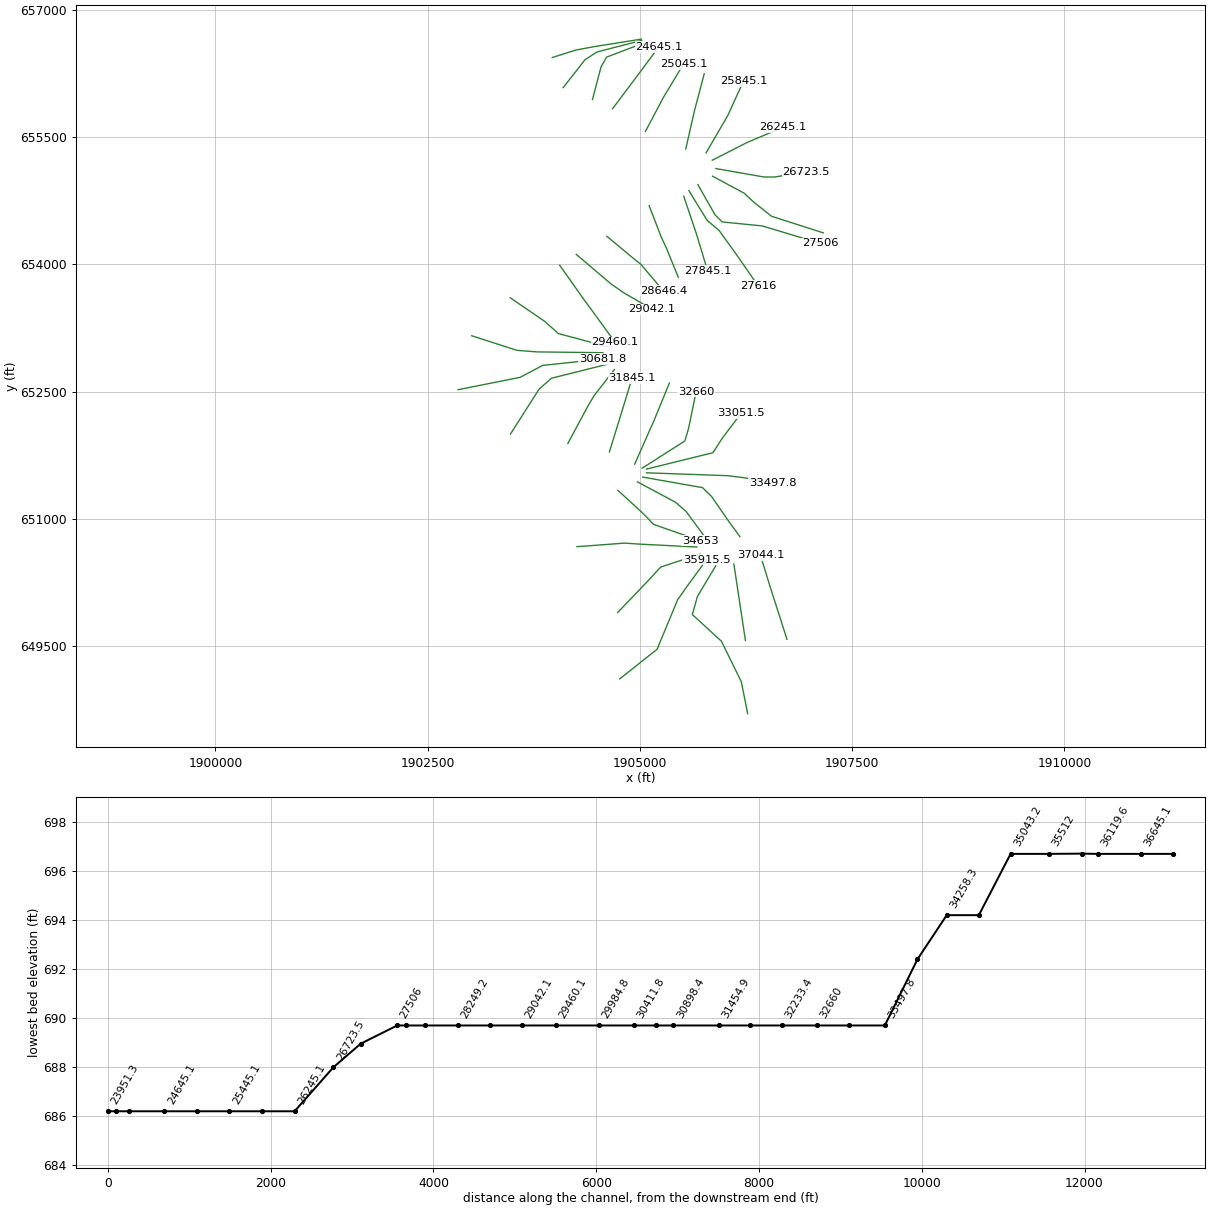
HEC-RAS study HenryFork.prj: HenryFork

--- HenryFork.g01 (geometry) --- (continued)

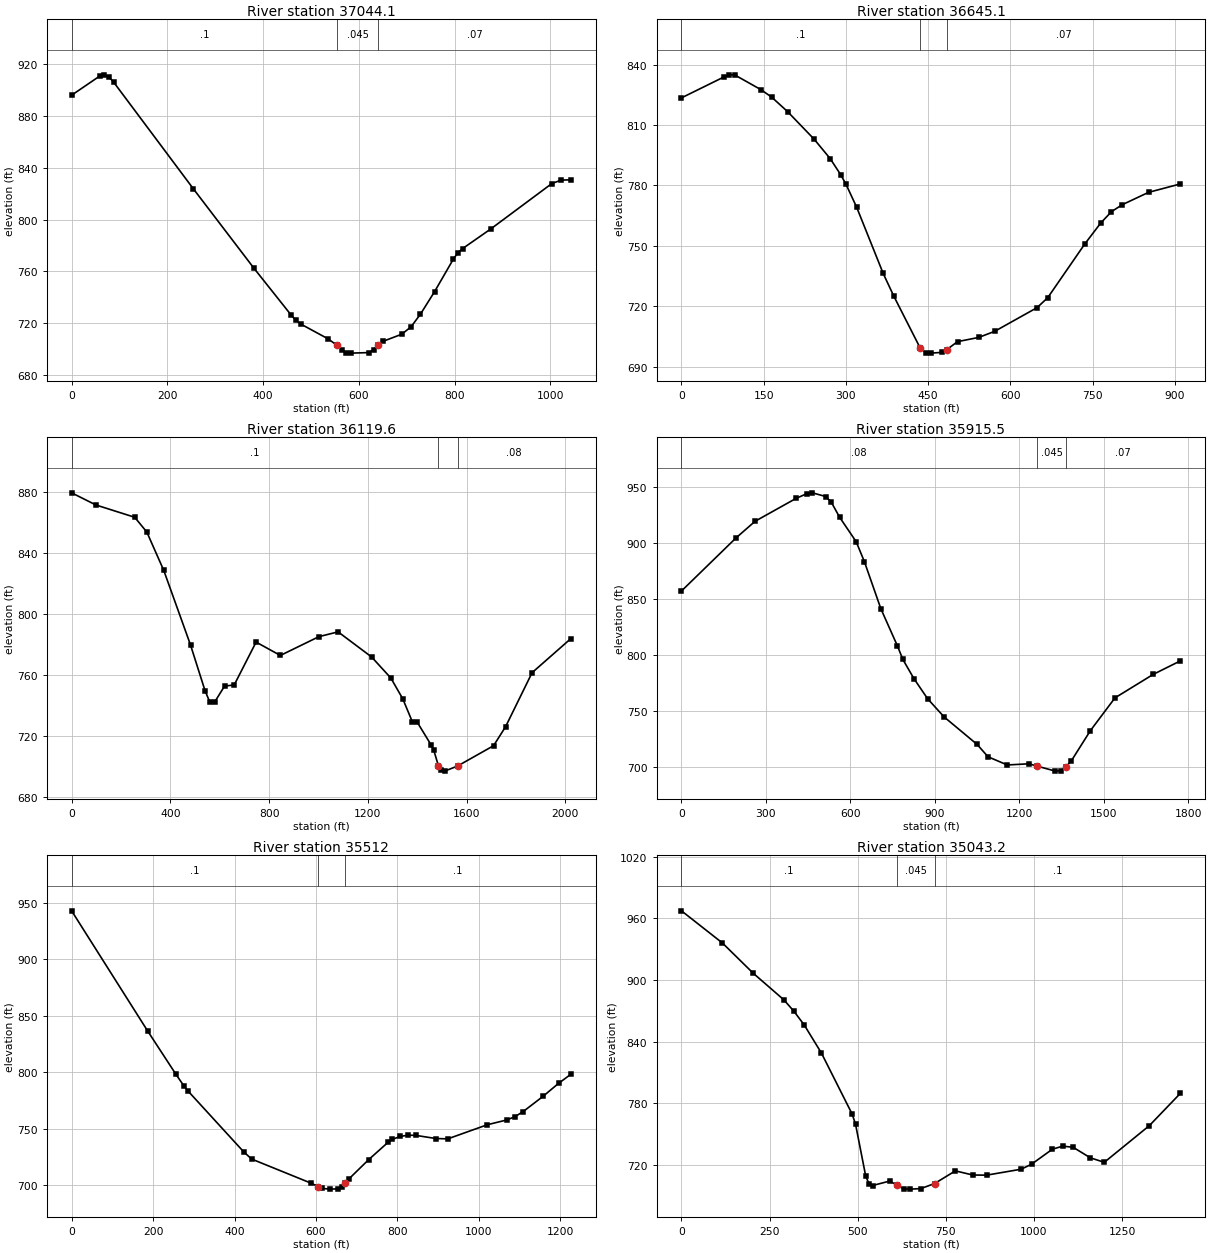
Type RM Length L Ch R = 1 ,37044.1 ,402.7,399,395.4
XS GIS Cut Line= 4
     1906732.089      649582.025     1906586.271      650037.624
     1906536.776      650191.834     1906418.747       650576.03
#Sta/Elev= 30
       0  896.12    58.6   910.9    68.3  911.88    78.1  910.19    87.9  906.15
   253.8  823.97   380.7  762.39   458.8     726   468.6  722.03   478.4  719.22
   535.5  707.77   554.6  702.65   564.1  699.29   573.6  697.17   583.2   696.7
   621.3  697.12   630.8   699.5   640.3  703.24   650.1  705.79   689.3  711.29
   708.9  717.01   728.6  726.86     758  744.21   797.2  769.34     807  774.42
   816.8  777.58   875.6  792.76    1003  827.83  1022.6  830.49  1042.2   830.7
#Mann= 3 , 0 , 0
       0      .1       0   554.6    .045       0   640.3     .07       0
Bank Sta=554.6,640.3
XS Rating Curve= 0 ,0
Exp/Cntr=0.3,0.1

Type RM Length L Ch R = 1 ,36645.1 ,535,525.5,515.9
XS GIS Cut Line= 3
     1906242.803      649568.969      1906174.74      650018.849
     1906106.676      650468.729
#Sta/Elev= 30
       0  823.54    77.4  833.92    87.1  834.98    96.8  834.99   145.2  827.58
   164.6  823.88   193.6  816.69     242  802.99   271.1   793.4   290.4  785.36
   300.1  780.59   319.5   769.2   367.9  736.28   387.2  725.04   435.6  699.11
   445.3  696.94     455   696.7   474.4  697.06     484  698.46   503.4  702.41
   542.1   704.5   571.2  707.53   648.6  719.32     668  724.27   735.7  751.01
   764.8  761.42   784.2  766.99   803.5  770.41   851.9   776.6     910  780.79
#Mann= 3 , 0 , 0
       0      .1       0   435.6    .045       0     484     .07       0
Bank Sta=435.6,484
XS Rating Curve= 0 ,0
Exp/Cntr=0.3,0.1

Type RM Length L Ch R = 1 ,36119.6 ,211.9,204.1,196.3
XS GIS Cut Line= 6
     1906269.384      648706.374     1906194.528       649082.19
     1905960.453      649559.218     1905617.505      649874.126
     1905677.401      650087.667     1905892.809      650447.669
#Sta/Elev= 30
       0  879.51    98.3  871.54   255.5  863.46   304.6  853.77   373.4   828.5
   481.6  779.61   540.6  749.47   560.3   741.9     580  742.22   619.4  752.53
   658.7  753.32   747.3  781.45   845.7  772.69  1001.9  785.04  1079.5  788.18
  1215.3  771.68  1292.9  757.92  1341.4  744.25  1380.2  729.14  1399.4  729.02
  1457.3  713.65  1466.9  710.56  1486.2  700.02  1495.9  697.12  1511.2   696.7
  1563.4  700.04  1709.3  713.39    1758  725.87  1865.4  761.38  2021.5  783.62
#Mann= 3 , 0 , 0
       0      .1       0  1486.2    .045       0  1563.4     .08       0
Bank Sta=1486.2,1563.4
XS Rating Curve= 0 ,0
Exp/Cntr=0.3,0.1

Type RM Length L Ch R = 1 ,35915.5 ,406.5,403.5,400.3
XS GIS Cut Line= 5
      1904762.44      649116.096     1905202.414      649465.173
      1905445.63      650051.209     1905560.214      650212.667
     1905783.157      650517.627
#Sta/Elev= 30
       0  857.34   193.7  904.69   261.4  919.54   406.7  939.92   445.4  944.21
   464.8  944.92   513.2  941.56   532.6  936.31   561.6  923.14   620.2  901.41
   649.5  883.58   708.1  841.51   766.6  808.54   786.2  796.29   825.2  779.32
     874   761.3   932.6  745.05  1049.7  720.54  1088.8  709.47  1157.1   702.2
  1233.8  703.25  1262.1  701.23  1328.1  696.71    1347  697.16  1365.8  700.76
  1384.7  706.01  1452.2  732.88  1539.4  762.06    1675  782.98  1771.9  795.08
#Mann= 3 , 0 , 0
       0     .08       0  1262.1    .045       0  1365.8     .07       0
Bank Sta=1262.1,1365.8
XS Rating Curve= 0 ,0
Exp/Cntr=0.3,0.1

Type RM Length L Ch R = 1 ,35512   ,489.9,468.9,448.1
XS GIS Cut Line= 4
     1904737.297      649897.563     1905104.485      650280.376
      1905245.11      650434.021     1905707.581       650585.19
#Sta/Elev= 30
       0  943.05   186.6  836.74   255.4  798.74     275  788.43   284.9  783.91
   422.4  729.76     442  723.33   587.2  702.08   606.2  698.81   615.6  697.32
   634.6   696.7   653.5  696.93     663  698.61   672.5  702.08   681.9  706.08
   729.3  722.77   777.6  738.33   787.4  740.73   806.8  743.32   826.3  744.49
   845.8  744.24   894.4   741.5   923.6  741.19  1020.9  753.72  1069.6  758.02
    1089  760.94  1108.5  765.28  1157.2  778.72  1196.1  790.45  1225.3  798.22
#Mann= 3 , 0 , 0
       0      .1       0   606.2    .045       0   672.5      .1       0
Bank Sta=606.2,672.5
XS Rating Curve= 0 ,0
Exp/Cntr=0.3,0.1

Type RM Length L Ch R = 1 ,35043.2 ,406,390.2,374.3
XS GIS Cut Line= 4
      1904258.13      650673.605     1904818.026      650715.271
     1905013.619      650702.629     1905670.807      650669.695
#Sta/Elev= 30
       0  967.21   116.2  935.94   203.3  906.63   290.4  880.72   319.4  869.44
   348.5  856.13   396.9  829.04     484  769.76   493.7  759.97   522.7   709.3
   532.4  701.63   542.1   700.2   590.8  704.55   610.4   700.7     630  696.95
   649.2   696.7     679  697.21   718.2  702.17   777.1  714.46   826.2  710.42
   865.5  710.28   963.7  716.06   993.2  720.95  1052.1  735.48  1081.5  738.49
    1111  737.37  1160.1   727.1  1199.4  722.76  1327.1  758.37  1415.5  789.89
#Mann= 3 , 0 , 0
       0      .1       0   610.4    .045       0   718.2      .1       0
Bank Sta=610.4,718.2
XS Rating Curve= 0 ,0
Exp/Cntr=0.3,0.1

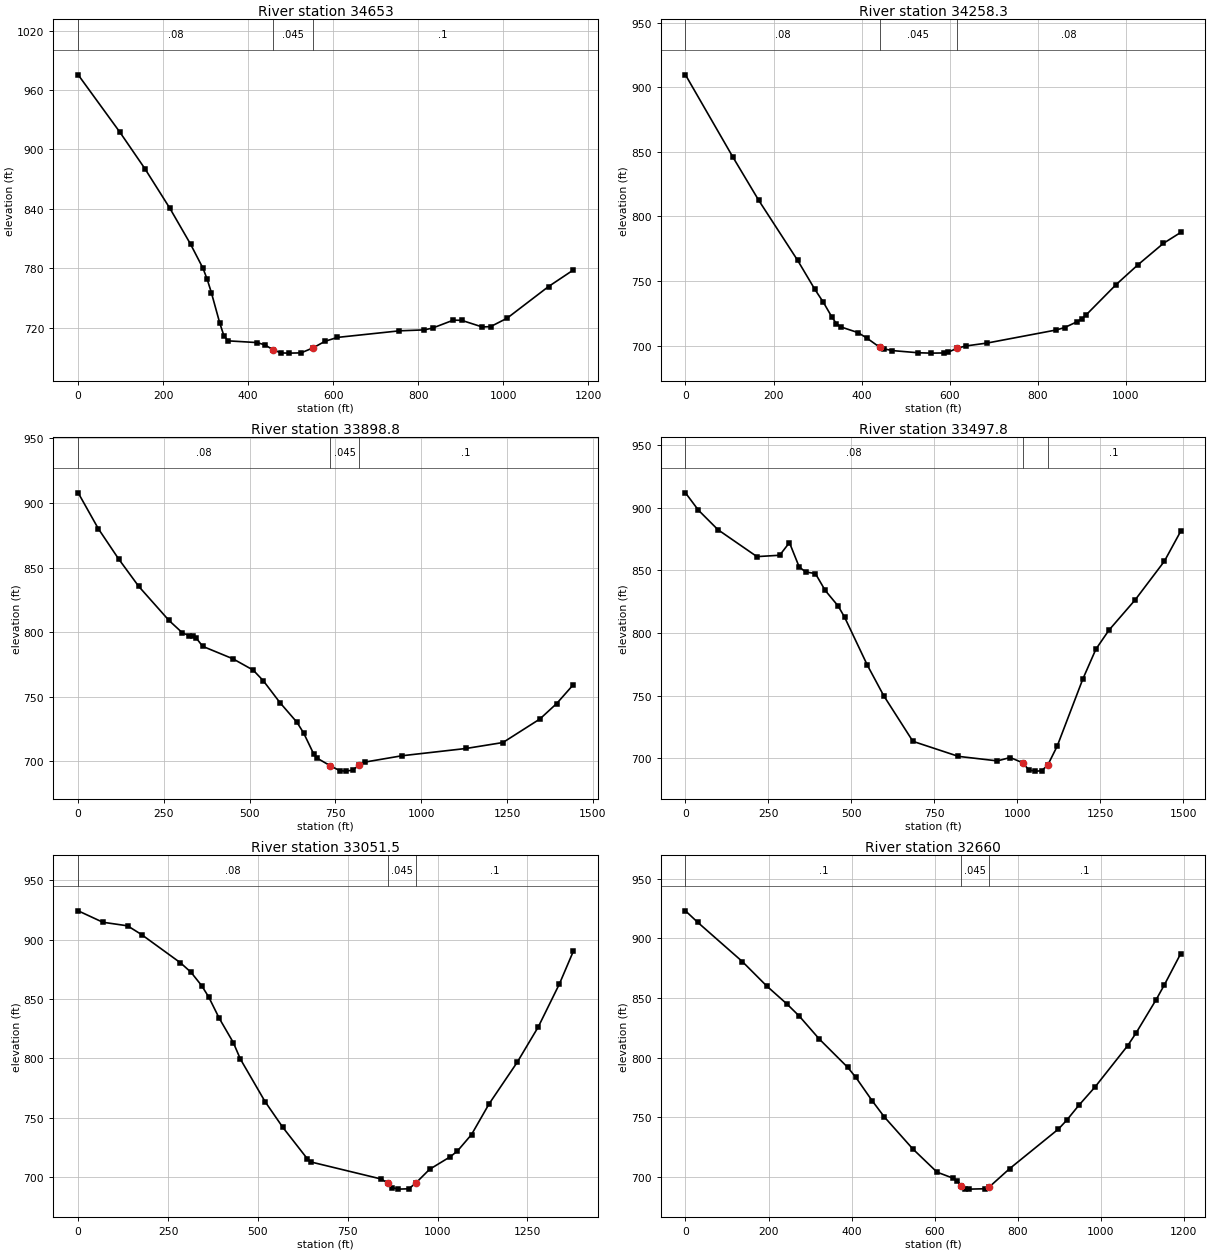
Type RM Length L Ch R = 1 ,34653   ,392.4,394.7,396.8
XS GIS Cut Line= 4
     1904739.901      651337.667     1905050.181      651053.069
     1905159.172      650936.626     1905710.889      650743.829
#Sta/Elev= 30
       0  975.41    97.9  917.58   156.7  880.75   215.4  840.77   264.4  804.29
   293.7  779.89   303.5  768.81   313.3  755.45   332.9  724.84   342.7  711.95
   352.5  706.61     421  704.86   439.8   702.4   458.6  697.55   477.3   694.4
   496.1   694.2   524.2  694.45   552.4  699.45   580.5  706.12   609.8  710.08
   755.9  716.74   814.3  717.69   833.8  719.53   882.5  727.51     902  727.36
   950.7  720.63   970.2  720.97  1009.1   729.5  1106.5  761.47    1165  778.23
#Mann= 3 , 0 , 0
       0     .08       0   458.6    .045       0   552.4      .1       0
Bank Sta=458.6,552.4
XS Rating Curve= 0 ,0
Exp/Cntr=0.3,0.1

Type RM Length L Ch R = 1 ,34258.3 ,360.7,359.5,358.3
XS GIS Cut Line= 4
     1904970.501      651436.927     1905419.589      651197.042
     1905544.726      651088.114     1905810.214      650725.688
#Sta/Elev= 30
       0  909.69   107.7     846   166.4  812.49   254.6  766.09   293.7  743.62
   313.3  733.44   332.9  721.89   342.7  717.04   352.5  714.53   391.6   710.1
   411.2  706.01   440.6  698.86   450.4   697.5     470  696.16   528.7  694.48
   557.9   694.2   587.2  694.34     597  695.03   616.5  697.93     636  699.72
   684.8     702   841.1  712.08   860.6  713.96   889.9  718.62   899.7   720.8
   909.4  723.69   977.8  747.28  1026.6  762.39  1085.2  779.22  1124.3  787.62
#Mann= 3 , 0 , 0
       0     .08       0   440.6    .045       0   616.5     .08       0
Bank Sta=440.6,616.5
XS Rating Curve= 0 ,0
Exp/Cntr=0.3,0.1

Type RM Length L Ch R = 1 ,33898.8 ,386.3,401,415.6
XS GIS Cut Line= 5
     1905032.145      651493.466     1905737.297      651368.917
     1905844.068      651264.751     1906050.443      650965.863
      1906177.37      650792.311
#Sta/Elev= 30
       0  907.82    58.8  880.02   117.7  856.73   176.6  835.38   264.8     809
   304.1  799.37   323.7  797.28   333.5  797.38   343.3  795.69   362.9     789
   451.2  779.34   510.1   770.6   539.5  762.41   588.6  745.29   637.6  730.25
   657.2  721.92   686.6  705.65   696.4  702.46   734.7  696.57   762.7  692.71
   781.3   692.4     800  693.21   818.6   696.9   837.3  699.46   943.8   704.3
  1130.3  709.92  1238.2  714.54  1345.7  732.72  1394.6  744.65  1443.5  759.35
#Mann= 3 , 0 , 0
       0     .08       0   734.7    .045       0   818.6      .1       0
Bank Sta=734.7,818.6
XS Rating Curve= 0 ,0
Exp/Cntr=0.3,0.1

Type RM Length L Ch R = 1 ,33497.8 ,420.8,446.3,471.7
XS GIS Cut Line= 4
     1905077.629      651543.895     1906036.776      651509.542
     1906224.276      651486.105     1906562.818      651426.209
#Sta/Elev= 30
       0  911.72    39.2  897.83    97.9  882.31   215.5  860.83     284  861.92
   313.4  872.01   342.8  852.57   362.4  848.61   391.7  847.29   421.1  833.89
   460.3  821.39   479.9  812.36   548.4  774.13   597.4  749.95   685.5  713.47
   822.6  701.48   940.2  697.86   978.7  700.56  1016.4  696.36  1035.4  690.53
  1054.2   689.7  1073.1   689.9    1092  694.54  1120.4  709.63  1197.8  763.28
  1237.1  787.01  1276.4  802.17    1355   826.2  1443.4  857.13  1492.5  880.99
#Mann= 3 , 0 , 0
       0     .08       0  1016.4    .045       0    1092      .1       0
Bank Sta=1016.4,1092
XS Rating Curve= 0 ,0
Exp/Cntr=0.3,0.1

Type RM Length L Ch R = 1 ,33051.5 ,385.1,391.5,397.9
XS GIS Cut Line= 4
     1905078.443      651587.667     1905859.693      651780.376
     1905969.406      651950.099     1906193.026      652246.521
#Sta/Elev= 30
       0   924.3    68.7  914.67   137.4  911.67   176.6  904.24   284.6  880.49
     314  872.52   343.5  861.28   363.1  851.76   392.5  833.76   431.8   813.2
   451.4  799.33   520.1  763.47   569.2   741.9   637.8  715.25   647.7  712.59
   843.2  698.23   862.4  694.69     872  691.06   891.3   689.7   920.2  689.99
   939.4  694.77   977.9  706.39  1036.1  717.11  1055.6  721.89  1094.7  735.72
  1143.6   761.6  1221.7  796.59  1280.4  826.44    1339  862.52  1378.1  890.28
#Mann= 3 , 0 , 0
       0     .08       0   862.4    .045       0   939.4      .1       0
Bank Sta=862.4,939.4
XS Rating Curve= 0 ,0
Exp/Cntr=0.3,0.1

Type RM Length L Ch R = 1 ,32660   ,429.6,426.7,423.7
XS GIS Cut Line= 4
      1905026.36      651598.084     1905528.964      651918.396
     1905573.235      652066.834     1905661.776      652499.126
#Sta/Elev= 30
       0  923.03    29.3  913.45   136.8  880.54   195.4  860.08   244.3  844.92
   273.6  834.92   322.4  815.46   390.8  791.73   410.4  783.31   449.4  763.84
   478.8  750.23   547.1   723.5   605.7  703.94   644.4  698.84   654.1  696.64
   663.8   692.7   673.4  690.17   683.1   689.7   721.8  690.01   731.5  691.54
   780.3  706.82     898  740.07   917.6  747.37     947  759.95   986.2  775.38
  1064.7     810  1084.3  820.29  1133.3  848.62  1152.9   860.9  1192.2  887.04
#Mann= 3 , 0 , 0
       0      .1       0   663.8    .045       0   731.5      .1       0
Bank Sta=663.8,731.5
XS Rating Curve= 0 ,0
Exp/Cntr=0.3,0.1

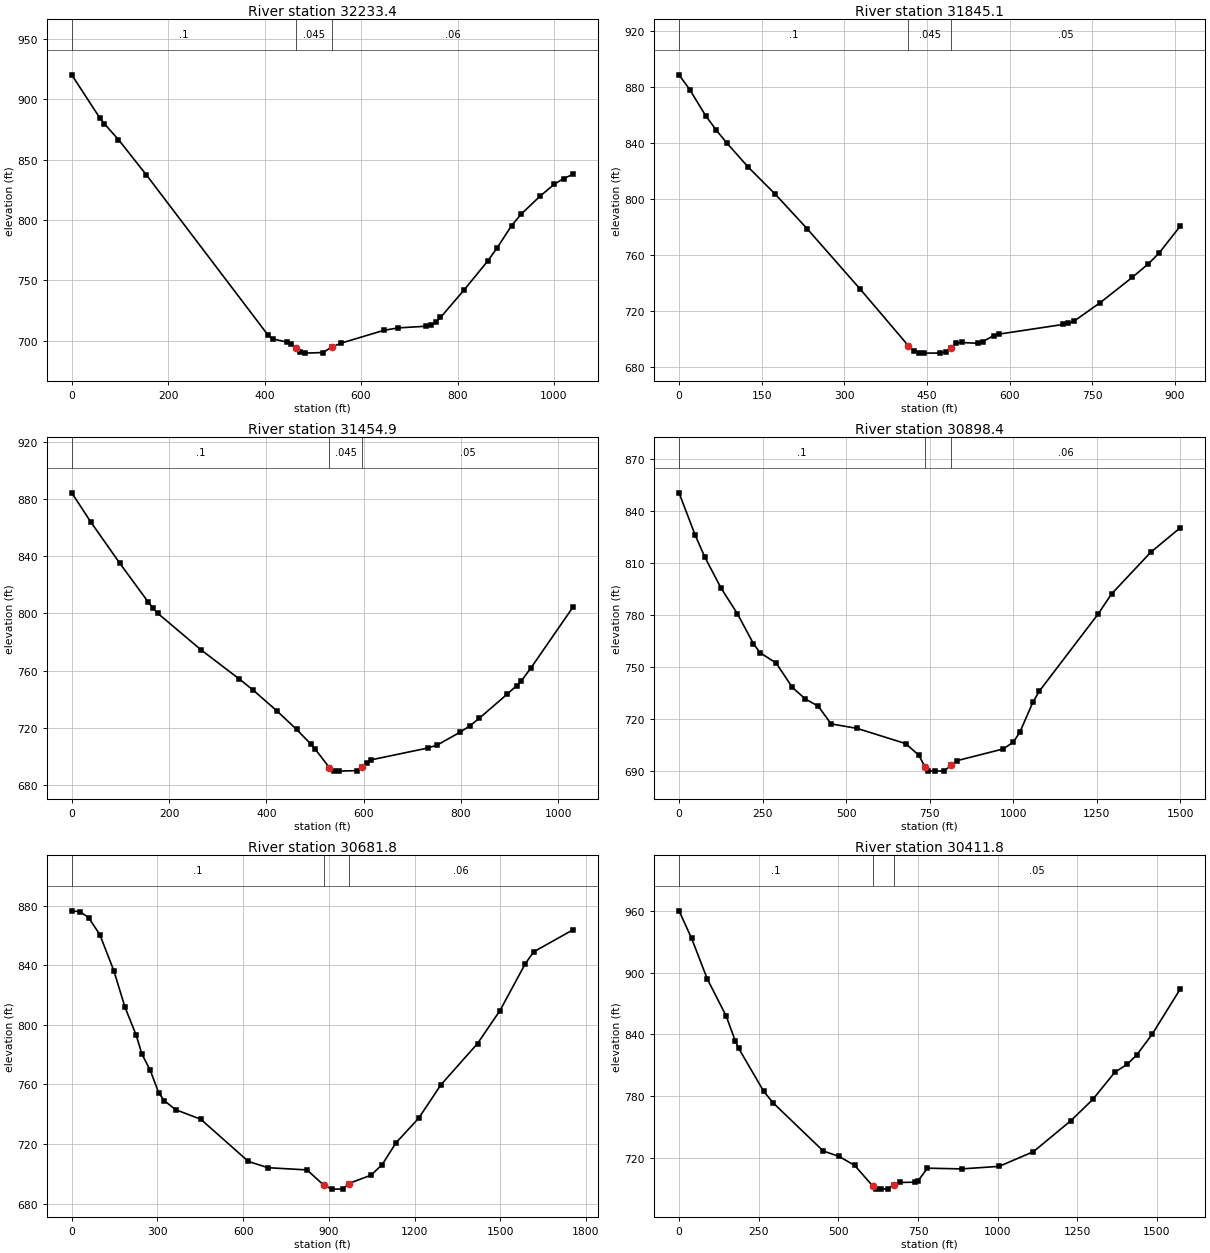
Type RM Length L Ch R = 1 ,32233.4 ,385.5,388.3,391
XS GIS Cut Line= 4
     1904937.818      651644.959     1905118.555      652052.251
      1905164.38      652155.376     1905346.672      652600.688
#Sta/Elev= 30
       0   920.4    58.1  884.75    67.8  879.78    96.9  866.69     155  837.34
   406.8  704.77   416.5  701.53   445.6  698.89     455  697.29   464.4  693.65
   473.8  690.69   483.2   689.7   520.8  690.19   539.6   694.8   558.4  697.96
   646.8  708.54   676.3   710.6   735.2     712     745  712.77   754.8  715.22
   764.7  719.25   813.8   742.1   862.9   766.2   882.5  777.15     912  795.32
   931.6  804.74   970.9  819.73  1000.3  829.55    1020  834.42  1039.6  837.91
#Mann= 3 , 0 , 0
       0      .1       0   464.4    .045       0   539.6     .06       0
Bank Sta=464.4,539.6
XS Rating Curve= 0 ,0
Exp/Cntr=0.3,0.1

Type RM Length L Ch R = 1 ,31845.1 ,395.4,390.2,385.1
XS GIS Cut Line= 3
     1904640.903      651790.508     1904774.698      652225.391
     1904908.494      652660.275
#Sta/Elev= 30
       0  888.54    19.4  877.99    48.4  859.29    67.8  848.92    87.1  839.66
   125.8   822.5   174.3   803.4   232.3  778.68   329.2  735.28   416.3  694.95
     426  691.44   435.6  689.93   445.3   689.7   474.4  689.78     484  690.68
   493.7  693.61   503.4  696.83   513.1   697.3   542.1  696.73   551.8     698
   571.2  702.27   580.8  703.28     697  710.18   706.7  710.92   716.4  712.38
   764.8  725.84   822.9  743.88   851.9  753.51   871.3  761.13     910  780.54
#Mann= 3 , 0 , 0
       0      .1       0   416.3    .045       0   493.7     .05       0
Bank Sta=416.3,493.7
XS Rating Curve= 0 ,0
Exp/Cntr=0.3,0.1

Type RM Length L Ch R = 1 ,31454.9 ,564.3,556.5,548.7
XS GIS Cut Line= 4
      1904151.36      651889.751     1904379.103      652314.411
     1904456.047      652447.042     1904698.488       652759.46
#Sta/Elev= 30
       0  884.17    39.3  863.74    98.3   835.2   157.4  807.78   167.2  803.59
     177  799.95   265.5  774.55   344.2  754.16   373.7   746.1   422.9  731.46
   462.2  718.86   491.5  708.66     501  704.88   529.8  692.11   539.4  690.09
     549   689.7   587.3  690.06   596.9  692.25   606.5  695.55     616  697.61
   731.7  705.82     751  707.84   799.2  717.02   818.5  721.34   837.8  726.59
   895.6  743.58   914.9  749.48   924.6  752.86   943.9  761.69  1030.7  804.36
#Mann= 3 , 0 , 0
       0      .1       0   529.8    .045       0   596.9     .05       0
Bank Sta=529.8,596.9
XS Rating Curve= 0 ,0
Exp/Cntr=0.3,0.1

Type RM Length L Ch R = 1 ,30898.4 ,221.5,216.5,211.6
XS GIS Cut Line= 4
     1903474.276      651999.126     1903812.818      652530.376
     1903958.651       652657.98     1904615.769      652822.126
#Sta/Elev= 30
       0  850.62    48.5  826.07    77.5  813.34     126  795.47   174.4  780.82
   222.9  763.34   242.3  758.21   290.8   752.2   339.2  738.09     378  731.46
   416.7  727.23   455.5     717     533  714.42   678.4  705.62   717.2  699.05
   736.5  692.29   746.2   689.9   765.6   689.7   794.7  689.84     814  693.11
   833.5  695.82     971  702.54  1000.4   706.4    1020  712.05  1059.3  729.47
    1079  736.02  1255.6  780.77  1294.9  792.14  1412.7  816.32    1501  830.45
#Mann= 3 , 0 , 0
       0      .1       0   736.5    .045       0     814     .06       0
Bank Sta=736.5,814
XS Rating Curve= 0 ,0
Exp/Cntr=0.3,0.1

Type RM Length L Ch R = 1 ,30681.8 ,282.1,270,258
XS GIS Cut Line= 4
     1902857.089      652522.563      1903588.86      652668.396
     1903854.485      652809.021     1904558.458      652883.786
#Sta/Elev= 30
       0  876.43    29.4  875.79    58.9  871.94    98.2  860.49   147.3  836.28
   186.5   811.7   225.8  792.91   245.4  780.44   274.9  769.35   304.4  754.34
     324  749.05   363.3  743.03   451.6  736.58   618.5  708.24   687.2  704.07
   823.7  702.59   881.9  692.37     911   689.7   949.8  689.76   969.2  693.44
  1046.7     699    1086     706  1135.2  720.84  1213.9  737.18  1292.5  759.78
  1420.3   787.4    1499  809.55  1587.5  840.97    1617  848.95  1754.6  863.71
#Mann= 3 , 0 , 0
       0      .1       0   881.9    .045       0   969.2     .06       0
Bank Sta=881.9,969.2
XS Rating Curve= 0 ,0
Exp/Cntr=0.3,0.1

Type RM Length L Ch R = 1 ,30411.8 ,442.6,427,411.4
XS GIS Cut Line= 4
     1903018.547       653157.98     1903552.401      652986.105
      1903789.38      652967.876     1904564.116      652958.491
#Sta/Elev= 30
       0  960.11    39.4  933.41    88.6  893.92   147.6  858.13   177.1  833.23
     187  826.54   265.7  784.74   295.2  773.52   452.6  726.74   501.8  721.53
     551  712.79   608.4  692.56   617.9  690.18   635.2   689.7   655.9  689.99
   674.9  694.08   693.9   696.2   741.5  696.43     751  698.04   779.5  710.07
   886.8  709.35  1004.5  711.81  1112.4  726.13    1230  756.27  1298.7  776.93
  1367.4  803.19  1406.6  811.07    1436  819.89    1485  840.26  1573.3  884.34
#Mann= 3 , 0 , 0
       0      .1       0   608.4    .045       0   674.9     .05       0
Bank Sta=608.4,674.9
XS Rating Curve= 0 ,0
Exp/Cntr=0.3,0.1

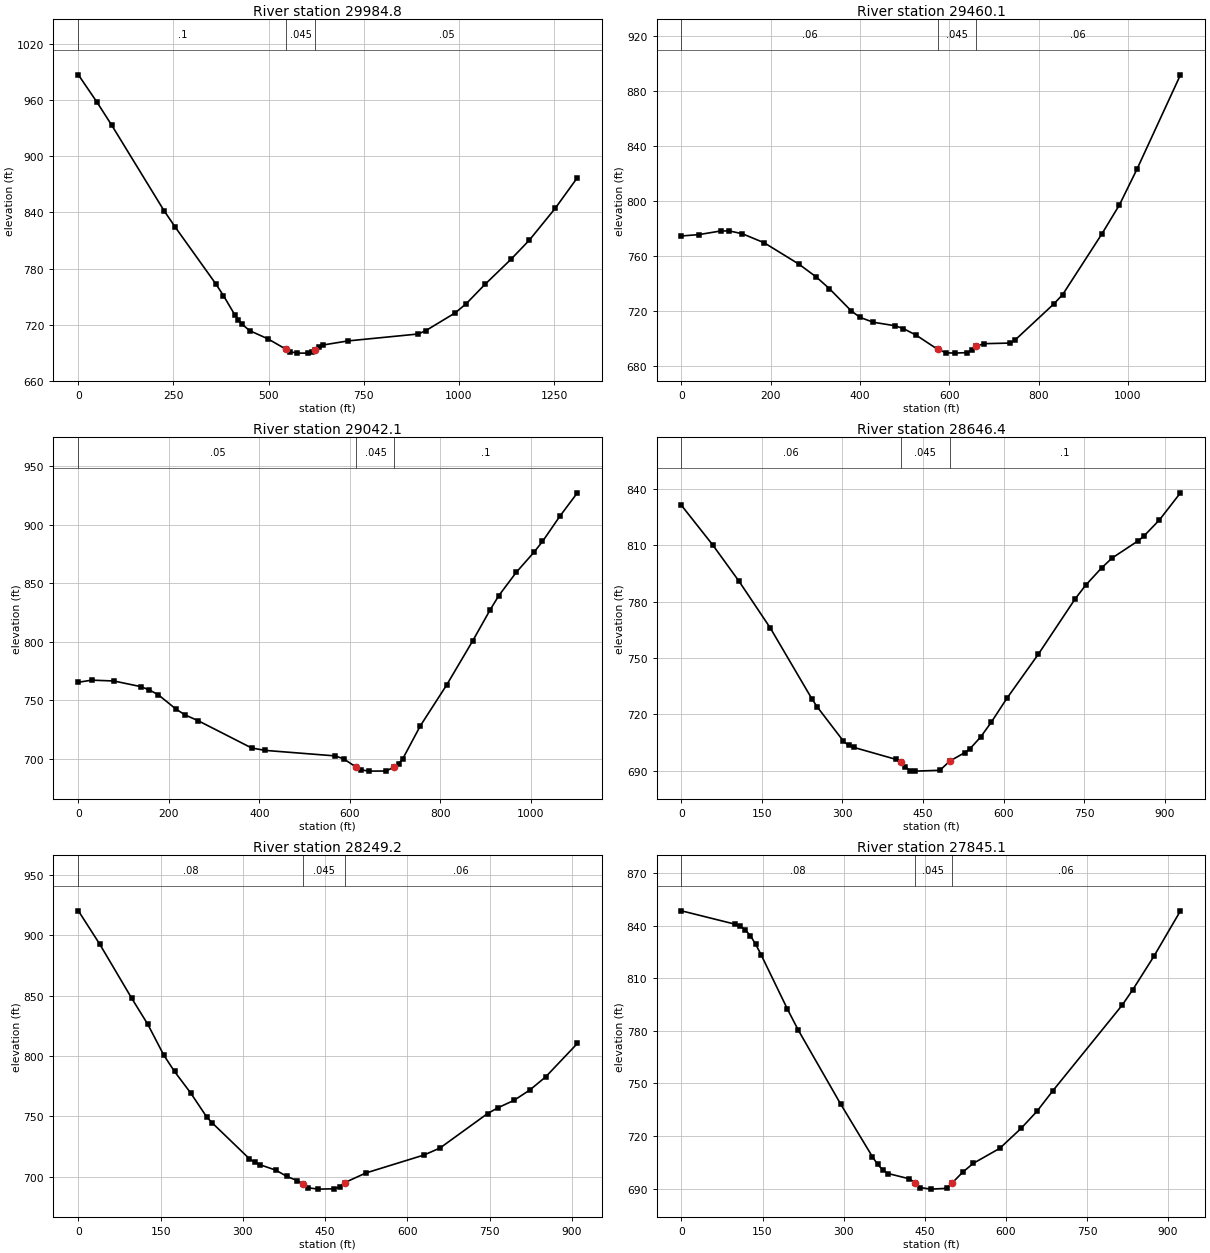
Type RM Length L Ch R = 1 ,29984.8 ,529,524.6,520.2
XS GIS Cut Line= 4
     1903471.672      653605.896     1903875.318      653329.855
      1904039.38      653184.021     1904621.987      653028.441
#Sta/Elev= 30
       0  987.06    48.9  957.86      88     933   224.9  842.08   254.3  824.49
   361.9  763.31   381.4   751.1   410.8  730.86   420.6  725.33   430.3  720.58
   449.9  713.79   498.6  704.87   546.3   693.7   555.8   691.3   574.9   689.7
   603.4  689.71   613.1  690.53   622.6  693.35   632.2  696.78   641.7  698.31
   708.5  702.74   893.3  710.15   912.8  713.66   990.6  732.76  1019.8  742.68
  1068.4  763.04  1136.5  789.75  1185.1  810.34  1253.2  844.38  1311.5  877.18
#Mann= 3 , 0 , 0
       0      .1       0   546.3    .045       0   622.6     .05       0
Bank Sta=546.3,622.6
XS Rating Curve= 0 ,0
Exp/Cntr=0.3,0.1

Type RM Length L Ch R = 1 ,29460.1 ,411,418.1,425.2
XS GIS Cut Line= 4
     1904055.005      653988.709     1904336.255      653590.271
     1904466.464      653413.188      1904707.52      653080.906
#Sta/Elev= 30
       0  774.89      39  775.88    87.8  778.52   107.3  778.56   136.6  776.47
   185.3  769.95   263.4  754.35   302.4  744.97   331.6  736.53   380.4  720.41
   399.9  715.74   429.2  712.19     478  709.63   497.3  707.53   525.9  702.75
   573.7  692.52   592.8  689.96   611.9   689.7   640.6  690.09   650.2  691.67
   659.7  694.82   678.8  696.58   736.8  697.02   746.6  698.97   834.6  725.58
   854.1  732.28   942.1  776.47   981.2  797.45  1020.3  823.27    1118  892.06
#Mann= 3 , 0 , 0
       0     .06       0   573.7    .045       0   659.7     .06       0
Bank Sta=573.7,659.7
XS Rating Curve= 0 ,0
Exp/Cntr=0.3,0.1

Type RM Length L Ch R = 1 ,29042.1 ,397.1,395.6,394.2
XS GIS Cut Line= 4
     1904250.318      654116.313     1904662.081      653766.836
      1904807.61      653665.792      1905140.88      653471.677
#Sta/Elev= 30
       0  765.47    29.5  767.28    78.6  766.56   137.5  761.79   157.1  758.91
   176.8  754.76     216  742.52   235.7  737.66   265.1  732.62     383  709.44
   412.4   707.4     568  702.66   586.7   700.1   614.7   692.9     624   690.8
   642.6   689.7     680   689.8   698.6  693.32   707.9  696.08   717.2  700.38
   755.8  728.32   813.7  762.99   871.5  800.73   910.1  827.23   929.4  839.41
   967.9  859.26  1006.5  876.13  1025.8  885.51  1064.4  907.17  1102.9  927.01
#Mann= 3 , 0 , 0
       0     .05       0   614.7    .045       0   698.6      .1       0
Bank Sta=614.7,698.6
XS Rating Curve= 0 ,0
Exp/Cntr=0.3,0.1

Type RM Length L Ch R = 1 ,28646.4 ,407.5,397.2,386.7
XS GIS Cut Line= 4
     1904610.404      654330.086     1904916.985      654074.646
      1905010.18      654000.531      1905276.36      653686.626
#Sta/Elev= 30
       0  831.39    58.4  810.23   107.1  790.99   165.5  766.02   243.3   728.1
   253.1  723.88   301.7  705.71   311.4  703.39   321.2  702.35     399  696.02
   408.2  694.67   417.4  691.82   426.5  690.02   435.7   689.7   481.5  690.14
   499.8  695.02   527.9  699.59   537.7  701.68   557.3  707.83   576.9  715.63
   606.3  728.51   665.1  752.12   733.7  781.63   753.3  788.88   782.7  798.02
   802.3   803.3   851.3  812.57   861.1  814.87   890.5  823.61   929.7  838.07
#Mann= 3 , 0 , 0
       0     .06       0   408.2    .045       0   499.8      .1       0
Bank Sta=408.2,499.8
XS Rating Curve= 0 ,0
Exp/Cntr=0.3,0.1

Type RM Length L Ch R = 1 ,28249.2 ,406.8,404.2,400.9
XS GIS Cut Line= 4
     1905108.752      654689.439     1905252.922      654316.834
     1905310.238       654194.93      1905452.12      653846.706
#Sta/Elev= 30
       0  920.14      39  892.52    97.4  847.65   126.7  826.11   155.9  800.57
   175.4  787.11   204.6  769.48   233.9  749.58   243.6  744.77   311.8  714.91
   321.6  711.88   331.3   709.9   360.6  705.34     380  700.29   399.5  696.66
   409.2  693.83   418.8   690.8     438   689.7   466.9  689.98   476.5  691.69
   486.1  695.14   524.6   703.1   630.6  717.97   659.6  723.74   746.3  752.23
   765.6  757.14   794.6   763.2   823.5  771.79   852.4  782.66   910.2  810.31
#Mann= 3 , 0 , 0
       0     .08       0   409.2    .045       0   486.1     .06       0
Bank Sta=409.2,486.1
XS Rating Curve= 0 ,0
Exp/Cntr=0.3,0.1

Type RM Length L Ch R = 1 ,27845.1 ,217.3,229.1,241.9
XS GIS Cut Line= 3
      1905516.16      654802.437      1905666.29      654356.324
     1905797.174      653923.448
#Sta/Elev= 30
       0  848.39    98.1  840.85   107.9  839.72   117.7  837.62   127.5  834.22
   137.3   829.3   147.1  823.48   196.1   792.3   215.7  780.57   294.2  738.33
     353  708.26   362.8   703.8   372.6  700.57   382.4  698.58   421.7  695.56
   431.5  693.39   441.3  690.62   460.9   689.7   490.4  690.15   500.2  693.05
   519.8  699.26   539.5  704.36   588.7  712.96     628   724.3   657.5  734.08
     687  745.83   814.8  794.49   834.4  803.27   873.8  822.48   922.9  848.39
#Mann= 3 , 0 , 0
       0     .08       0   431.5    .045       0   500.2     .06       0
Bank Sta=431.5,500.2
XS Rating Curve= 0 ,0
Exp/Cntr=0.3,0.1

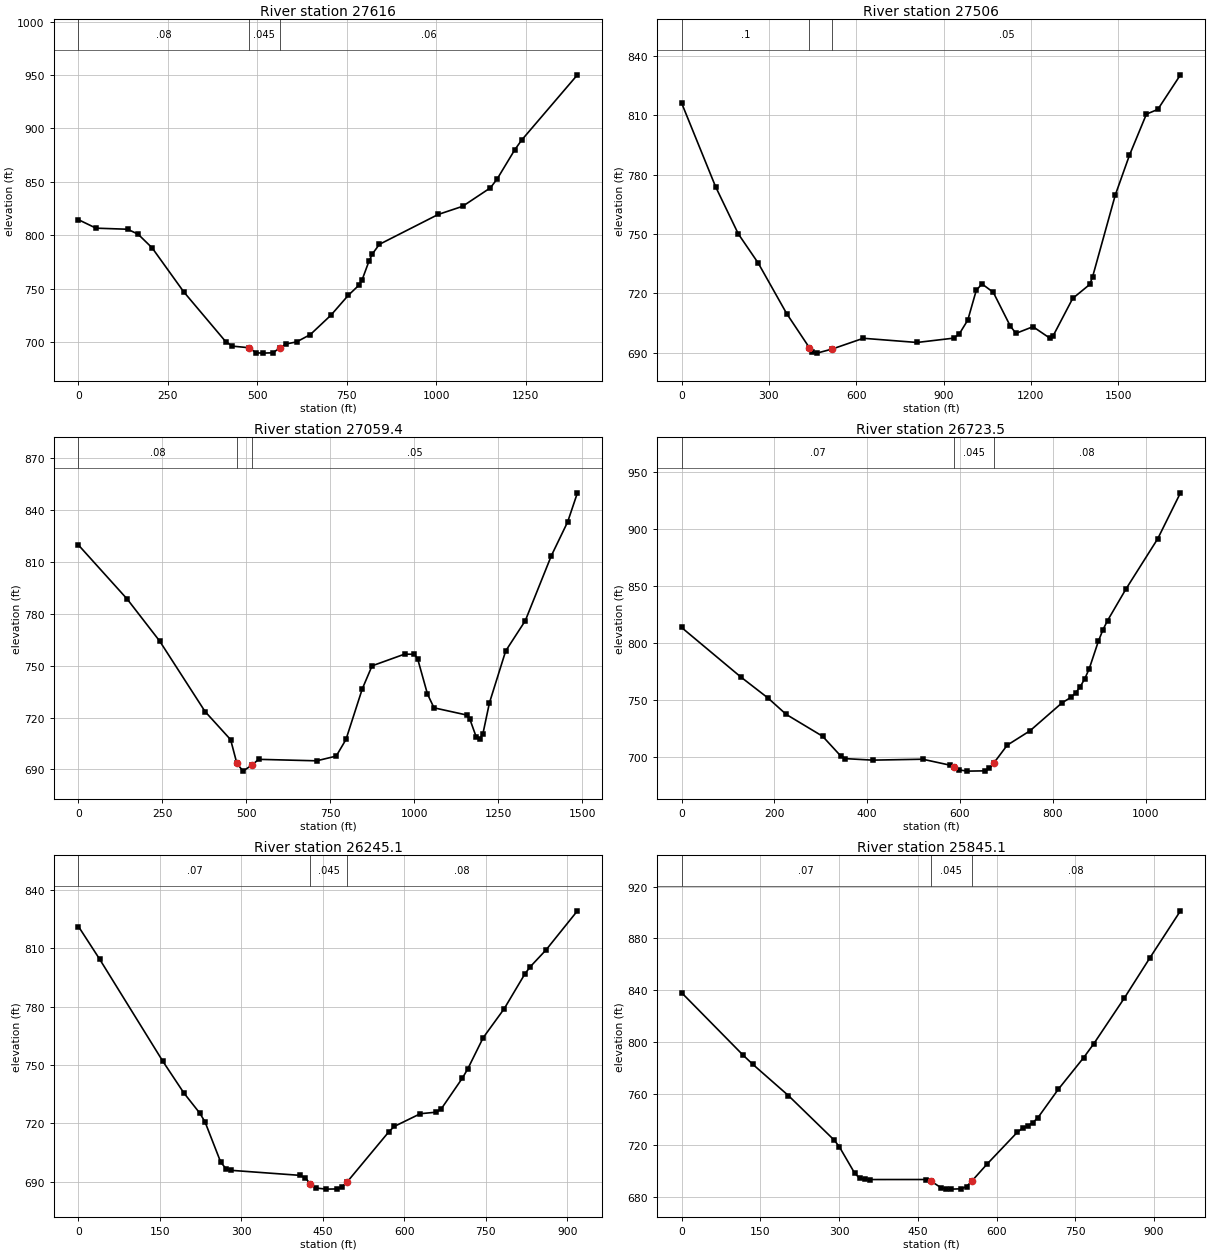
Type RM Length L Ch R = 1 ,27616   ,110.6,110,108.7
XS GIS Cut Line= 5
     1905576.707      654867.615     1905791.985      654516.921
     1905929.137      654402.337     1906127.059      654128.874
     1906393.082      653745.002
#Sta/Elev= 30
       0  814.57      49  806.65   137.2  805.65   166.6  801.02   205.8  788.24
   293.9  747.18   411.5  700.46   430.3  696.25   477.3  694.72   496.2  689.99
     515   689.7   543.2  690.01     562   694.3   580.8   698.3   609.5  700.18
   648.1  707.08     706  725.31   754.2   743.8   783.1     753   792.8  758.25
     812  775.72   821.7  782.59     841  791.48  1005.6  819.49  1073.7  827.09
  1151.6  844.42    1171  853.05  1219.7  880.08  1239.2  889.23  1394.8  950.17
#Mann= 3 , 0 , 0
       0     .08       0   477.3    .045       0     562     .06       0
Bank Sta=477.3,562
XS Rating Curve= 0 ,0
Exp/Cntr=0.3,0.1

Type RM Length L Ch R = 1 ,27506   ,446.3,446.6,447.2
XS GIS Cut Line= 5
      1905682.61      654938.796     1905884.867      654582.459
       1905968.2      654499.126     1906440.902      654451.932
     1907121.815      654247.172
#Sta/Elev= 30
       0  816.33   117.1  773.86   195.1     750   263.4  735.26     361  709.74
   439.2  692.43     449  690.12   465.3   689.7   517.8  691.79   624.5  697.21
   808.7  695.09   934.8  697.28   954.2  699.46   983.2  706.41  1012.4  721.49
  1031.9  724.72  1070.8  720.46  1129.3  703.37  1148.7   699.7  1207.2  703.07
  1265.6  697.22  1275.4  698.18  1343.6  717.38    1402  724.43  1411.7  728.21
  1489.6  769.57  1538.4  789.78  1596.8  810.61  1635.8  812.97  1713.7  830.48
#Mann= 3 , 0 , 0
       0      .1       0   439.2    .045       0   517.8     .05       0
Bank Sta=439.2,517.8
XS Rating Curve= 0 ,0
Exp/Cntr=0.3,0.1

Type RM Length L Ch R = 1 ,27059.4 ,318.9,335.9,352.4
XS GIS Cut Line= 5
     1905854.887      655038.141     1906229.485      654836.365
     1906337.611      654735.254     1906550.172      654565.824
     1907160.443      654370.002
#Sta/Elev= 30
       0  819.86     145   788.6   241.8  764.27   377.1  723.45   453.2  707.17
   471.8  693.44   490.2  688.96     518  692.65   536.5  695.79   709.4  694.93
   767.7  697.66   796.8  707.28   845.4   736.6   874.5  749.92   971.6  756.72
  1000.7  756.61  1010.4  753.93  1039.6  733.58    1059  725.62  1156.1  721.46
  1165.8  719.07  1185.2  708.51  1194.9  707.57  1204.6   710.5  1224.1  728.45
  1272.6  758.56  1330.9  776.04  1408.6  813.71  1457.1  833.24  1486.3  850.11
#Mann= 3 , 0 , 0
       0     .08       0   471.8    .045       0     518     .05       0
Bank Sta=471.8,518
XS Rating Curve= 0 ,0
Exp/Cntr=0.3,0.1

Type RM Length L Ch R = 1 ,26723.5 ,467.3,478.4,487.9
XS GIS Cut Line= 4
     1905895.251        655127.6     1906455.179      655029.074
     1906578.443      655027.337     1906956.915      655086.365
#Sta/Elev= 30
       0  813.76   127.4  770.51   186.2  752.02   225.4  737.69   303.9  718.52
   343.1   701.2   352.9  698.94   411.7  697.62   519.5  698.42     578  693.25
   587.5  691.45     597  689.13   615.9     688   653.9  688.25   663.4  690.44
   672.8  695.11   701.6  710.71   750.7  723.32   819.5  747.72   839.1  752.63
     849  756.47   858.8  761.88   868.6  768.78   878.4  777.77   898.1  801.86
   907.9   811.8   917.7  819.75     957  847.14  1025.8  891.38  1074.8  931.58
#Mann= 3 , 0 , 0
       0     .07       0   587.5    .045       0   672.8     .08       0
Bank Sta=587.5,672.8
XS Rating Curve= 0 ,0
Exp/Cntr=0.3,0.1

Type RM Length L Ch R = 1 ,26245.1 ,387,400,416.7
XS GIS Cut Line= 3
     1905852.408      655226.017     1906267.673      655437.157
     1906685.066      655613.419
#Sta/Elev= 30
       0  821.12    38.8  804.41   155.3   751.9   194.1  735.59   223.2   725.3
   232.9  720.82     262  700.01   271.8  696.66   281.5  695.85   407.6  693.28
   417.3  692.09     427  688.93   436.7  686.78   456.2   686.2   475.5   686.3
   485.1  687.29   494.8  689.89   571.9  715.77   581.5   718.4   629.7  724.96
   658.7  725.72   668.3  727.51   706.9   743.2   716.5  747.75   745.4  764.04
     784  778.87   822.5  796.94   832.2  800.51   861.1   809.1   918.9  829.18
#Mann= 3 , 0 , 0
       0     .07       0     427    .045       0   494.8     .08       0
Bank Sta=427,494.8
XS Rating Curve= 0 ,0
Exp/Cntr=0.3,0.1

Type RM Length L Ch R = 1 ,25845.1 ,393.1,400,403.9
XS GIS Cut Line= 3
      1905779.27      655312.799     1906032.734      655748.549
      1906218.62      656154.217
#Sta/Elev= 30
       0  838.05   116.3  790.12   135.7  782.66   203.6  758.48   290.8  724.08
   300.5  718.98   329.6  698.66   339.3  694.52     349  693.71   358.7  693.61
   465.3  693.63     475  692.44   494.4  687.24   504.1  686.24   513.8   686.2
   533.2  686.46   542.9  688.22   552.6  692.28   581.7  705.44   639.9   730.3
   649.6  733.28   659.3  734.95     669  737.57   678.7  741.36   717.5  763.28
     766  787.84   785.4  798.66   843.6  833.96   892.1  864.93   950.3  901.24
#Mann= 3 , 0 , 0
       0     .07       0     475    .045       0   552.6     .08       0
Bank Sta=475,552.6
XS Rating Curve= 0 ,0
Exp/Cntr=0.3,0.1

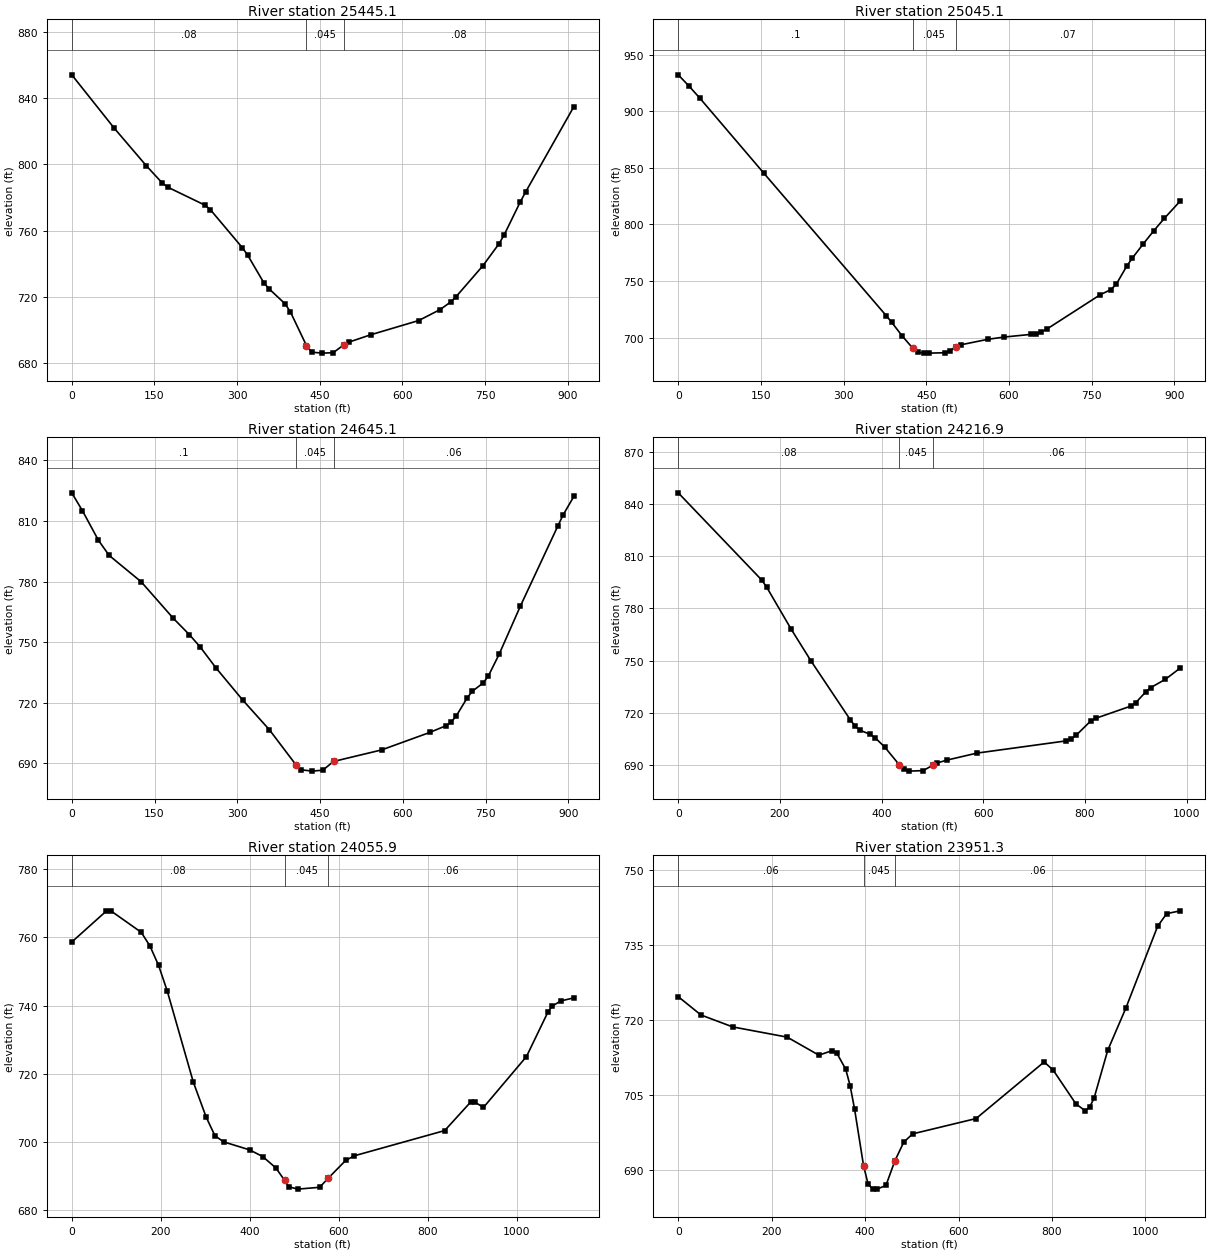
Type RM Length L Ch R = 1 ,25445.1 ,405.9,400,393.6
XS GIS Cut Line= 3
     1905540.272      655359.245     1905641.054      655802.748
     1905757.319      656243.756
#Sta/Elev= 30
       0  854.01    77.4  821.69   135.5  799.09   164.5  788.67   174.2  786.26
   241.9  775.38   251.6  772.63   309.7  749.69   319.3  745.17   348.4  728.65
     358  724.94   387.1  715.92   396.8  710.96   425.8  690.75   435.5  686.76
   454.8   686.2   474.2  686.46   493.6  691.16   503.3  692.89   542.1  697.24
   629.5  705.86   668.3  712.46   687.7   717.1   697.4  720.31   745.9   738.9
     775  752.08   784.7  757.63   813.8  777.46   823.6  783.48   910.9  834.82
#Mann= 3 , 0 , 0
       0     .08       0   425.8    .045       0   493.6     .08       0
Bank Sta=425.8,493.6
XS Rating Curve= 0 ,0
Exp/Cntr=0.3,0.1

Type RM Length L Ch R = 1 ,25045.1 ,403.6,400,397.8
XS GIS Cut Line= 3
     1905064.951      655565.039     1905277.405      655967.213
     1905512.961      656357.542
#Sta/Elev= 30
       0  932.15    19.4  922.27    38.7  911.82   154.8  845.49   377.4  719.23
   387.1  713.48   406.4  701.26   425.8  690.32   435.5  686.87   445.2  686.24
   454.8   686.2   483.9  686.55   493.6  688.38   503.3  691.83     513  693.59
   561.5   698.4   590.6  700.38   639.1  702.74   648.8  703.51   658.5  704.93
   668.2  707.32   765.2  737.72   784.6  742.33   794.3  746.89   813.7  763.22
   823.4  769.98   842.8  782.32   862.2  794.12   881.6  805.25   910.7  820.69
#Mann= 3 , 0 , 0
       0      .1       0   425.8    .045       0   503.3     .07       0
Bank Sta=425.8,503.3
XS Rating Curve= 0 ,0
Exp/Cntr=0.3,0.1

Type RM Length L Ch R = 1 ,24645.1 ,426.3,428.2,429.9
XS GIS Cut Line= 3
     1904676.917      655831.635     1904950.329      656195.334
     1905221.956      656560.359
#Sta/Elev= 30
       0  823.94    19.4  815.05    48.4  800.41    67.8  792.95   125.8  779.91
   183.9  761.87     213  753.79   232.3  747.81   261.4  737.28   309.8  721.38
   358.2  706.66   406.6  689.21   416.3  686.85   435.6   686.2     455  686.67
   474.4  690.98   561.5  696.69   648.6  705.32   677.7  708.62   687.4  710.36
     697  713.56   716.4  722.32   726.1  725.77   745.4  729.77   755.1  733.32
   774.5  743.99   813.2  767.94     881  807.53   890.6  813.03     910  822.15
#Mann= 3 , 0 , 0
       0      .1       0   406.6    .045       0   474.4     .06       0
Bank Sta=406.6,474.4
XS Rating Curve= 0 ,0
Exp/Cntr=0.3,0.1

Type RM Length L Ch R = 1 ,24216.9 ,171,161,151
XS GIS Cut Line= 4
      1904441.29      655942.268     1904541.985      656325.949
     1904607.957      656440.532     1905036.776      656603.726
#Sta/Elev= 30
       0  846.71   164.5  796.33   174.2  792.19   222.5  767.91   261.2  749.73
   338.6  715.77   348.3  712.01     358  709.72   377.3  707.45     387  705.52
   406.1  700.12   434.4  690.02   443.9  687.31   453.3   686.2   481.7  686.49
   500.6  689.55     510  690.97   528.9  692.58   587.5  696.59   763.2  703.64
     773  704.83   782.7  706.86     812  715.28   821.8  716.71   890.1  723.68
   899.9  725.63   919.4  731.79   929.1   734.3   958.4  739.17   987.7  745.69
#Mann= 3 , 0 , 0
       0     .08       0   434.4    .045       0   500.6     .06       0
Bank Sta=434.4,500.6
XS Rating Curve= 0 ,0
Exp/Cntr=0.3,0.1

Type RM Length L Ch R = 1 ,24055.9 ,113.3,104.6,95.7
XS GIS Cut Line= 4
     1904095.804      656081.157     1904354.485      656411.018
      1904495.11      656501.296     1905019.415      656636.712
#Sta/Elev= 30
       0  758.66      78  767.79    87.7  767.81     156  761.52   175.5  757.52
     195  751.82   214.5  744.28     273  717.59   302.2  707.22   321.7  701.84
   341.2  700.06   399.7   697.7     429  695.74   458.5  692.41   478.2  688.75
     488  686.88   507.7   686.2   556.8  686.74   576.5  689.46   615.3  694.62
   634.6  695.97   837.7  703.37   895.7  711.69   905.4  711.72   924.8  710.16
  1021.4  725.08  1069.8  738.18  1079.5   739.9  1098.8   741.4  1127.8  742.28
#Mann= 3 , 0 , 0
       0     .08       0   478.2    .045       0   576.5     .06       0
Bank Sta=478.2,576.5
XS Rating Curve= 0 ,0
Exp/Cntr=0.3,0.1

Type RM Length L Ch R = 1 ,23951.3 ,85.2,84.5,82.8
XS GIS Cut Line= 4
     1903967.332      656435.324      1904245.11      656523.865
     1904470.804      656565.532     1905017.679      656652.337
#Sta/Elev= 30
       0  724.68    48.6  721.02   116.6  718.63   233.2  716.59   301.1  712.98
   329.8   713.9   339.4   713.4   358.5  710.18     368  706.87   377.6  702.14
   396.7  690.89   406.3  687.26   415.9  686.24   425.4   686.2   444.6  686.93
   463.7  691.84   482.8   695.6   501.9  697.25   637.6  700.31   783.4  711.63
   802.8  709.97   851.4  703.23   870.8   701.9   880.5  702.56   890.2   704.4
   919.4  713.95   958.2  722.39  1026.2  738.74  1045.6  741.28  1074.8  741.84
#Mann= 3 , 0 , 0
       0     .06       0   396.7    .045       0   463.7     .06       0
Bank Sta=396.7,463.7
XS Rating Curve= 0 ,0
Exp/Cntr=0.3,0.1