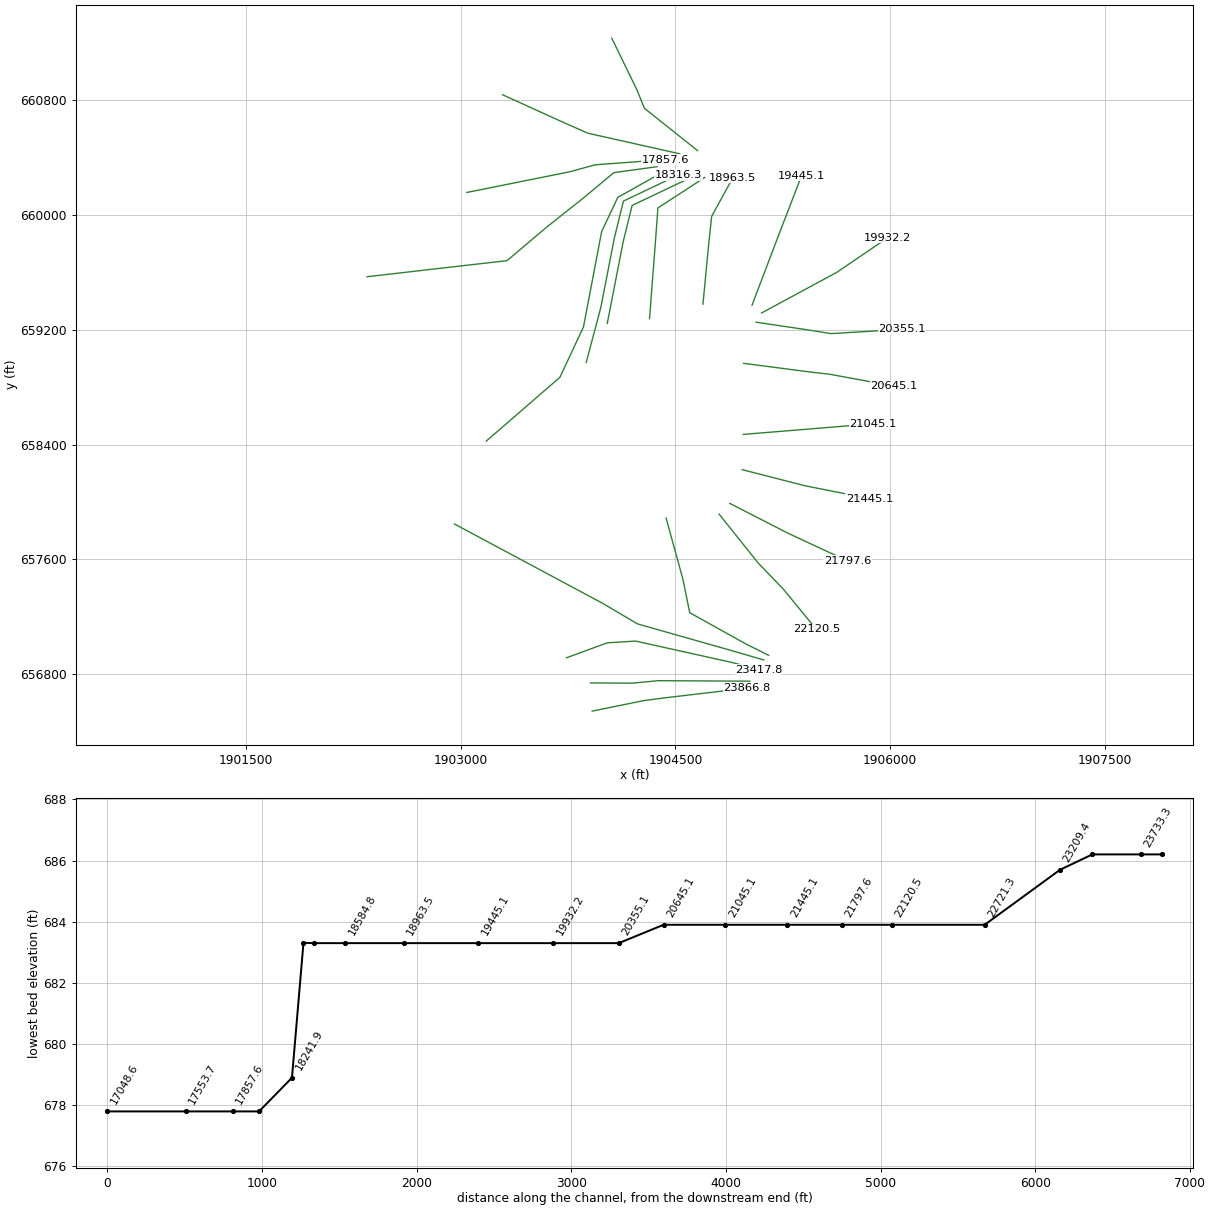
HEC-RAS study HenryFork.prj: HenryFork

--- HenryFork.g01 (geometry) --- (continued)

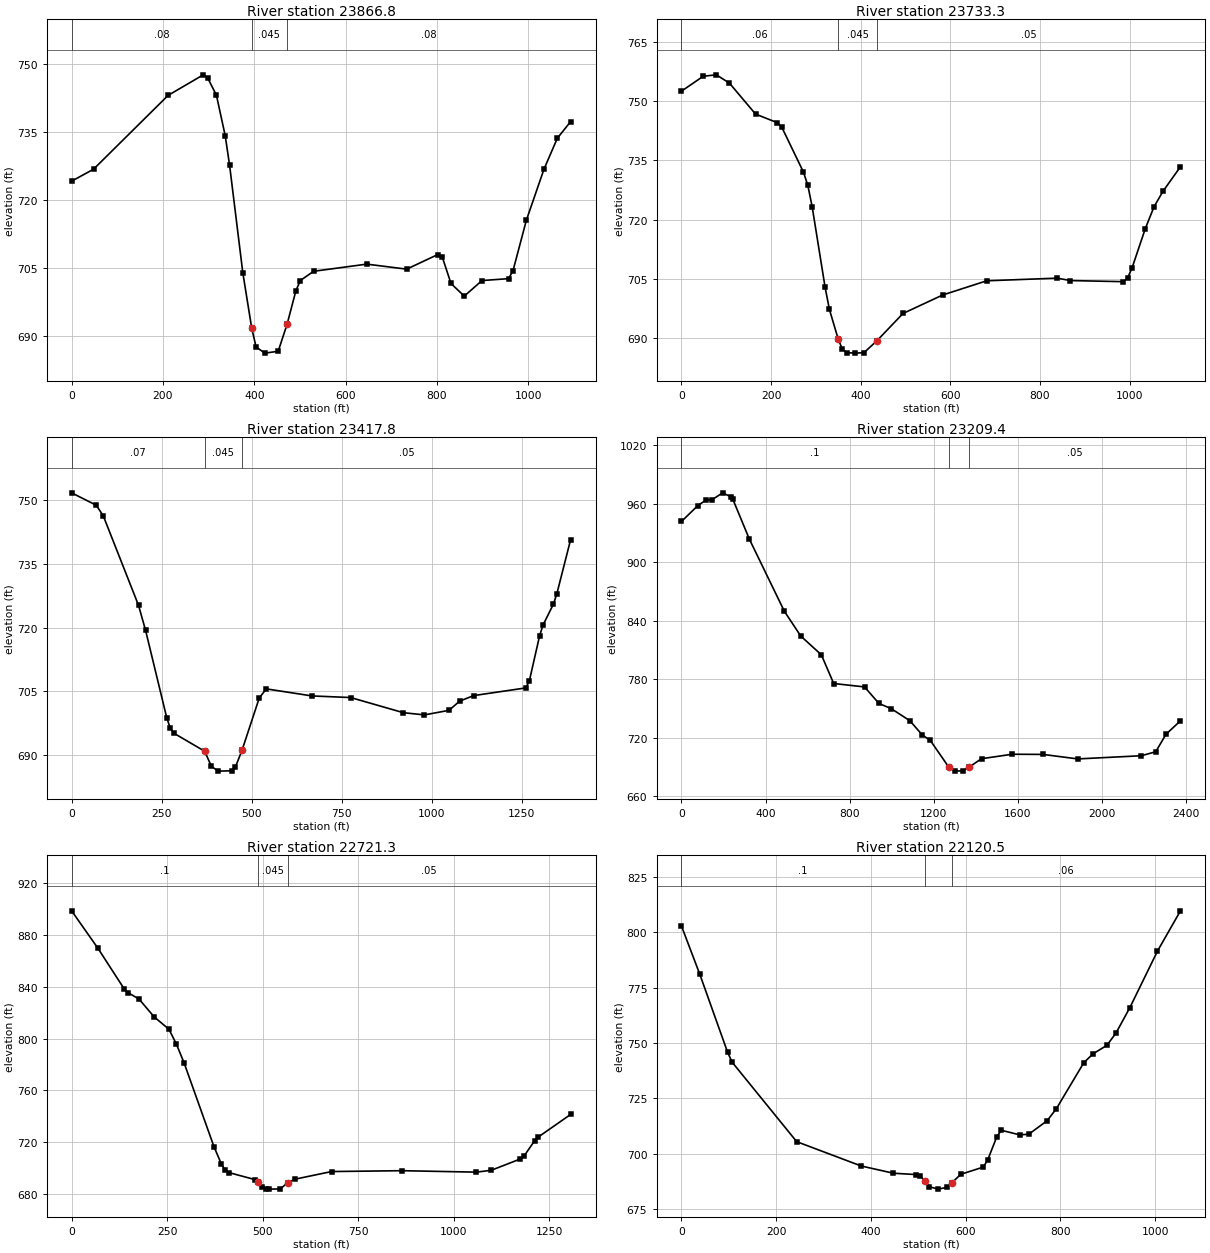
Type RM Length L Ch R = 1 ,23866.8 ,134.7,133.5,132.9
XS GIS Cut Line= 4
     1903918.721      656542.962      1904276.36      656615.879
     1904420.457      656634.976     1904998.582      656702.685
#Sta/Elev= 30
       0   724.2      48  726.85   211.3  743.17   288.2  747.71   297.8  747.03
     317  743.21   336.2  734.27   345.8  727.75   374.7  704.02   394.1  691.82
   403.8  687.55   423.1   686.2   452.2  686.61   471.6  692.55     491     700
   500.7  702.25   529.8  704.29   646.2  705.87   733.5  704.76   801.4  707.98
   811.1  707.54   830.5  701.59   859.6   698.8   898.4  702.24   956.6  702.66
   966.3  704.43   995.4  715.54  1034.2  726.89  1063.3   733.7  1092.4  737.37
#Mann= 3 , 0 , 0
       0     .08       0   394.1    .045       0   471.6     .08       0
Bank Sta=394.1,471.6
XS Rating Curve= 0 ,0
Exp/Cntr=0.3,0.1

Type RM Length L Ch R = 1 ,23733.3 ,316.6,315.6,314.8
XS GIS Cut Line= 4
     1903906.134      656739.577     1904197.801      656737.841
     1904380.092      656755.202     1905018.981       656751.73
#Sta/Elev= 30
       0  752.55    48.6  756.33    77.8  756.69     107   754.6   165.3  746.75
   213.9  744.57   223.6   743.5   272.2  732.06     282  728.71   291.7  723.29
   320.6  702.87   330.2  697.27   349.5  689.88   359.1  687.17   368.8  686.33
   387.4   686.2   407.3  686.31   436.2  689.33   494.4  696.24   582.9  700.92
   681.2  704.52   838.5  705.19     868  704.58   985.9   704.3   995.7  705.23
  1005.6  707.76    1035  717.67  1054.7  723.27  1074.4  727.14  1113.7  733.42
#Mann= 3 , 0 , 0
       0     .06       0   349.5    .045       0   436.2     .05       0
Bank Sta=349.5,436.2
XS Rating Curve= 0 ,0
Exp/Cntr=0.3,0.1

Type RM Length L Ch R = 1 ,23417.8 ,221.6,208.4,195.2
XS GIS Cut Line= 5
     1903739.467      656914.924     1904024.189      657019.091
     1904222.106      657031.244     1904898.526      656881.259
     1905083.186      656832.242
#Sta/Elev= 30
       0  751.78    68.5  748.85      88  746.33   185.8  725.26   205.4  719.35
   264.1  698.78   273.8  696.33   283.6  695.15   369.3  690.89   388.2  687.32
     407   686.2   444.8  686.28   454.3  687.08   473.1  691.11     521  703.45
   540.5  705.58   667.4  703.92   774.7  703.54   921.1  699.97   979.6  699.45
  1047.9  700.53  1077.2  702.69  1116.2     704  1261.2  705.81  1270.7  707.44
  1299.4  718.13    1309  720.66  1337.6  725.55  1347.2  728.01  1385.4  740.75
#Mann= 3 , 0 , 0
       0     .07       0   369.3    .045       0   473.1     .05       0
Bank Sta=369.3,473.1
XS Rating Curve= 0 ,0
Exp/Cntr=0.3,0.1

Type RM Length L Ch R = 1 ,23209.4 ,507,488.1,468.9
XS GIS Cut Line= 5
     1902956.884      657847.433     1903992.071      657294.265
     1904235.127      657151.035     1904890.865      656965.324
     1905116.606      656899.516
#Sta/Elev= 30
       0  941.99    78.2  958.35   117.4  964.08   146.7  964.47   195.6   971.4
   234.7  967.32   244.5  964.71   322.8  923.88     489   849.9   567.3  824.36
   665.1  805.12   723.8  775.65   870.5  772.14     939  755.17   997.7  749.78
  1085.7   737.5  1144.4  722.97  1183.4  717.15    1271  689.77  1300.2   685.7
  1339.1  686.05  1368.3  689.93  1426.6  698.45  1572.7  703.04  1718.7  702.86
  1884.2  698.23  2186.4   701.5  2254.9  705.59  2303.9  723.61  2372.5  737.32
#Mann= 3 , 0 , 0
       0      .1       0    1271    .045       0  1368.3     .05       0
Bank Sta=1271,1368.3
XS Rating Curve= 0 ,0
Exp/Cntr=0.3,0.1

Type RM Length L Ch R = 1 ,22721.3 ,587.8,600.8,613.9
XS GIS Cut Line= 5
      1904434.78      657888.883     1904551.967      657463.535
      1904599.71       657229.16     1904990.669      657012.064
      1905150.46      656932.068
#Sta/Elev= 30
       0  898.55    68.6  869.79   137.3  838.48   147.1  835.52   176.5   830.5
   215.7  816.85   254.9  807.18   274.5  795.59   294.1  781.53   372.6  716.68
   392.2  703.14     402  698.59   411.8  696.65   479.5  691.28     489  689.19
   498.6  685.76   508.2  683.98   517.7   683.9   546.4  684.04   565.6  688.97
   584.7  691.57   680.4  697.46   865.1  698.12  1059.5     697  1098.4  698.42
  1174.6  707.16    1184  709.27  1212.2  721.26  1221.6  724.07  1306.3  741.51
#Mann= 3 , 0 , 0
       0      .1       0     489    .045       0   565.6     .05       0
Bank Sta=489,565.6
XS Rating Curve= 0 ,0
Exp/Cntr=0.3,0.1

Type RM Length L Ch R = 1 ,22120.5 ,315.1,322.9,331.2
XS GIS Cut Line= 4
     1904804.729      657916.516     1905078.443      657574.646
     1905256.394      657390.185     1905484.259      657112.407
#Sta/Elev= 30
       0  802.85    38.9  780.92    97.3  745.83     107  741.28   243.3  705.35
   379.6  694.35   447.4  691.09   494.9  690.49   504.4  689.89   513.9  687.44
   523.4  684.96   542.4   683.9   561.4  684.77   570.8  686.75   589.8  690.61
   637.3  693.87   646.8  697.23   665.8  707.59   675.3  710.51   713.7  708.45
   733.1  708.69   771.9  714.81   791.4  720.21   849.6   741.1     869  745.07
   898.2   748.9   917.6  754.53   946.7  765.96    1005  791.51  1053.5   809.7
#Mann= 3 , 0 , 0
       0      .1       0   513.9    .045       0   570.8     .06       0
Bank Sta=513.9,570.8
XS Rating Curve= 0 ,0
Exp/Cntr=0.3,0.1

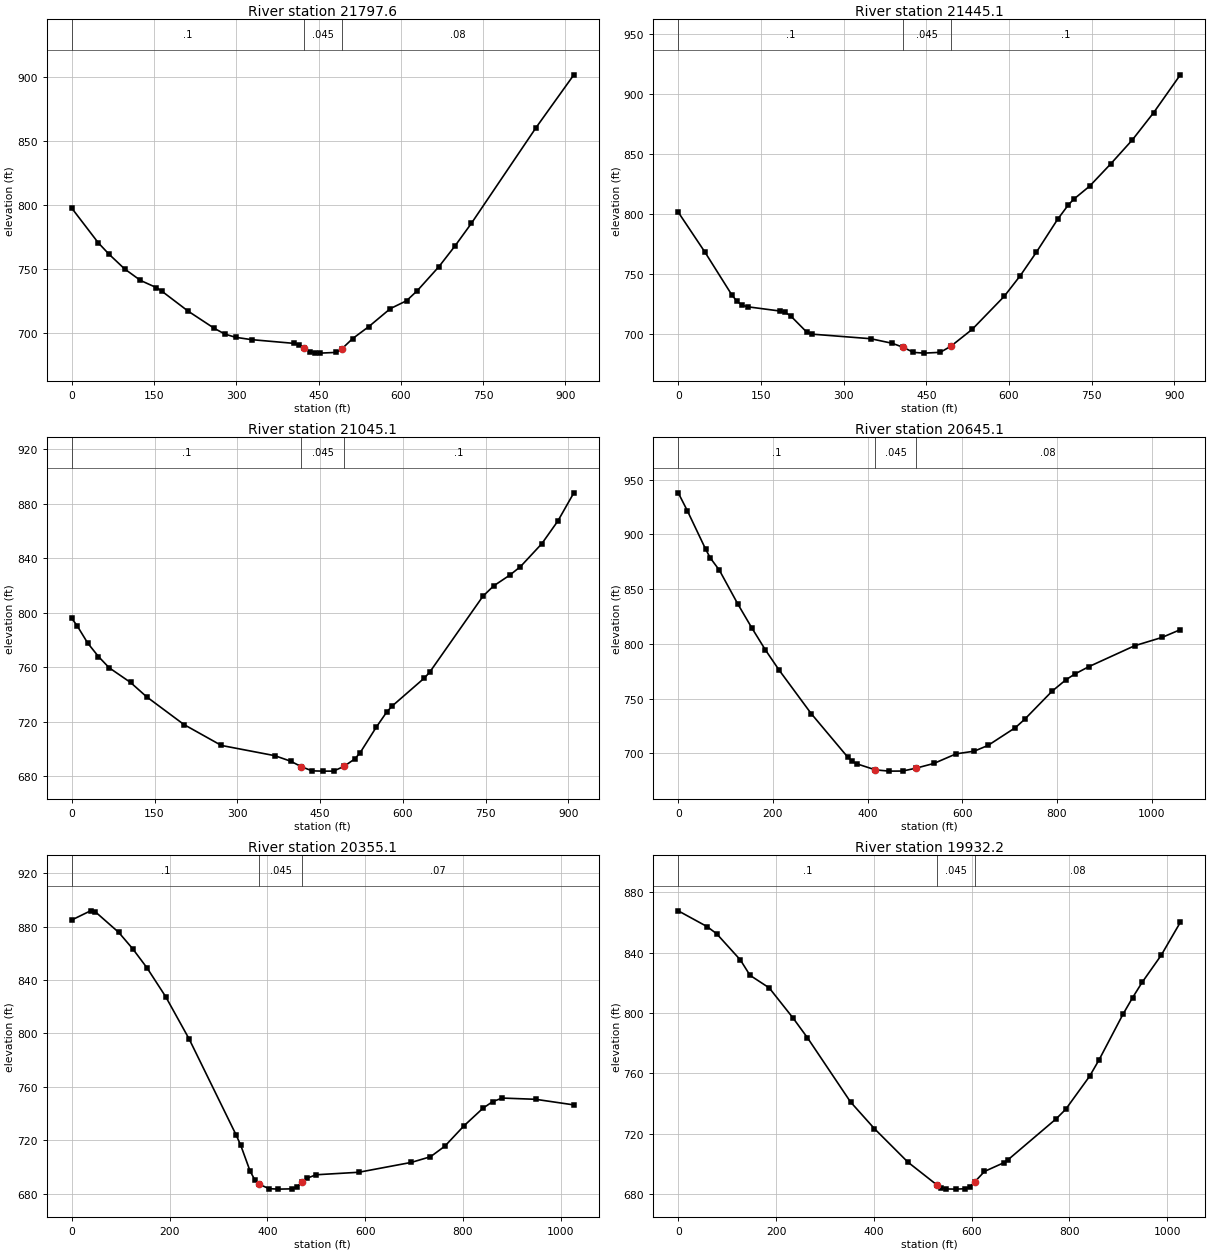
Type RM Length L Ch R = 1 ,21797.6 ,347.8,352.5,357.9
XS GIS Cut Line= 3
     1904879.626      657991.158      1905282.87      657784.716
       1905702.1      657589.644
#Sta/Elev= 30
       0   797.4    48.2  770.35    67.5  761.52    96.4  749.81   125.3  740.82
   154.2  735.22   163.9  732.51     212  716.81   260.2   703.2   279.5  698.76
   298.8  696.28   327.7  694.46   404.8  691.55   414.5   690.3   424.1  687.65
   433.7  685.15   443.4  684.06     453   683.9   482.5  684.47   492.4  687.24
     512  695.24   541.6  704.68   580.9  718.76   610.4  724.92   630.1  732.85
   669.5  751.65     699  767.97   728.5  785.46   846.5  860.48   915.4   901.8
#Mann= 3 , 0 , 0
       0      .1       0   424.1    .045       0   492.4     .08       0
Bank Sta=424.1,492.4
XS Rating Curve= 0 ,0
Exp/Cntr=0.3,0.1

Type RM Length L Ch R = 1 ,21445.1 ,392.5,400,406.3
XS GIS Cut Line= 3
     1904966.255      658226.116     1905407.923      658113.388
     1905854.134      658025.141
#Sta/Elev= 30
       0  801.27    48.5  767.96      97  732.53   106.7  726.92   116.4   723.7
   126.1  722.48   184.3  718.97     194  717.78   203.7  715.02   232.8  701.52
   242.5  699.72   349.1   695.9   387.9  692.11   407.3  688.89   426.7  684.51
   446.1   683.9   475.2  684.56   494.5  689.63   533.2   703.7   591.3   731.2
   620.4  748.38   649.4  767.78   688.1   795.3   707.4  807.22   717.1  811.94
   746.2  822.95   784.9   841.7   823.6  861.41   862.3  884.13   910.7  915.65
#Mann= 3 , 0 , 0
       0      .1       0   407.3    .045       0   494.5      .1       0
Bank Sta=407.3,494.5
XS Rating Curve= 0 ,0
Exp/Cntr=0.3,0.1

Type RM Length L Ch R = 1 ,21045.1 ,404.7,400,395.5
XS GIS Cut Line= 3
     1904973.546      658471.995     1905427.029      658509.113
     1905880.513      658546.231
#Sta/Elev= 30
       0   795.9     9.7  790.51      29  777.73    48.4  767.91    67.8  759.69
   106.5  748.93   135.5  738.46   203.3  718.07   271.1  702.74   367.9  695.24
   396.9  691.16   416.3   687.1   435.6   684.1     455   683.9   474.4   683.9
   493.7  687.47   513.1  692.89   522.8  697.47   551.8  716.07   571.2  727.43
   580.8  731.66   638.9  752.11   648.6  756.39   745.4  812.26   764.8  819.77
   793.8   827.6   813.2  833.84   851.9  850.66     881   867.3     910  887.98
#Mann= 3 , 0 , 0
       0      .1       0   416.3    .045       0   493.7      .1       0
Bank Sta=416.3,493.7
XS Rating Curve= 0 ,0
Exp/Cntr=0.3,0.1

Type RM Length L Ch R = 1 ,20645.1 ,290.7,290,289
XS GIS Cut Line= 4
     1904976.586      658967.478     1905427.755      658908.645
     1905577.512      658891.373     1906024.623      658809.456
#Sta/Elev= 30
       0  937.97    19.4  921.48    58.1  886.29    67.8  878.48    87.1  867.17
   125.8  836.48   154.9     815   183.9  794.68     213  776.16   280.7  736.45
   358.2  696.54   367.9  692.74   377.5  690.51   416.3  685.07   445.3   683.9
   473.8  683.97   502.1  686.59   539.8   690.9   586.9  699.69   625.1  702.12
   654.1  707.34   712.1  723.64   731.5  731.17   789.5  756.87   818.5  767.21
   837.8  772.61   866.9  779.23   963.6  798.33  1021.6  805.95  1060.3  813.05
#Mann= 3 , 0 , 0
       0      .1       0   416.3    .045       0   502.1     .08       0
Bank Sta=416.3,502.1
XS Rating Curve= 0 ,0
Exp/Cntr=0.3,0.1

Type RM Length L Ch R = 1 ,20355.1 ,408,422.9,437.7
XS GIS Cut Line= 4
     1905063.252      659254.334     1905443.026       659197.91
     1905585.683      659174.842     1906083.217      659204.421
#Sta/Elev= 30
       0  885.02    38.4  891.87      48  891.19      96  875.72   124.8  863.35
   153.6  849.27     192  827.58     240  795.85     336  724.02   345.6  716.14
   364.8  696.73   374.3  690.32   383.9  686.88   403.2  683.65   422.5   683.3
   451.4  683.52     461   685.1   470.6  688.42   480.3  691.35   499.6  694.06
   587.1  695.94   694.6  703.34   733.7  707.57     763  715.47   802.1  730.71
   841.2  743.98   860.7  748.83   880.3  751.55   948.7  750.62  1026.9  746.42
#Mann= 3 , 0 , 0
       0      .1       0   383.9    .045       0   470.6     .07       0
Bank Sta=383.9,470.6
XS Rating Curve= 0 ,0
Exp/Cntr=0.3,0.1

Type RM Length L Ch R = 1 ,19932.2 ,471,487.1,503.1
XS GIS Cut Line= 3
     1905101.111      659318.385     1905626.646      659601.755
     1905982.395      659843.173
#Sta/Elev= 30
       0  867.63    58.7  857.24    78.3  852.54   127.2  835.06   146.8  824.92
     186  816.62   234.9  796.62   264.3  783.57   352.4  741.05   401.3  723.35
   469.8  701.18   528.6  686.21   538.3  684.16   548.1  683.42   567.7   683.3
   587.3  683.56   597.1  684.99   606.8   688.2   626.4  695.01   665.5  700.71
   675.2  702.92   772.9  729.82   792.5  736.15   841.3  757.98   860.9  768.99
   909.7  799.12   929.3  810.07   948.8  820.22   987.9   838.2    1027     860
#Mann= 3 , 0 , 0
       0      .1       0   528.6    .045       0   606.8     .08       0
Bank Sta=528.6,606.8
XS Rating Curve= 0 ,0
Exp/Cntr=0.3,0.1

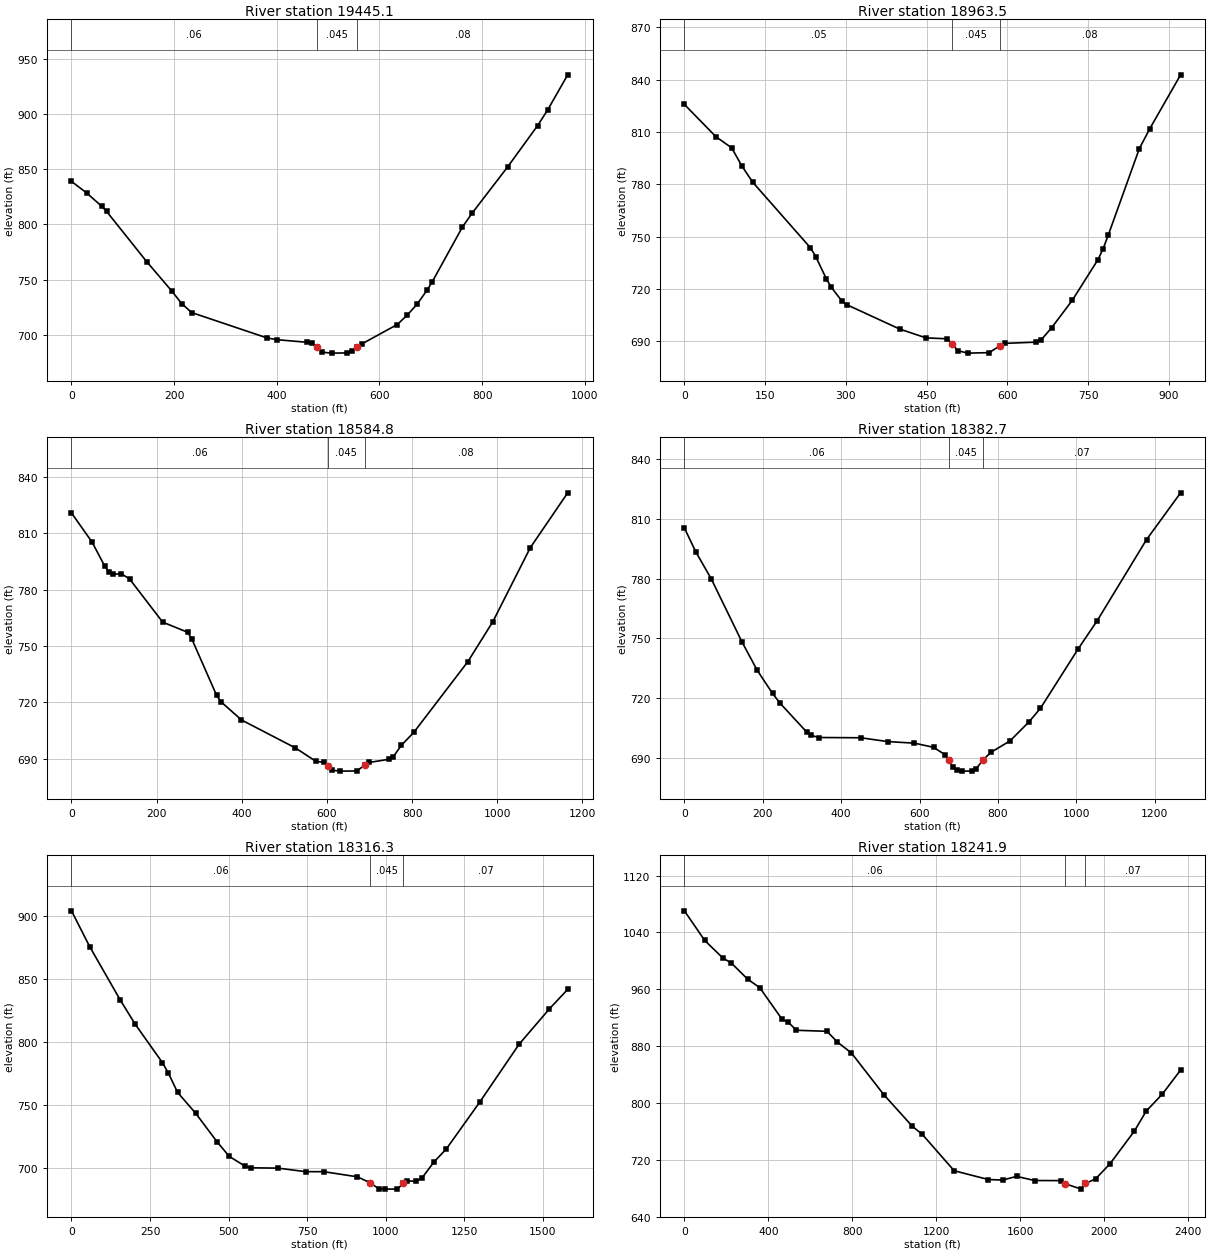
Type RM Length L Ch R = 1 ,19445.1 ,475.8,481.6,487.5
XS GIS Cut Line= 3
      1905035.04      659373.692     1905219.313      659857.278
     1905381.232        660276.4
#Sta/Elev= 30
       0  838.97    29.3  828.62    58.6  816.55    68.4  811.76   146.5  766.26
   195.3  739.66   214.8  728.18   234.3  720.06   380.8   697.1   400.3  695.48
   458.9  693.13   468.7  692.11   478.4  688.45   488.2  684.14   507.7   683.3
     537  683.48   546.8  685.21   556.6  688.61   566.3  691.79   634.7  709.23
   654.2  717.79   673.8  727.92   693.3  740.74   703.1  748.16   761.7  797.62
   781.2  810.59   849.6     852   908.2  889.59   927.8  903.83   966.8   935.6
#Mann= 3 , 0 , 0
       0     .06       0   478.4    .045       0   556.6     .08       0
Bank Sta=478.4,556.6
XS Rating Curve= 0 ,0
Exp/Cntr=0.3,0.1

Type RM Length L Ch R = 1 ,18963.5 ,377.9,378.6,379.4
XS GIS Cut Line= 4
     1904692.158      659380.202     1904731.221      659788.188
     1904752.922      659992.181     1904900.492      660261.278
#Sta/Elev= 30
       0  825.83    58.6  807.31    87.8  800.96   107.3   790.3   126.9  781.26
   234.2  743.67     244  738.66   263.5  726.02   273.2  720.92   292.8  713.08
   302.5  710.94   400.1  697.08   448.9  692.04     488   691.5   497.8   688.7
   507.5  684.71   527.1   683.3   566.2  683.59   585.7  687.38   595.5  688.89
   653.4   689.6     663  690.98   682.1  697.76   720.5   713.5   768.4  736.88
     778  743.17   787.6     751   845.2  800.47   864.4  811.78   921.9  842.78
#Mann= 3 , 0 , 0
       0     .05       0   497.8    .045       0   585.7     .08       0
Bank Sta=497.8,585.7
XS Rating Curve= 0 ,0
Exp/Cntr=0.3,0.1

Type RM Length L Ch R = 1 ,18584.8 ,205.9,202.1,198.3
XS GIS Cut Line= 4
     1904318.894      659278.206     1904360.127       659812.06
     1904377.488      660050.775     1904705.179      660263.449
#Sta/Elev= 30
       0  820.93    48.7  805.25    77.9  792.62    87.6  789.49    97.4  788.21
   116.8  788.53   136.3  785.77   214.2  762.72   272.6  757.34   282.3  753.91
   340.7  723.76   350.5   720.4   399.2  710.58   525.7   695.7   573.7  688.57
   592.9  687.97   602.5  685.89     612  683.76   631.2   683.3   669.5  683.38
   688.6  686.42   698.2   687.9   746.1  689.62   755.6   690.9   774.8   697.1
   804.1     704     931  741.69   989.6  762.97  1077.6  802.42  1165.4  831.64
#Mann= 3 , 0 , 0
       0     .06       0   602.5    .045       0   688.6     .08       0
Bank Sta=602.5,688.6
XS Rating Curve= 0 ,0
Exp/Cntr=0.3,0.1

Type RM Length L Ch R = 1 ,18382.7 ,66.4,66.4,66.4
XS GIS Cut Line= 4
     1904023.755      659245.653     1904134.432       659812.06
     1904197.367      660068.136     1904581.481      660250.428
#Sta/Elev= 30
       0  805.39    29.3  793.32    68.5  779.86   146.7  748.26   185.8  733.94
     225  722.29   244.5  717.32     313  702.72   322.8  701.33   342.4  700.18
     450  700.05   518.4  698.14   586.9  697.34   635.7  695.25     665  691.54
   674.8  688.84   684.6  685.38   694.3  683.62   709.4   683.3   733.4  683.36
   743.2  684.21   762.7   689.1   782.2  692.75     831  698.51   879.5  708.09
   908.5  714.87  1005.1   744.8  1053.4  758.89    1179  799.52    1266  823.03
#Mann= 3 , 0 , 0
       0     .06       0   674.8    .045       0   762.7     .07       0
Bank Sta=674.8,762.7
XS Rating Curve= 0 ,0
Exp/Cntr=0.3,0.1

Type RM Length L Ch R = 1 ,18316.3 ,79,74.5,69.9
XS GIS Cut Line= 5
     1903877.023      658974.169     1903978.733      659356.593
     1904073.669      659842.442     1904136.603      660098.518
     1904520.717       660280.81
#Sta/Elev= 30
       0  903.72    57.9  875.41   154.4  833.45   202.7  813.95   289.6  783.47
   308.8  775.02   337.8  759.91   395.7  743.27   463.7  720.69   502.5  709.19
     551  701.77   570.4   700.2   657.8  699.94   745.2  697.15   803.4  697.12
   910.3  693.05   949.4  688.48   978.6  683.55   998.2  683.31  1037.2  683.38
  1056.8  687.92  1066.6  689.87  1095.8  689.54  1115.4  692.02  1154.4  704.98
  1193.1  715.08  1299.4  752.16    1425   798.1  1521.6  826.14  1579.6  841.52
#Mann= 3 , 0 , 0
       0     .06       0   949.4    .045       0  1056.8     .07       0
Bank Sta=949.4,1056.8
XS Rating Curve= 0 ,0
Exp/Cntr=0.3,0.1

Type RM Length L Ch R = 1 ,18241.9 ,222.2,212.9,203.5
XS GIS Cut Line= 6
     1903179.106      658425.558     1903692.995      658870.002
     1903857.548      659220.427     1903984.693      659885.844
      1904097.54       660124.56      1904407.87      660298.171
#Sta/Elev= 30
       0 1070.39    97.1 1028.66   184.4 1003.72   223.2  997.07   300.9  974.37
   359.1  962.28   465.9  917.59     495  913.59   533.8  902.34   679.4  900.92
   727.8  886.03   795.6  870.47   950.4  811.62  1085.6  767.32  1133.1  755.99
  1285.2  704.75  1448.4  692.36  1515.6  691.65  1582.5  696.84    1668     691
    1793  690.88  1812.5  686.61  1890.8   678.9  1910.3  686.82  1959.2  693.45
  2027.3  714.55  2142.6  760.16  2200.3   788.8  2277.2  812.76  2363.7  846.42
#Mann= 3 , 0 , 0
       0     .06       0  1812.5    .045       0  1910.3     .07       0
Bank Sta=1812.5,1910.3
XS Rating Curve= 0 ,0
Exp/Cntr=0.3,0.1

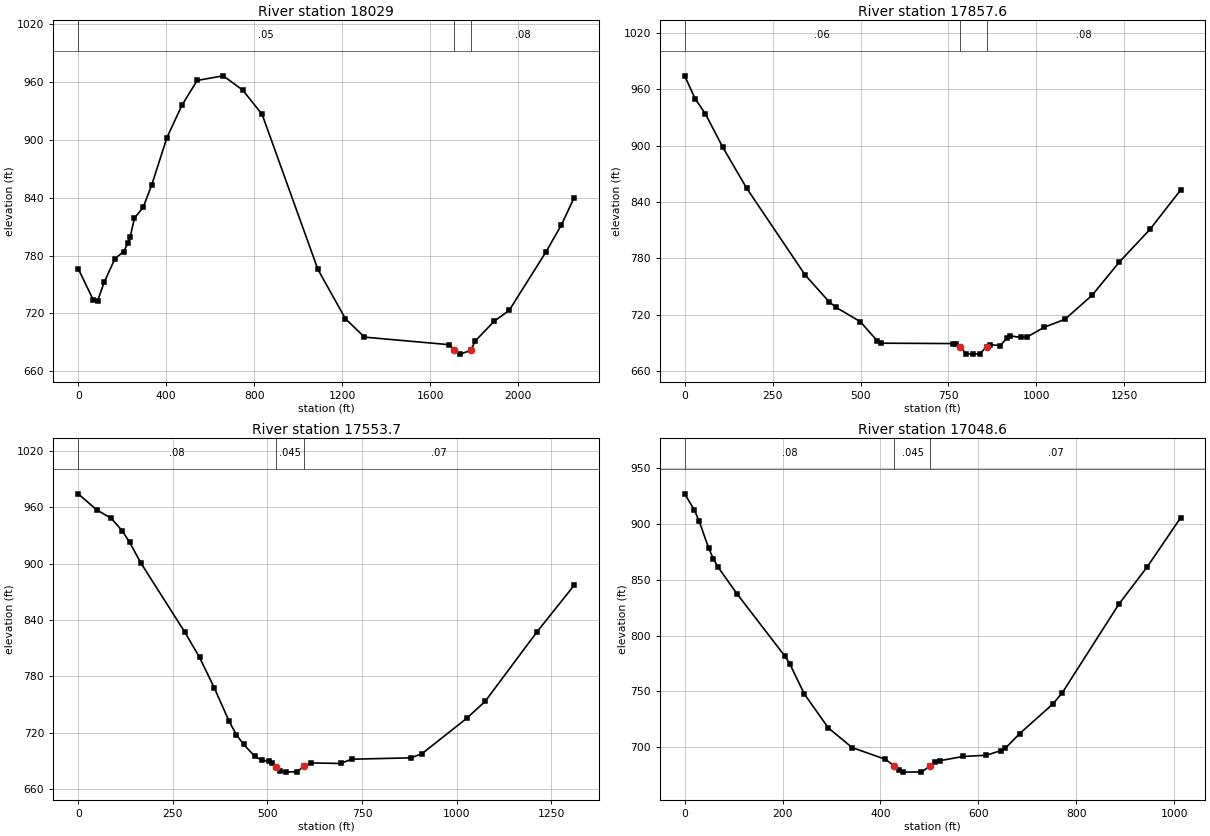
Type RM Length L Ch R = 1 ,18029   ,181.5,171.4,161.3
XS GIS Cut Line= 6
     1902346.641      659571.391     1903323.646      659683.389
     1903603.617      659919.265     1903853.617      660117.181
     1904069.762      660296.869     1904371.846      660338.535
#Sta/Elev= 30
       0  766.44    68.8  733.78    88.5  733.26     118  752.32   167.2  776.87
   206.5  784.04   226.2     793     236  798.98   255.7  818.78     295  829.82
   334.4  853.39   403.2  902.16     472  936.02   540.9  961.52   658.9   966.3
   747.4  951.61   835.9  926.35  1089.4   765.7  1214.6  714.48  1301.3  695.42
  1687.7  687.56  1707.1  682.42  1736.2   677.8  1784.7  681.73    1804  691.22
  1891.3  711.98  1959.3  723.22  2126.5  783.83  2195.4  811.32  2254.4  839.92
#Mann= 3 , 0 , 0
       0     .05       0  1707.1    .045       0  1784.7     .08       0
Bank Sta=1707.1,1784.7
XS Rating Curve= 0 ,0
Exp/Cntr=0.3,0.1

Type RM Length L Ch R = 1 ,17857.6 ,318.6,303.9,289.2
XS GIS Cut Line= 4
     1903043.721      660158.848     1903763.164      660303.106
     1903939.554      660351.556     1904431.742      660388.015
#Sta/Elev= 30
       0  974.39    29.4  950.21    58.7  934.03   107.6   898.8   176.1  854.72
   342.4   762.2   410.9   733.5   430.5  727.63     499  712.52   547.9  691.84
   557.7  689.47   762.6  689.05   772.3   688.7   781.9  685.61   801.2  678.23
   820.4   677.8   839.7  678.32   858.9  685.78   868.6  687.74   897.4  686.99
   916.7  695.06   926.4   697.3   955.4  695.53   974.8  696.32  1023.1  706.58
  1081.2  714.88  1158.6  740.58    1236  775.97  1323.1  810.76  1410.2   852.7
#Mann= 3 , 0 , 0
       0     .06       0   781.9    .045       0   858.9     .08       0
Bank Sta=781.9,858.9
XS Rating Curve= 0 ,0
Exp/Cntr=0.3,0.1

Type RM Length L Ch R = 1 ,17553.7 ,523.1,505.1,487
XS GIS Cut Line= 4
     1903292.853      660839.837     1903717.332      660647.129
     1903889.207      660571.608     1904529.832      660428.379
#Sta/Elev= 30
       0  974.21    48.6  957.24    87.4   948.1   116.5  934.71     136   922.5
   165.1  900.84   281.6  826.94   320.5   800.1   359.3  767.77   398.2   732.4
   417.6  717.82     437  707.38   466.2  694.73     485  690.58   503.7  689.37
   513.1   687.4   522.5  683.07   531.9  679.23   549.7   677.8   578.8   678.3
   597.6  684.58   616.4  687.58   693.1  687.04   722.5  691.56   879.3  693.02
   908.6  697.52  1026.2  735.02  1075.2  753.17  1212.4  827.28  1310.4  876.78
#Mann= 3 , 0 , 0
       0     .08       0   522.5    .045       0   597.6     .07       0
Bank Sta=522.5,597.6
XS Rating Curve= 0 ,0
Exp/Cntr=0.3,0.1

Type RM Length L Ch R = 1 ,17048.6 ,452.6,454.5,457.2
XS GIS Cut Line= 4
     1904055.439      661233.935     1904231.221      660873.692
     1904283.304      660745.653     1904654.398      660450.515
#Sta/Elev= 30
       0  926.75    19.6  912.38    29.3  902.63    48.9  878.25    58.7  868.54
    68.4  861.05   107.5  836.92   205.3  781.25   215.1  774.29   244.4  747.75
   293.3  717.45   342.2  699.73   410.1  689.29   428.5  683.22   437.7   679.5
   446.9   677.8   483.8  677.96   502.2  683.44   511.4  686.79   520.6  687.94
   568.1  691.78   616.5  692.91   645.5  696.98   655.2  699.18   684.2  712.22
     752  738.66   771.3  748.68   887.4  828.28   945.5  861.72  1013.2  905.36
#Mann= 3 , 0 , 0
       0     .08       0   428.5    .045       0   502.2     .07       0
Bank Sta=428.5,502.2
XS Rating Curve= 0 ,0
Exp/Cntr=0.3,0.1