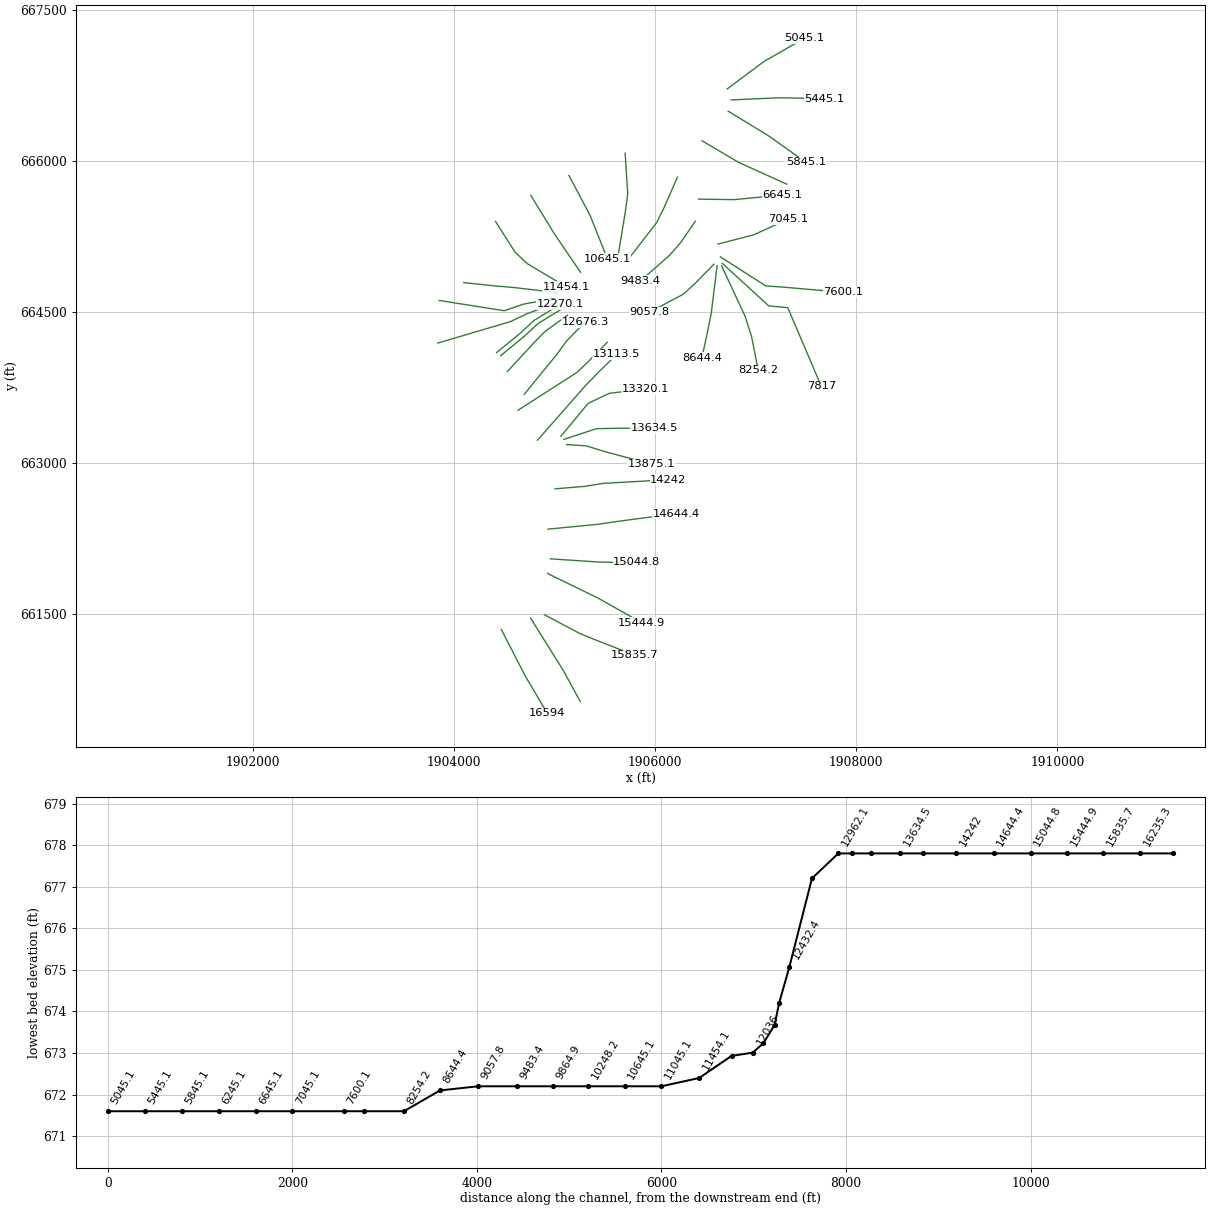
HEC-RAS study HenryFork.prj: HenryFork

--- HenryFork.g01 (geometry) --- (continued)

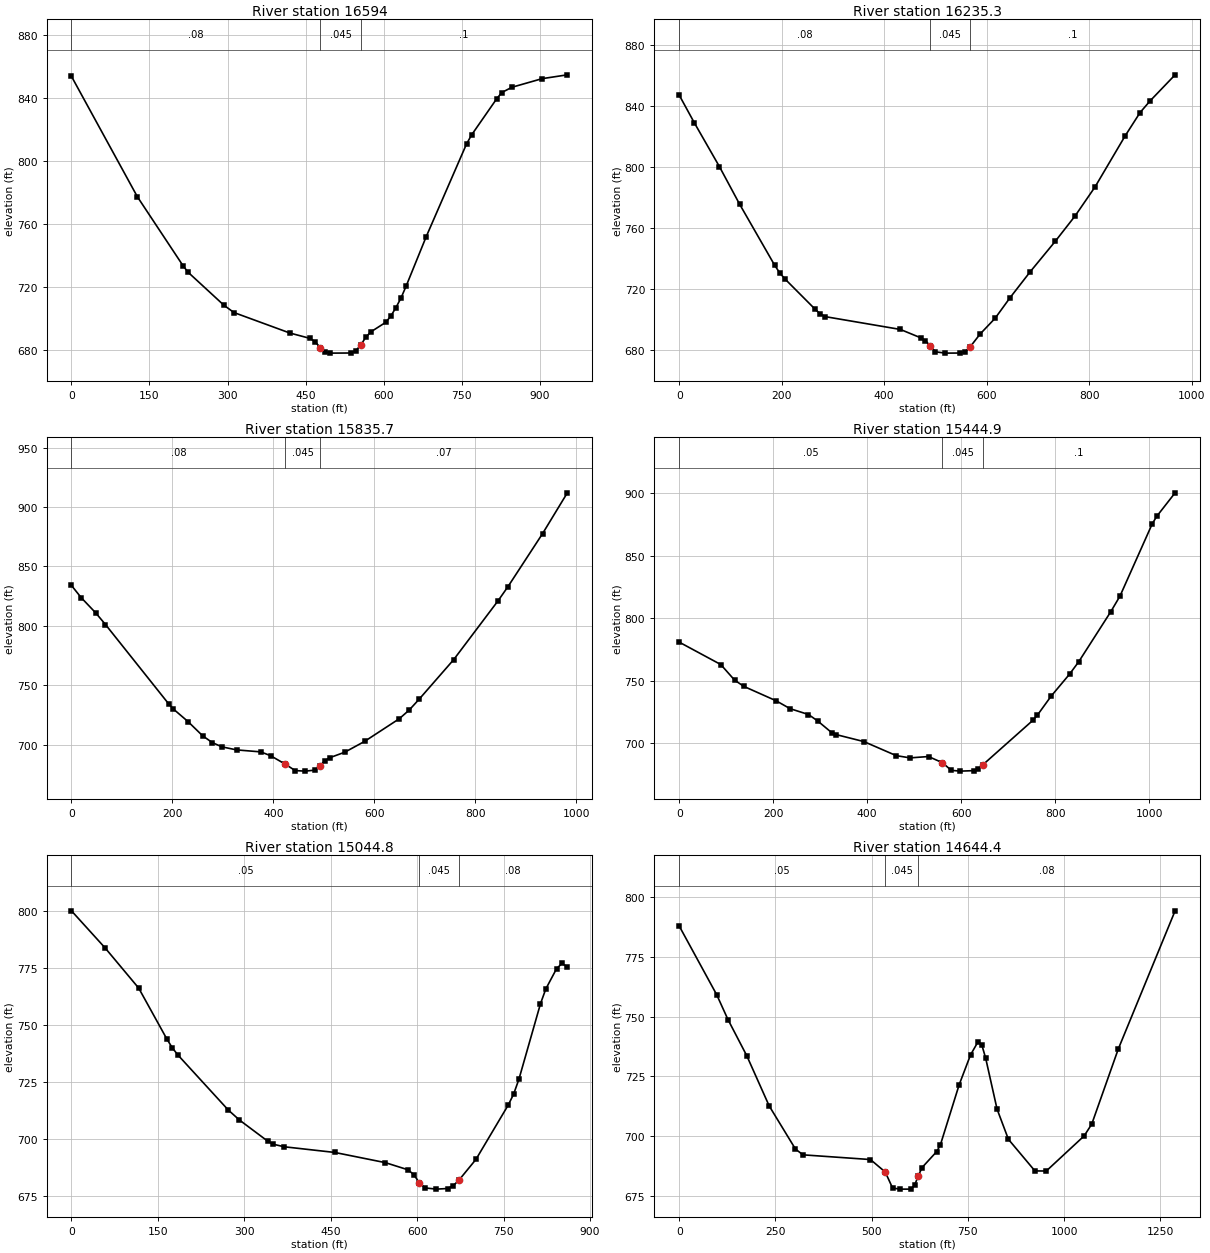
Type RM Length L Ch R = 1 ,16594   ,356.8,358.8,359.8
XS GIS Cut Line= 3
     1904469.936      661342.442     1904706.481      660882.372
     1904927.835      660506.938
#Sta/Elev= 30
       0  853.99   126.9  777.23   214.7  733.33   224.5  729.19   292.8  708.36
   312.3  703.64   419.7  690.61   458.8  687.16   468.5  684.98   478.3  681.37
     488  678.45   497.8   677.8   536.7  677.88   546.4  679.24   556.1  682.99
   565.7  687.86   575.4  691.32   604.5  697.48   614.2  701.57   623.8  706.83
   633.5  712.94   643.2  720.37     682  752.01   759.4  810.94   769.1  816.68
   817.6  839.81   827.2  843.69   846.6  847.04   904.7  852.52   953.2  854.96
#Mann= 3 , 0 , 0
       0     .08       0   478.3    .045       0   556.1      .1       0
Bank Sta=478.3,556.1
XS Rating Curve= 0 ,0
Exp/Cntr=0.3,0.1

Type RM Length L Ch R = 1 ,16235.3 ,385.2,399.6,414.1
XS GIS Cut Line= 4
     1904760.735      661455.289     1905010.301      661055.983
     1905097.612      660915.839     1905255.526      660624.126
#Sta/Elev= 30
       0  846.96    29.4  828.87    78.5  800.07   117.7  775.54   186.4  735.33
   196.2  730.41     206  726.55   264.9  706.68   274.7  703.66   284.5  701.75
   431.6  693.33   470.9   687.9   480.6  685.95   490.3  682.43     500  678.66
   519.4   677.8   548.6  677.86   558.3  678.74     568  682.02   587.4  690.39
   616.6  700.71   645.8  714.22   684.8  731.09   733.6  751.01   772.6  767.77
   811.6  786.84   870.2  820.23   899.4  835.56   918.9  843.18   967.7  860.27
#Mann= 3 , 0 , 0
       0     .08       0   490.3    .045       0     568      .1       0
Bank Sta=490.3,568
XS Rating Curve= 0 ,0
Exp/Cntr=0.3,0.1

Type RM Length L Ch R = 1 ,15835.7 ,393.7,390.8,387.9
XS GIS Cut Line= 4
     1904898.254      661487.886     1905255.526      661299.039
     1905410.344      661236.342     1905793.721      661086.365
#Sta/Elev= 30
       0  833.96    19.2  823.77    48.1  810.88    67.4  801.12   192.4  734.51
   202.1  729.98   230.9  719.52   259.8   707.6     279  701.82   298.3  698.21
   327.1  695.67   375.2  693.98   394.5  690.81   423.8  683.65   443.4  678.25
   463.1   677.8   482.7  678.63   492.5  682.34   502.4  686.61   512.2  689.14
   541.7  693.71   580.9  702.79   649.6  721.83   669.2  729.09   688.8  738.16
   757.4   771.5   845.6  821.14   865.2  833.02   933.8  877.65   982.8  911.88
#Mann= 3 , 0 , 0
       0     .08       0   423.8    .045       0   492.5     .07       0
Bank Sta=423.8,492.5
XS Rating Curve= 0 ,0
Exp/Cntr=0.3,0.1

Type RM Length L Ch R = 1 ,15444.9 ,388.9,400,411.2
XS GIS Cut Line= 4
     1904930.005      661897.997     1905433.478      661652.771
      1905549.93       661586.85     1905864.733      661409.509
#Sta/Elev= 30
       0   780.9    88.4  763.01   117.9  750.52   137.6  745.52   206.3  734.02
   235.8  727.74   275.1  723.05   294.8  717.86   324.2  708.65     334  706.99
     393  701.41   461.8  690.19   491.2  688.39   530.5  689.47     560  684.54
   579.1  678.41   598.2   677.8   626.9  678.19   636.5   679.9     646  682.84
   752.4  718.36   762.2  722.57   791.5  737.78   830.6  755.31   850.1  765.22
   918.4  805.27     938  817.78  1006.3  875.27  1016.1  881.45  1055.2  900.25
#Mann= 3 , 0 , 0
       0     .05       0     560    .045       0     646      .1       0
Bank Sta=560,646
XS Rating Curve= 0 ,0
Exp/Cntr=0.3,0.1

Type RM Length L Ch R = 1 ,15044.8 ,396.7,400.4,404.2
XS GIS Cut Line= 4
     1904958.217      662043.396     1905452.962      662011.058
     1905659.172      662006.504     1905817.553      662016.243
#Sta/Elev= 30
       0  799.92    58.3  783.67   116.7  766.01   165.3  743.79     175  739.82
   184.7  736.67   272.2  712.51   291.6  708.12   340.3  698.91     350  697.51
   369.4  696.38   456.9   693.9   544.9  689.42   584.2  686.28     594   684.2
   603.8  680.62   613.7  678.33   633.3   677.8     653  678.07   662.8  679.35
   672.6  681.76   702.1  690.86   758.1  714.69   767.4  719.45   776.7  726.06
   814.1  759.18   823.4  765.68   842.1  774.57   851.4  776.85   860.7   775.3
#Mann= 3 , 0 , 0
       0     .05       0   603.8    .045       0   672.6     .08       0
Bank Sta=603.8,672.6
XS Rating Curve= 0 ,0
Exp/Cntr=0.3,0.1

Type RM Length L Ch R = 1 ,14644.4 ,402.1,402.4,402.3
XS GIS Cut Line= 4
     1904934.346      662338.535     1905438.469      662388.101
     1905617.939       662414.49     1906212.992      662493.483
#Sta/Elev= 30
       0  787.99    97.4  759.21   126.6  748.83   175.4   733.7   233.8  712.62
     302  694.58   321.5  692.16   496.8  690.19   535.2  684.97   554.3  678.25
   573.4   677.8     602   677.8   611.6  679.46   621.1  683.38   630.7  686.81
   668.9  693.53   678.4  696.31   727.3  721.54   756.8  734.02   776.5  739.59
   786.4  738.02   796.2  732.58   825.7  711.31   855.2  698.66   924.1  685.42
   953.6  685.39    1052   700.1  1071.7  705.04  1140.6  736.48  1288.2  794.35
#Mann= 3 , 0 , 0
       0     .05       0   535.2    .045       0   621.1     .08       0
Bank Sta=535.2,621.1
XS Rating Curve= 0 ,0
Exp/Cntr=0.3,0.1

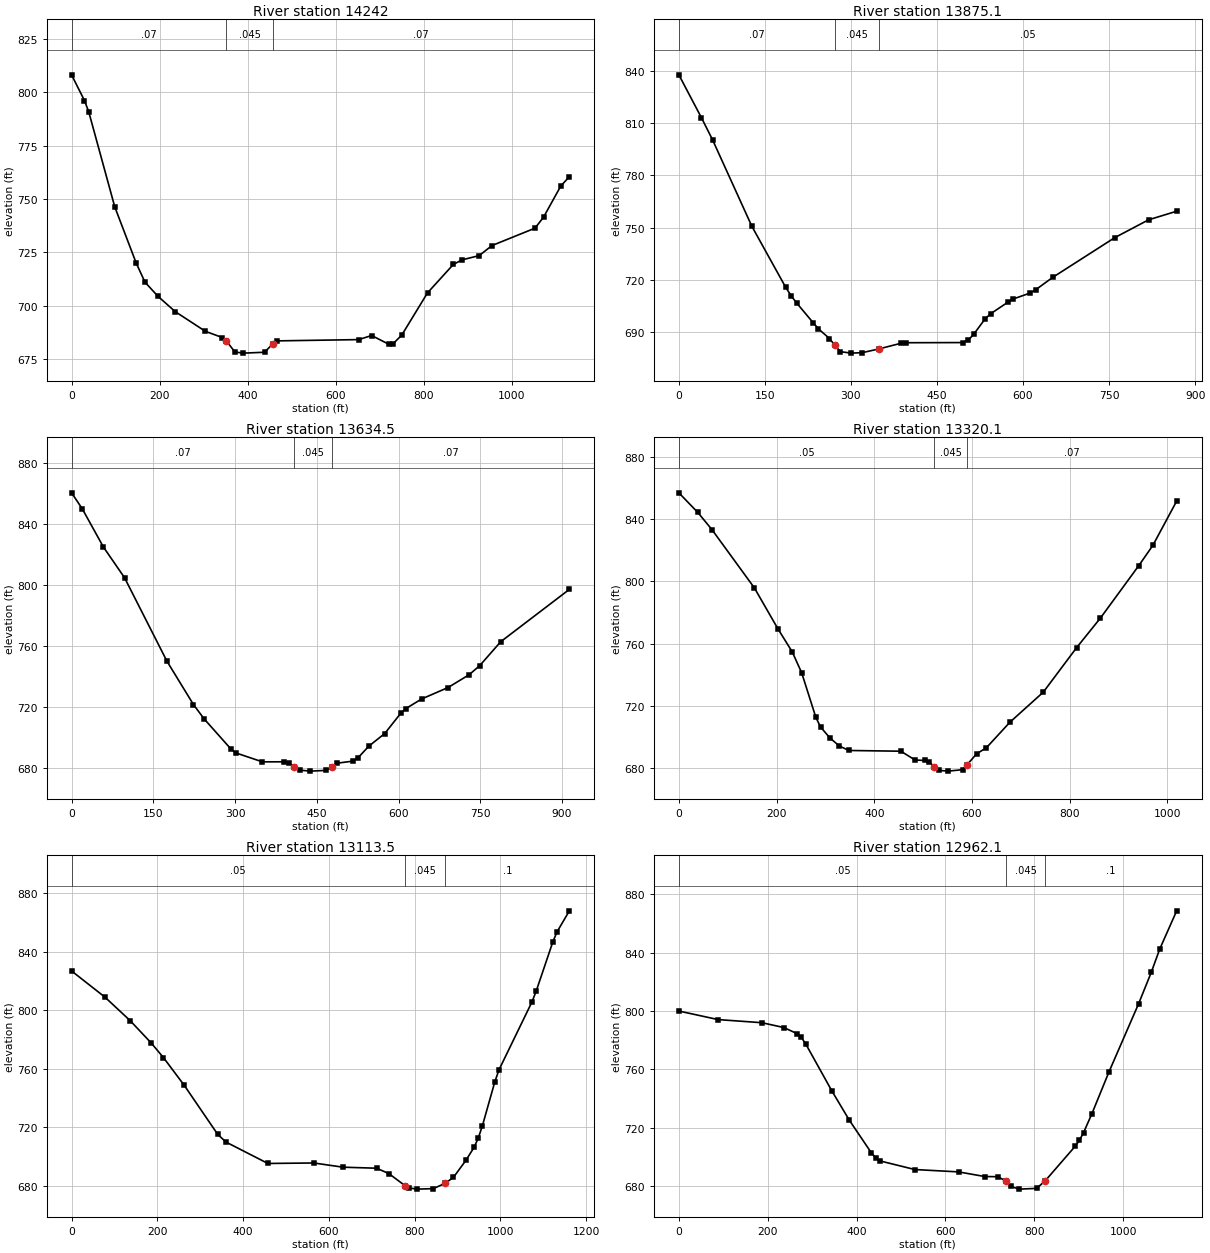
Type RM Length L Ch R = 1 ,14242   ,377.1,366.9,356.7
XS GIS Cut Line= 4
     1905004.658      662739.577     1905298.061      662763.883
     1905487.731      662794.265     1906131.394      662829.855
#Sta/Elev= 30
       0  808.11    29.4  796.04    39.2  790.68    98.1  746.33   147.2   719.8
   166.8  711.04   196.3  704.41   235.5  697.24     304  688.02   342.4  685.11
     352  683.44   371.2  678.32   390.4   677.8   438.5  678.21   457.7  682.22
   467.3  683.54   652.5  684.13   681.8  686.05   720.9  681.95   730.7  682.23
   750.2  686.22   808.8  706.02   867.4  719.31     887  721.46     926  723.45
   955.3  728.17    1053  736.31  1072.5  741.48  1111.6  756.03  1131.1  760.44
#Mann= 3 , 0 , 0
       0     .07       0     352    .045       0   457.7     .07       0
Bank Sta=352,457.7
XS Rating Curve= 0 ,0
Exp/Cntr=0.3,0.1

Type RM Length L Ch R = 1 ,13875.1 ,233.1,240.6,248
XS GIS Cut Line= 4
     1905119.676      663179.681     1905314.988       663166.66
      1905497.28      663110.671     1905962.123      662985.671
#Sta/Elev= 30
       0  837.82    39.2  813.24    58.7  800.48   127.2  750.75     186  715.76
   195.8  710.73   205.3  706.64   233.9  695.36   243.4  691.75   262.5  686.19
     272  682.32   281.6  678.63   300.6   677.8   319.7  678.07   348.3  680.18
   386.4  683.41   396.3  683.78   494.5  683.87   504.3  685.21   514.2  688.73
   533.8  697.48   543.6  700.47   573.1  706.98   582.9  708.94   612.4  712.36
   622.2  714.28   651.7  721.36   759.7  744.17   818.7  754.44   867.8   759.4
#Mann= 3 , 0 , 0
       0     .07       0     272    .045       0   348.3     .05       0
Bank Sta=272,348.3
XS Rating Curve= 0 ,0
Exp/Cntr=0.3,0.1

Type RM Length L Ch R = 1 ,13634.5 ,304.8,314.5,324
XS GIS Cut Line= 4
       1905093.2      663231.331     1905416.551      663337.667
     1905631.394      663342.008     1905989.467      663342.008
#Sta/Elev= 30
       0  860.67    19.4  850.33    58.4  825.09    97.2   804.9   175.1  749.98
   223.7  721.52   243.1   712.2   291.8  692.58   301.5  689.76   350.2   683.9
   389.2  683.93     399  683.12   408.8  680.62   418.5  678.45   438.1   677.8
   467.4  678.29   477.1  680.72   486.9     683   516.2  684.36     526  686.71
   545.5  694.22   574.6  702.49   603.7  715.67   613.3  718.89   642.4  725.22
   690.8  732.73   729.5  741.15   748.8  747.08   787.5  762.85   913.4  797.22
#Mann= 3 , 0 , 0
       0     .07       0   408.8    .045       0   477.1     .07       0
Bank Sta=408.8,477.1
XS Rating Curve= 0 ,0
Exp/Cntr=0.3,0.1

Type RM Length L Ch R = 1 ,13320.1 ,198.4,206.5,214.7
XS GIS Cut Line= 4
     1905062.818      663261.712     1905334.085      663589.403
     1905544.589       663689.23     1905902.662      663732.633
#Sta/Elev= 30
       0  857.08    38.7  844.46    67.7  833.39   154.7  795.78     203  769.35
     232  754.68   251.4  741.16   280.4  712.45     290  706.26   309.4   699.1
   328.7  693.96   348.1   691.1   454.5  690.63   483.6  684.95   503.1  684.69
   512.8  683.55   522.5  680.74   532.2  678.27   551.6   677.8   580.7  678.74
   590.4  682.04   609.8  689.04   629.3  692.77   677.9  709.36   746.1   728.7
   814.4  757.41   863.1  776.44   941.1  809.99   970.3   823.2  1019.1  851.76
#Mann= 3 , 0 , 0
       0     .05       0   522.5    .045       0   590.4     .07       0
Bank Sta=522.5,590.4
XS Rating Curve= 0 ,0
Exp/Cntr=0.3,0.1

Type RM Length L Ch R = 1 ,13113.5 ,152.6,151.4,150.4
XS GIS Cut Line= 4
     1904831.047      663223.518     1905306.742      663765.185
     1905431.742      663893.657     1905617.505      664076.817
#Sta/Elev= 30
       0  826.75    77.9  808.86   136.4   792.9   185.1  777.79   214.3  767.61
     263  748.59     341  715.12   360.4   709.9   457.9  695.32     565  695.65
   633.2  692.77   711.2  692.08   739.8  688.46   777.5  680.21   786.9   678.6
   805.8   677.8   843.5  678.12   871.8  681.84   890.7  685.86   919.5  697.36
   938.8  706.34   948.4  712.55   958.1  720.95   987.1  750.99   996.8   759.2
  1074.1  805.81  1083.7  813.04  1122.4  846.53    1132   853.3    1161  867.79
#Mann= 3 , 0 , 0
       0     .05       0   777.5    .045       0   871.8      .1       0
Bank Sta=777.5,871.8
XS Rating Curve= 0 ,0
Exp/Cntr=0.3,0.1

Type RM Length L Ch R = 1 ,12962.1 ,281.6,285.8,289.8
XS GIS Cut Line= 4
     1904635.735      663520.393     1905223.408      663897.563
     1905329.132      663997.919     1905522.887      664194.872
#Sta/Elev= 30
       0  799.98    88.5  794.11   186.9  791.97     236  788.68   265.6  784.55
   275.4  781.94   285.2  777.57   344.2  745.25   383.6  725.12   432.8  702.89
   442.6   699.4   452.4  697.17   531.1  691.24   629.4  689.63   688.5  686.44
   717.7  686.33   737.2  683.15   746.9  679.62   766.3   677.8   805.2  678.31
   824.6  683.54   891.7  707.11   901.2  711.17   910.8  716.55   929.8  729.68
   967.9  758.14  1034.6   804.9  1063.2  826.53  1082.2  842.46  1120.4  868.73
#Mann= 3 , 0 , 0
       0     .05       0   737.2    .045       0   824.6      .1       0
Bank Sta=737.2,824.6
XS Rating Curve= 0 ,0
Exp/Cntr=0.3,0.1

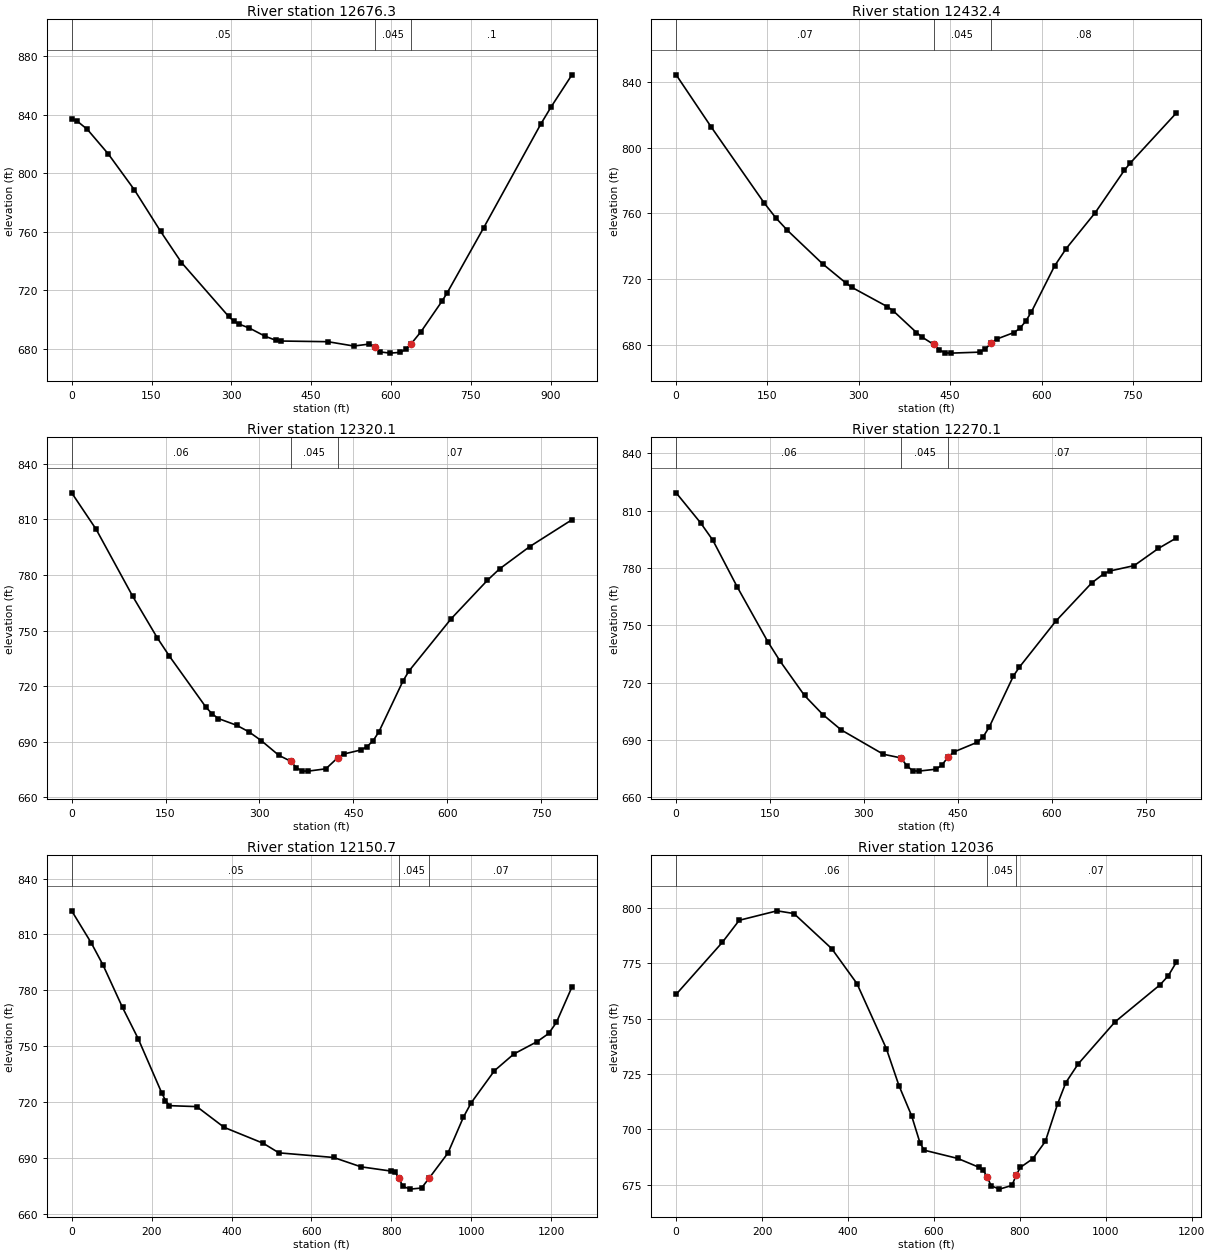
Type RM Length L Ch R = 1 ,12676.3 ,247.5,243.9,240.4
XS GIS Cut Line= 4
     1904698.235      663678.379     1905021.151      664074.212
     1905118.373      664207.893     1905302.401      664397.129
#Sta/Elev= 30
       0  836.79     9.8  835.64    29.5  829.82    68.8  813.08   117.9  788.58
     167  760.33   206.3  739.03   294.7  702.34   304.5  699.02   314.4  697.01
     334  694.29   363.5  688.71   383.1  686.03     393  685.46   481.4     685
   530.3  682.04   559.5   683.4   569.2  681.32   578.9  678.06   598.4   677.2
   617.8  677.73   627.5  679.73   637.2  683.23   656.7  691.95   695.7  712.53
   705.5  718.23   773.9  762.51   881.4  833.37     901  845.21   940.1  867.07
#Mann= 3 , 0 , 0
       0     .05       0   569.2    .045       0   637.2      .1       0
Bank Sta=569.2,637.2
XS Rating Curve= 0 ,0
Exp/Cntr=0.3,0.1

Type RM Length L Ch R = 1 ,12432.4 ,113.1,112.3,111.4
XS GIS Cut Line= 4
     1904531.134      663906.244     1904805.439      664203.119
     1904904.398      664303.813     1905128.356      664465.271
#Sta/Elev= 30
       0  844.15    57.7  812.38   144.4   766.4   163.6  757.28   182.8  749.63
   240.6  729.29   279.1  717.57   288.7  715.01   346.5  703.36   356.1  700.88
   394.6  687.61   404.2  684.72     423  680.33   432.4  676.95   441.8  675.21
   451.3  675.08   498.3  675.68   507.7  677.66   517.2  681.02   526.6  683.64
   554.9  687.61   564.4  690.18   573.9  694.38   583.5  700.23   621.5  728.08
   640.6  738.64   688.2  760.42   735.8  786.04   745.3   790.4   821.5  821.02
#Mann= 3 , 0 , 0
       0     .07       0     423    .045       0   517.2     .08       0
Bank Sta=423,517.2
XS Rating Curve= 0 ,0
Exp/Cntr=0.3,0.1

Type RM Length L Ch R = 1 ,12320.1 ,50,50,50.1
XS GIS Cut Line= 4
     1904465.162       664064.23     1904699.103      664256.504
     1904837.123      664384.108     1905100.144      664545.567
#Sta/Elev= 30
       0  824.21    39.1  804.54    97.7  768.33   136.8  746.03   156.3  736.11
   214.9   708.5   224.7  705.01   234.4  702.54   263.7  698.91   283.3  695.36
   302.8  690.69     331  682.73   349.8  679.57   359.2  675.97   368.6  674.26
     378   674.2   406.2  675.45     425  681.38   434.4  683.38   462.6  685.64
     472  687.43   481.4  690.47   490.8  695.29   529.4  722.77     539  728.19
   606.5  756.38   664.4  777.09   683.7   783.2   731.9  795.22   799.4  809.69
#Mann= 3 , 0 , 0
       0     .06       0   349.8    .045       0     425     .07       0
Bank Sta=349.8,425
XS Rating Curve= 0 ,0
Exp/Cntr=0.3,0.1

Type RM Length L Ch R = 1 ,12270.1 ,126.3,119.4,112.4
XS GIS Cut Line= 4
     1904423.495      664093.744     1904657.436      664286.018
     1904795.457      664413.622     1905058.478      664575.081
#Sta/Elev= 30
       0  819.32    39.1  803.59    58.6  794.53    97.7  770.01   146.5  741.38
   166.1  731.23   205.1  713.26   234.4  703.28   263.7  695.25     331  682.51
   359.2  680.58   368.6  676.52     378  673.84   387.4  673.67   415.6   674.7
     425  676.96   434.4  681.01   443.8   683.7   481.4  688.81   490.8  691.76
   500.4  696.78     539   723.5   548.6  728.14   606.5   752.1   664.4  772.28
   683.7  777.02   693.3  778.42   731.9  781.23   770.5   790.2   799.4   795.7
#Mann= 3 , 0 , 0
       0     .06       0   359.2    .045       0   434.4     .07       0
Bank Sta=359.2,434.4
XS Rating Curve= 0 ,0
Exp/Cntr=0.3,0.1

Type RM Length L Ch R = 1 ,12150.7 ,117.3,114.7,112.2
XS GIS Cut Line= 4
     1903840.162       664189.23     1904562.384      664402.771
     1904723.842       664479.16     1905022.453      664593.744
#Sta/Elev= 30
       0  822.71    48.9   805.5    78.2   793.7   127.2   770.8   166.3  754.07
     225  725.07   234.7  720.84   244.5  718.07     313  717.56   381.5  706.41
   479.3  697.86   518.4  692.73   655.3  690.24   723.8  685.22   800.1   682.9
   809.5  682.22   818.9  679.18   828.3  674.74   847.1  673.24   875.3  673.84
   894.1  679.08   941.4  692.63   980.2  711.96   999.6  719.62  1057.7  736.84
  1106.2  745.81  1164.4  752.44  1193.4  756.83  1212.8   762.8  1251.6   781.8
#Mann= 3 , 0 , 0
       0     .05       0   818.9    .045       0   894.1     .07       0
Bank Sta=818.9,894.1
XS Rating Curve= 0 ,0
Exp/Cntr=0.3,0.1

Type RM Length L Ch R = 1 ,12036   ,241.2,231.9,222.6
XS GIS Cut Line= 4
     1903852.314      664612.841     1904499.884       664510.41
     1904692.592      664576.383     1904992.939      664630.202
#Sta/Elev= 30
       0  761.06   107.6  784.58   146.8  794.52   234.8   798.8     274  797.58
   362.1  781.71   420.8  765.92   489.3  736.49   518.6   719.8     548   706.2
   567.6   693.9   577.3  690.61   655.6  686.87   704.1  682.95   713.8  681.82
   723.5  678.69   733.2  674.51   752.6  673.01   781.7   674.7   791.4  679.32
   801.1  682.82   830.2  686.76   859.3  694.56   887.9  711.56     907  721.16
   935.6  729.56  1021.4  748.58  1126.3  765.36  1145.4  769.42  1164.4  775.62
#Mann= 3 , 0 , 0
       0     .06       0   723.5    .045       0   791.4     .07       0
Bank Sta=723.5,791.4
XS Rating Curve= 0 ,0
Exp/Cntr=0.3,0.1

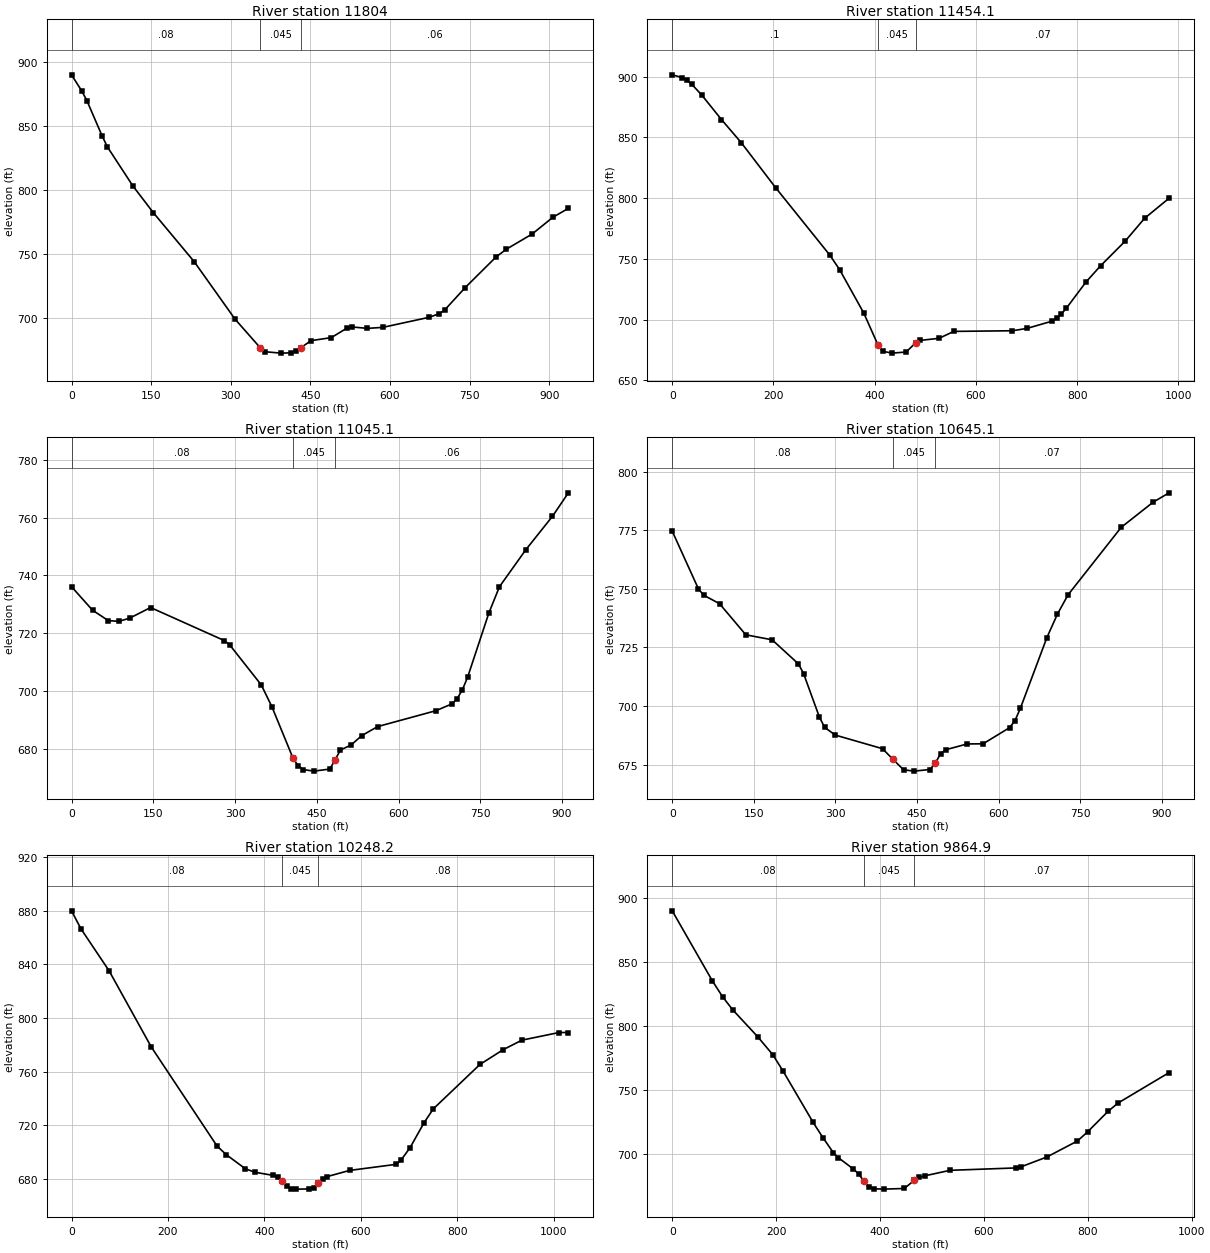
Type RM Length L Ch R = 1 ,11804   ,365.2,349.9,334.7
XS GIS Cut Line= 4
     1904097.106      664789.924     1904413.078      664756.938
     1904593.634      664741.313     1905027.662      664690.966
#Sta/Elev= 30
       0  889.89    19.2   877.4    28.9  869.86    57.8  842.12    67.4  833.82
   115.5  803.34     154  782.48     231  744.29   308.1  699.39   355.8  676.97
   365.4  673.99     394  672.93   413.1  673.14   422.6  674.31   432.2   677.2
   451.2  682.67   489.4  685.02   518.3   692.3     528  693.36   557.2  692.23
   586.3     693   673.7  700.86   693.1  703.75   702.8   706.5   741.7  724.07
   799.9  747.98   819.3  753.98   867.9  765.84   906.7  778.82   935.9  785.78
#Mann= 3 , 0 , 0
       0     .08       0   355.8    .045       0   432.2     .06       0
Bank Sta=355.8,432.2
XS Rating Curve= 0 ,0
Exp/Cntr=0.3,0.1

Type RM Length L Ch R = 1 ,11454.1 ,415,409.1,404.1
XS GIS Cut Line= 4
     1904413.527      665397.582     1904606.655      665093.744
     1904728.182      664978.726     1905118.807      664746.521
#Sta/Elev= 30
       0  901.54    19.5  899.28    29.2  896.87    38.9  893.62    58.4  884.86
    97.3  864.72   136.2   845.8   204.3  808.65   311.4  753.12   330.8  741.15
   378.6  705.31   406.5  679.22   415.8  673.93   434.4   672.4   462.3  673.32
   480.9  680.85   490.2  682.89   527.4   684.6   556.4  690.29   672.4  690.83
   701.4  692.79   749.7  698.62   759.4  701.06   769.1  704.72   778.7  709.29
   817.4  730.83   846.4   744.3   894.8  764.49   933.4  783.39   981.8  799.94
#Mann= 3 , 0 , 0
       0      .1       0   406.5    .045       0   480.9     .07       0
Bank Sta=406.5,480.9
XS Rating Curve= 0 ,0
Exp/Cntr=0.3,0.1

Type RM Length L Ch R = 1 ,11045.1 ,401.3,400,395.2
XS GIS Cut Line= 3
     1904763.815      665657.467     1905001.799      665270.079
     1905258.661      664892.109
#Sta/Elev= 30
       0  736.12    38.7  727.94    67.7  724.34    87.1  724.12   106.4  725.18
   145.1  728.89   280.5  717.43   290.2  715.96   348.2  702.07   367.6  694.55
   406.3  676.74     416     674   425.6  672.72     445   672.2   474.1  672.92
   483.8   676.2   493.5  679.52     513  681.25   532.4  684.49   561.6  687.63
   668.6  693.14   697.7  695.47   707.4  697.26   717.2   700.4   726.9  704.81
   765.8  727.02   785.2  736.11   833.8  748.98   882.5  760.51   911.6  768.64
#Mann= 3 , 0 , 0
       0     .08       0   406.3    .045       0   483.8     .06       0
Bank Sta=406.3,483.8
XS Rating Curve= 0 ,0
Exp/Cntr=0.3,0.1

Type RM Length L Ch R = 1 ,10645.1 ,410.7,396.9,384.8
XS GIS Cut Line= 3
     1905142.781      665855.772     1905355.328      665454.301
     1905524.414      665027.477
#Sta/Elev= 30
       0  774.66    48.3  749.94      58   747.3      87  743.68   135.3   730.4
   183.6  728.27     232  717.99   241.6  713.78   270.6  695.24   280.3  690.87
   299.6   687.6   386.6  681.78   405.9  677.22   425.3  672.77   444.6   672.2
   473.8  672.89   483.6  675.59   493.3  679.61   503.1  681.35   542.2   683.8
   571.5  683.87   620.3  690.78   630.1  693.77   639.9  698.94   688.7  729.16
   708.2  739.27   727.8  747.51   825.4  776.28   884.1  787.03   913.4  791.02
#Mann= 3 , 0 , 0
       0     .08       0   405.9    .045       0   483.6     .07       0
Bank Sta=405.9,483.6
XS Rating Curve= 0 ,0
Exp/Cntr=0.3,0.1

Type RM Length L Ch R = 1 ,10248.2 ,390.8,383.3,377.1
XS GIS Cut Line= 4
     1905701.707      666077.685     1905727.748      665669.699
     1905705.263      665503.305     1905631.234      665055.591
#Sta/Elev= 30
       0  879.97    19.5  866.58    77.9  835.23   165.5   778.3   301.8  704.37
   321.2  697.87   360.2   687.5   379.6  684.86   418.1  682.47   427.5     681
   436.8  677.96   446.1  674.26   455.5  672.29   464.8   672.2   492.8  672.32
   502.1  673.28   511.4  676.64   520.8  679.93   530.1  681.54   576.7  686.16
   673.3   690.7   682.9  693.62   702.2  703.14   731.2  721.77   750.5  732.16
   847.1  765.28   895.3   776.3     934   783.4  1011.2  789.12  1030.5   789.1
#Mann= 3 , 0 , 0
       0     .08       0   436.8    .045       0   511.4     .08       0
Bank Sta=436.8,511.4
XS Rating Curve= 0 ,0
Exp/Cntr=0.3,0.1

Type RM Length L Ch R = 1 ,9864.9  ,386.1,381.5,376.2
XS GIS Cut Line= 4
     1906222.106      665838.969     1906085.387       665528.64
       1906016.3      665388.288     1905734.299      665023.681
#Sta/Elev= 30
       0  889.96    77.5  834.99    96.9  822.77   116.3  812.57   164.7  791.38
   193.8  777.28   213.2  764.69   271.3  724.38   290.7  712.12     310  700.85
   319.7  696.81   348.9  687.88   358.7  684.13   368.4  678.81   378.2  674.23
     388  672.49   407.6   672.2   446.7  672.71   466.2  679.15     476  681.41
   485.8  682.57   534.8  686.91   662.3   688.8   672.1  689.74   721.1  697.32
     780  709.83   799.6  716.98   838.8  732.98   858.4   739.6   956.5  763.37
#Mann= 3 , 0 , 0
       0     .08       0   368.4    .045       0   466.2     .07       0
Bank Sta=368.4,466.2
XS Rating Curve= 0 ,0
Exp/Cntr=0.3,0.1

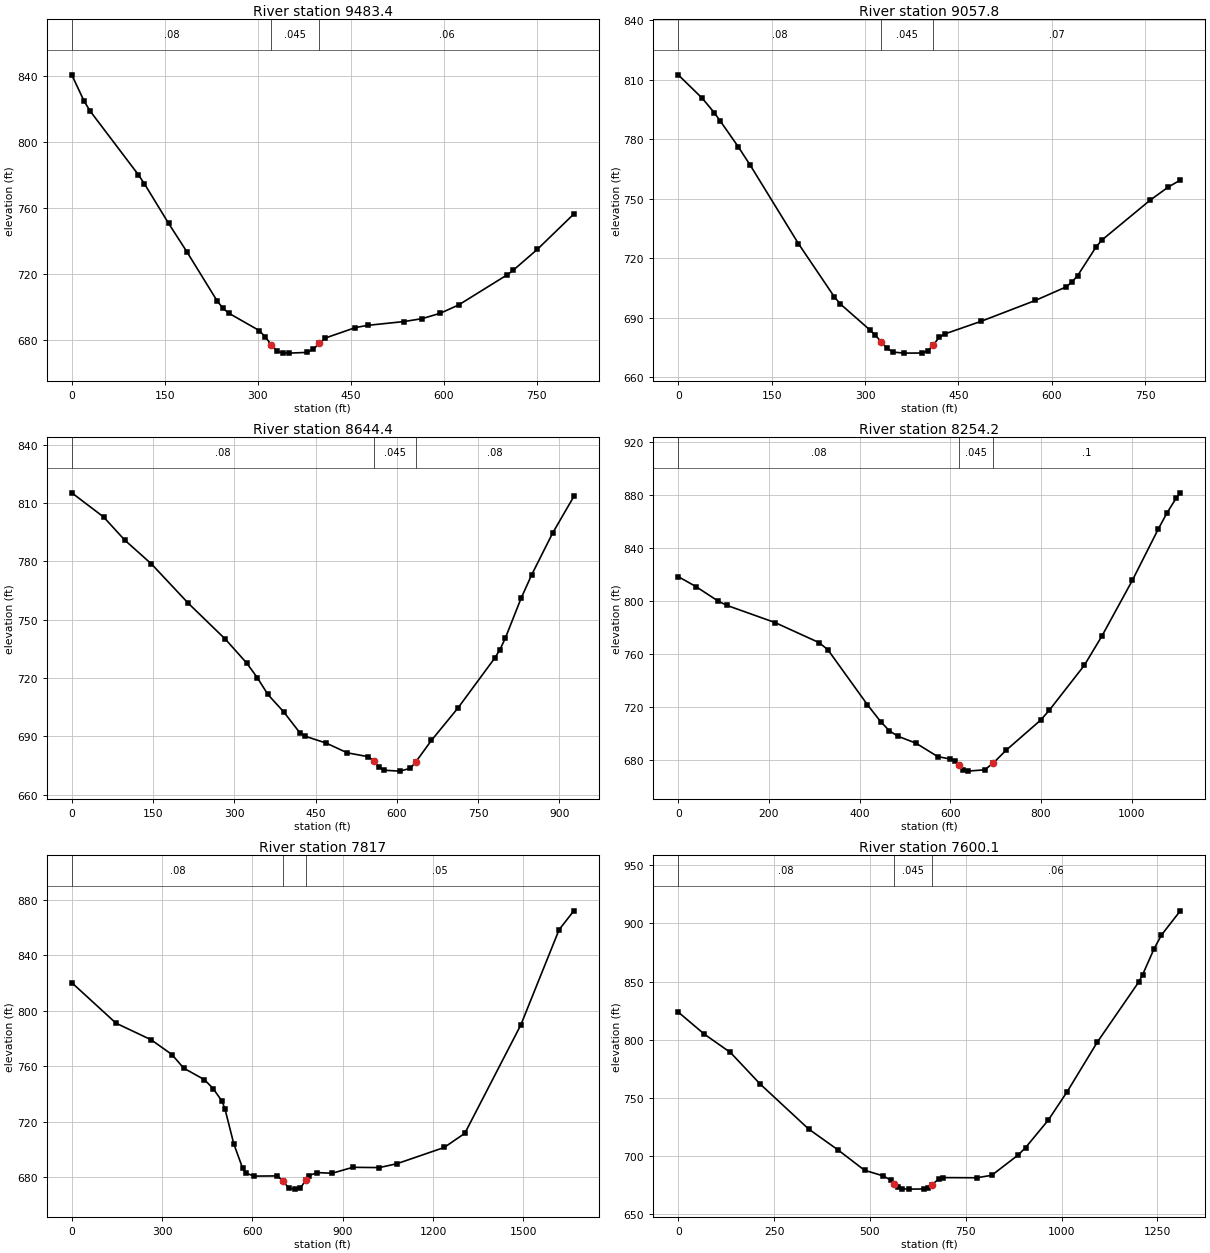
Type RM Length L Ch R = 1 ,9483.4  ,429.3,425.6,421.7
XS GIS Cut Line= 4
     1906400.057      665400.601     1906250.318      665183.587
     1906141.811       665059.89     1905855.353      664808.153
#Sta/Elev= 30
       0  840.45    19.5  824.85    29.3  818.69   107.4  780.04   117.2  774.54
   156.2   750.6   185.5  733.53   234.4  703.77   244.1   699.2   253.9   696.2
   302.4  685.82   312.1  681.93   321.7  677.36   331.4   673.2   341.1  672.29
   350.8   672.2   379.8  672.66   389.5  674.62   399.2  678.07   408.8  681.33
   457.5  687.66   477.1  688.99   535.8  691.29   565.1  693.05   594.4  696.34
   623.8  701.32     702  719.51   711.8  722.28   750.9     735   809.6  756.31
#Mann= 3 , 0 , 0
       0     .08       0   321.7    .045       0   399.2     .06       0
Bank Sta=321.7,399.2
XS Rating Curve= 0 ,0
Exp/Cntr=0.3,0.1

Type RM Length L Ch R = 1 ,9057.8  ,399.1,413.4,427.8
XS GIS Cut Line= 4
     1906584.519      664973.084     1906395.717      664779.942
      1906278.53      664673.605     1905944.328      664496.956
#Sta/Elev= 30
       0  812.51    38.6   800.7    57.9  793.41    67.5  789.22    96.5   776.2
   115.8  766.86   192.9  727.47   250.8  700.54   260.4  696.96   307.3  684.03
   316.6   681.3   325.9  677.88   335.2  674.72   344.6  672.73   363.2   672.2
   391.1  672.26   400.4  673.25   409.7  676.32     419  680.13   428.3  681.88
   486.5  688.25   573.7  698.77   622.2  705.47   631.9  707.85   641.6  711.33
   670.6  725.49   680.3  729.17   757.9   749.3     787  755.93   806.4  759.43
#Mann= 3 , 0 , 0
       0     .08       0   325.9    .045       0   409.7     .07       0
Bank Sta=325.9,409.7
XS Rating Curve= 0 ,0
Exp/Cntr=0.3,0.1

Type RM Length L Ch R = 1 ,8644.4  ,378.8,390.2,401.7
XS GIS Cut Line= 4
     1906616.203      664957.893     1906558.912      664491.747
     1906519.415       664291.66     1906465.162      664044.265
#Sta/Elev= 30
       0  815.32    58.7  802.91    97.8  790.99   146.8   778.8   215.3  758.44
   283.8  739.93   322.9  727.72   342.5  720.22     362  711.56   391.4  702.54
   420.7  691.97   430.5   690.1   469.6  686.54   508.5  681.53   547.4  679.52
   557.1  677.45   566.8  674.29   576.5  672.56   605.6   672.1     625  673.54
   634.8  676.72   663.9  687.89   712.6  704.46   780.8  730.25   790.5  734.64
   800.2  740.41   829.5  761.05     849  773.11   887.9  794.69   926.9  813.46
#Mann= 3 , 0 , 0
       0     .08       0   557.1    .045       0   634.8     .08       0
Bank Sta=557.1,634.8
XS Rating Curve= 0 ,0
Exp/Cntr=0.3,0.1

Type RM Length L Ch R = 1 ,8254.2  ,410.7,437.2,463.7
XS GIS Cut Line= 4
     1906660.474      664957.893     1906894.163      664456.534
     1906959.953       664249.56     1907025.057      663918.831
#Sta/Elev= 30
       0  818.41    38.8  810.95    87.3   800.1   106.8  796.77   213.5  783.74
   310.5  768.62     330  763.25   417.3  721.71   446.4  708.98   465.8  701.98
   485.2  697.83     524  692.76     572  682.63   600.4  680.66   609.8  679.09
   619.2  675.87   628.7  672.66   638.1   671.6   675.9  672.58   694.8  677.69
   723.1  687.34   799.2  710.04   818.5  717.61   895.5  751.39     934  773.26
  1001.5  815.51  1059.2  854.59  1078.5  866.78  1097.8  877.38  1107.4  881.66
#Mann= 3 , 0 , 0
       0     .08       0   619.2    .045       0   694.8      .1       0
Bank Sta=619.2,694.8
XS Rating Curve= 0 ,0
Exp/Cntr=0.3,0.1

Type RM Length L Ch R = 1 ,7817    ,216.8,216.8,216.4
XS GIS Cut Line= 4
     1906668.287      664981.331     1907130.092      664558.153
     1907318.894      664540.792     1907653.096      663757.372
#Sta/Elev= 30
       0  820.31   146.8  791.15   264.2   779.1   332.8  768.51   371.9  758.71
   440.4  750.48   469.8  743.98   499.1  734.94   508.9   729.3   538.3  704.09
   567.6  686.66   577.4  683.13   606.8  680.99   683.2  681.12   702.2  677.36
   721.2  672.16   740.1   671.6   759.1  672.21     778  678.41   787.5  681.39
     816   683.5   864.9  683.03   933.4  687.31  1021.6  687.11  1080.3  689.92
  1236.9  701.59  1305.5  711.79  1491.5  789.83  1618.8  858.49  1667.7  872.05
#Mann= 3 , 0 , 0
       0     .08       0   702.2    .045       0     778     .05       0
Bank Sta=702.2,778
XS Rating Curve= 0 ,0
Exp/Cntr=0.3,0.1

Type RM Length L Ch R = 1 ,7600.1  ,547.2,555.1,567.1
XS GIS Cut Line= 4
     1906649.189      665045.567      1907099.71      664757.806
     1907303.703      664742.615      1907872.28      664692.702
#Sta/Elev= 30
       0  823.75      68  804.78   136.1  789.04   213.8  761.88   340.2  723.26
   417.9  705.05     486  687.82   534.6  682.99   554.1  679.41   563.8  676.31
   573.5   673.3   583.3  671.89   601.4   671.6   641.7  671.74   651.5   672.7
   661.2  675.14   680.7  680.67   690.4  681.51   778.5  681.36   817.9  683.48
   886.8  700.92   906.4  707.36   965.5  730.95  1014.7  755.32  1093.4  797.95
  1201.6  849.66  1211.5  855.81    1241  877.83  1260.7  889.96  1309.9  910.75
#Mann= 3 , 0 , 0
       0     .08       0   563.8    .045       0   661.2     .06       0
Bank Sta=563.8,661.2
XS Rating Curve= 0 ,0
Exp/Cntr=0.3,0.1

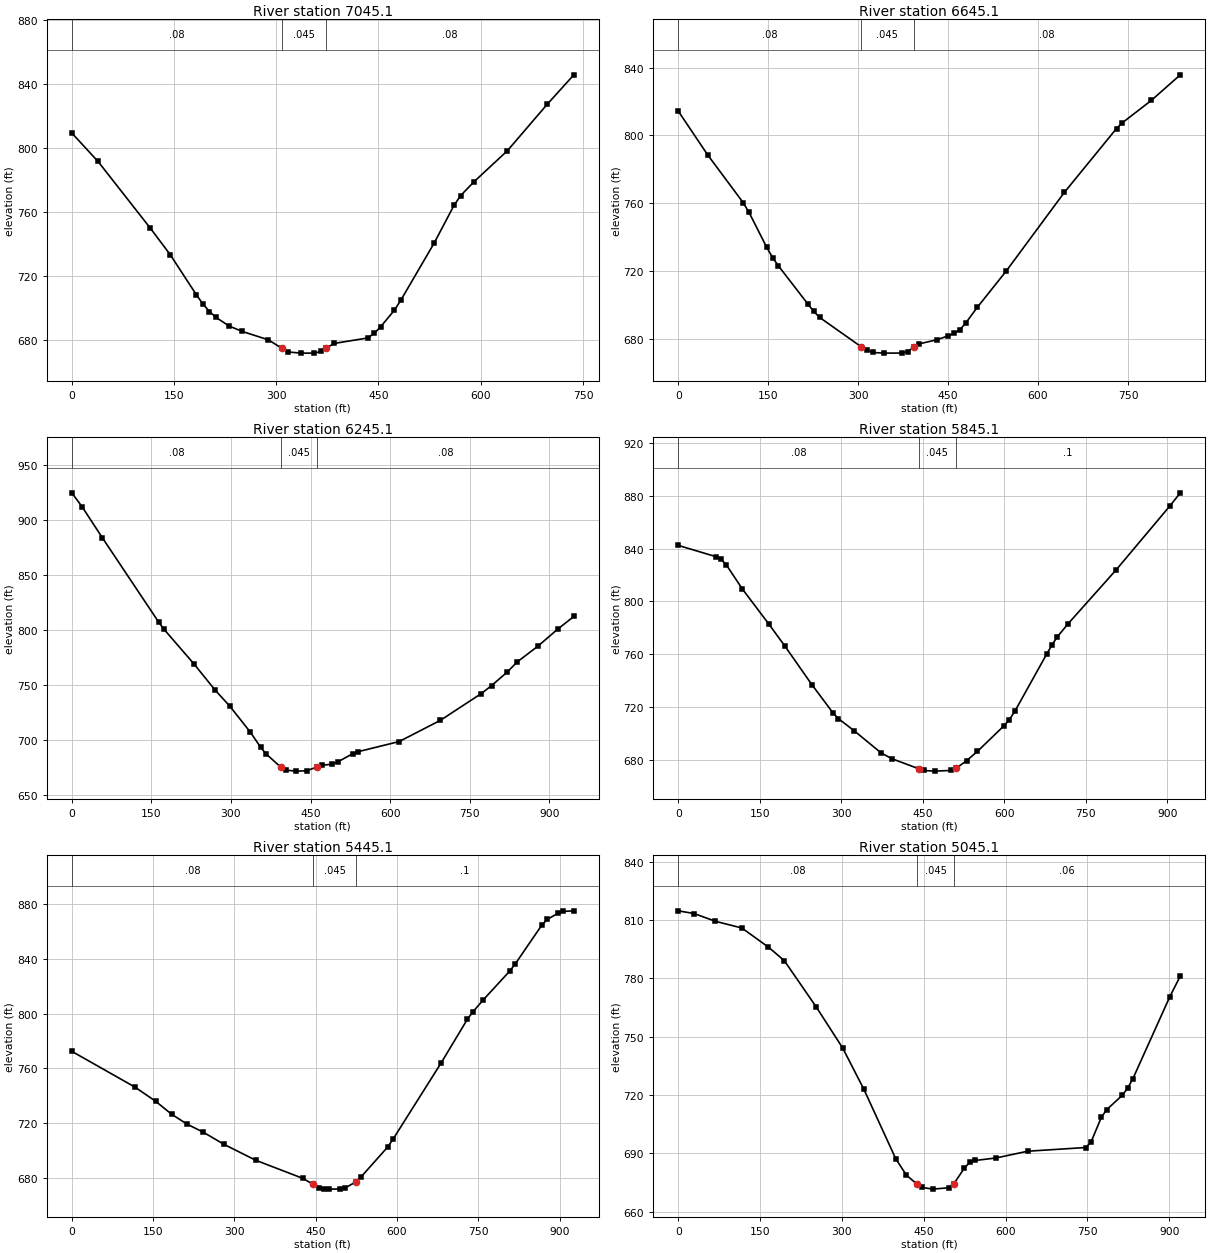
Type RM Length L Ch R = 1 ,7045.1  ,406.4,400,392.4
XS GIS Cut Line= 3
     1906625.795      665173.236      1906979.61      665265.231
     1907317.557      665418.276
#Sta/Elev= 30
       0  809.13    38.5  791.35   115.4  749.58   144.3   733.2   182.8  708.07
   192.4  702.31     202  697.58   211.6   693.9   230.9  688.52   250.1  685.15
   288.6  679.88   307.9   674.7   317.5  672.32   336.7   671.6     356  671.61
   365.6  672.68   373.1  674.78   385.1  677.66   433.9  681.05   443.7  683.92
   453.4  688.22     473  698.24   482.7  704.61   531.6  740.31   560.8  763.91
   570.6  770.05   590.1  778.66   638.9  797.95   697.5  827.04   736.6  845.46
#Mann= 3 , 0 , 0
       0     .08       0   307.9    .045       0   373.1     .08       0
Bank Sta=307.9,373.1
XS Rating Curve= 0 ,0
Exp/Cntr=0.3,0.1

Type RM Length L Ch R = 1 ,6645.1  ,411.1,400,389.1
XS GIS Cut Line= 3
     1906432.653      665620.285     1906786.348      665614.886
     1907267.535       665661.69
#Sta/Elev= 30
       0  814.41    49.1  788.54   108.1  760.46   117.9  754.71   147.4  734.12
   157.2     728     167   723.1   216.2  700.56     226  696.18   235.8  692.65
   304.6  675.48   314.4  673.33   324.3  671.99   343.9   671.6   373.1  671.64
   382.7  672.55   392.4  674.99   402.1  677.08   431.1  679.47   450.4  681.82
   460.1  683.25   469.8  685.47   479.4  689.36   498.8  698.67   547.1  720.11
   643.8   766.4   730.8   804.1   740.5  807.48   788.8  820.67   837.2  835.78
#Mann= 3 , 0 , 0
       0     .08       0   304.6    .045       0   392.4     .08       0
Bank Sta=304.6,392.4
XS Rating Curve= 0 ,0
Exp/Cntr=0.3,0.1

Type RM Length L Ch R = 1 ,6245.1  ,400.7,400,394.9
XS GIS Cut Line= 3
     1906467.375      666199.712     1906832.028      665984.505
     1907308.542      665769.237
#Sta/Elev= 30
       0  924.99    19.2  912.49    57.7  884.03   163.6  807.43   173.2  801.11
     231  768.82   269.4  745.81   298.3  730.48   336.8  706.94   356.1  693.24
   365.7  687.51   394.6  674.94   404.2  672.41   423.4   671.6   442.8   671.9
   462.2  675.43   471.8   676.9   491.2  678.06   500.9  679.86   529.9  687.58
   539.6  689.29   617.1  698.54   694.6   717.8     772  742.26   791.4  749.54
   820.4  761.67   839.8   771.1   878.5  785.35   917.2  801.42   946.3   812.4
#Mann= 3 , 0 , 0
       0     .08       0   394.6    .045       0   462.2     .08       0
Bank Sta=394.6,462.2
XS Rating Curve= 0 ,0
Exp/Cntr=0.3,0.1

Type RM Length L Ch R = 1 ,5845.1  ,386.6,400,413.5
XS GIS Cut Line= 3
     1906726.502      666494.373     1907129.212      666248.668
     1907497.718      665986.853
#Sta/Elev= 30
       0  842.36    68.8   833.9    78.6  831.95    88.4  827.68   117.9  809.44
   167.1  782.64   196.6  765.97   245.7  737.12     285  715.54   294.8  711.28
   324.3  701.94   373.5  685.31   393.1  681.01   442.3  673.43   452.1  672.08
   471.8   671.6   501.2  672.11   511.1  673.67   530.7  679.54   550.4  686.48
   599.5  705.96   609.3  710.62   619.2  716.76   678.1  760.28   687.9  767.16
   697.8  773.36   717.4  783.13   805.9  823.92   904.1  871.94   923.8  882.12
#Mann= 3 , 0 , 0
       0     .08       0   442.3    .045       0   511.1      .1       0
Bank Sta=442.3,511.1
XS Rating Curve= 0 ,0
Exp/Cntr=0.3,0.1

Type RM Length L Ch R = 1 ,5445.1  ,386.6,400,412
XS GIS Cut Line= 3
     1906755.774      666606.472     1907229.909      666627.985
     1907681.377      666620.081
#Sta/Elev= 30
       0  772.46   116.2  746.36     155  735.84     184  726.45   213.1  719.07
   242.2  713.34   280.9  704.36     339  692.79   426.2  679.48   445.6  674.99
   455.2  672.79   464.9  671.72   474.6   671.6   494.2  671.69   504.1  672.42
   523.7  676.82   533.5  680.45   582.6  702.36   592.4     708   680.8  763.59
   729.8   795.9   739.6  801.18   759.3  810.21   808.4  831.41   818.2  836.48
   867.3  864.94   877.1  868.98   896.7  873.44   906.5  874.85   926.2  875.29
#Mann= 3 , 0 , 0
       0     .08       0   445.6    .045       0   523.7      .1       0
Bank Sta=445.6,523.7
XS Rating Curve= 0 ,0
Exp/Cntr=0.3,0.1

Type RM Length L Ch R = 1 ,5045.1  ,401.4,400,398.1
XS GIS Cut Line= 3
     1906715.624      666715.353     1907082.135      666988.603
     1907483.995      667218.888
#Sta/Elev= 30
       0  814.68    29.2  813.28    68.1   809.3   116.7  805.84   165.4     796
   194.5  789.04   252.9  765.27   301.5  744.13   340.4  722.86   398.8  687.16
   418.2  678.79   437.7  674.14   447.4  672.46   466.8   671.6   495.8   672.3
   505.4  674.46   524.7  682.48   534.4  685.43     544  686.32   582.6  687.62
   640.5  691.09   746.6  692.99   756.3  695.58   775.6  708.55   785.2  712.42
   814.2  719.92   823.8  723.54   833.5  728.46     901   770.5   920.3  781.16
#Mann= 3 , 0 , 0
       0     .08       0   437.7    .045       0   505.4     .06       0
Bank Sta=437.7,505.4
XS Rating Curve= 0 ,0
Exp/Cntr=0.3,0.1