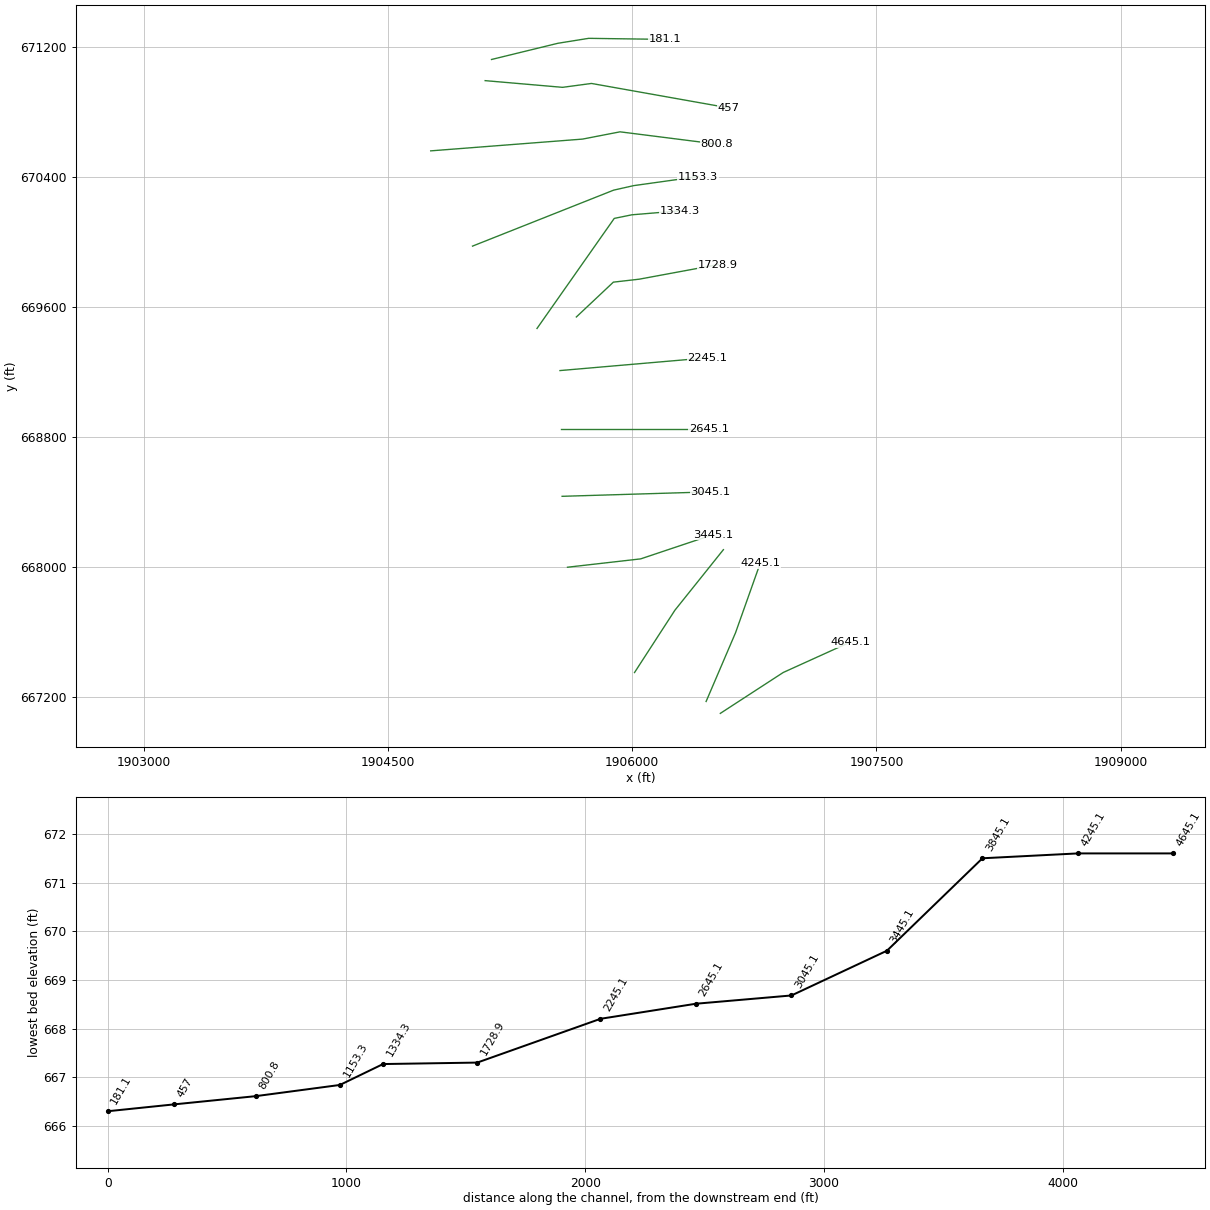
HEC-RAS study HenryFork.prj: HenryFork

--- HenryFork.g01 (geometry) --- (continued)

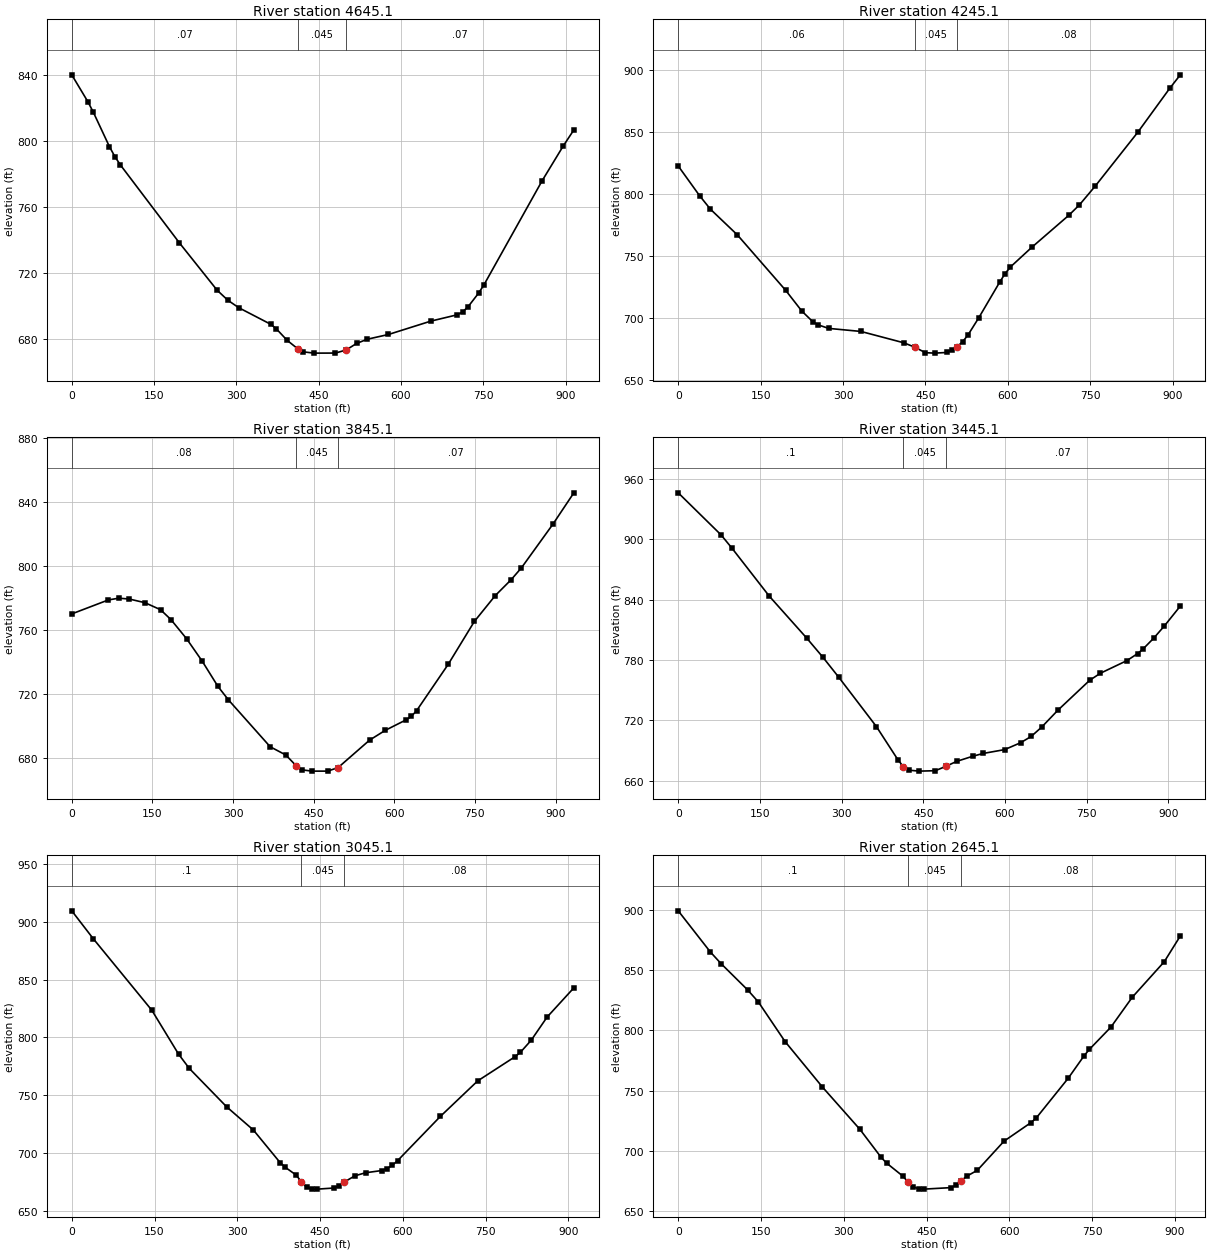
Type RM Length L Ch R = 1 ,4645.1  ,386.7,400,418.2
XS GIS Cut Line= 3
     1906540.987       667098.46     1906927.542      667350.261
     1907340.735      667538.092
#Sta/Elev= 30
       0   839.9    29.4  823.62    39.3  817.28    68.7  796.44    78.5  790.48
    88.3  785.55   196.3  738.23     265  709.63   284.6  703.56   304.3  699.09
   363.2  688.96     373  686.25   392.6  679.34   412.3  674.12   422.1  672.37
   441.7   671.6   480.6  671.64     500  673.48   519.3  677.48   538.6     680
   577.2  682.87   654.5  690.96   702.8  694.79   712.4  696.53   722.1  699.52
   741.4  707.81     751  712.69   857.3   775.8   895.9  796.89   915.2  806.59
#Mann= 3 , 0 , 0
       0     .07       0   412.3    .045       0     500     .07       0
Bank Sta=412.3,500
XS Rating Curve= 0 ,0
Exp/Cntr=0.3,0.1

Type RM Length L Ch R = 1 ,4245.1  ,403.9,400,392.3
XS GIS Cut Line= 3
      1906453.61      667171.559     1906634.212      667594.347
     1906785.944      668022.676
#Sta/Elev= 30
       0  822.61    39.1  798.52    58.7  787.71   107.6  767.04   195.6  722.29
     225  705.57   244.6  697.12   254.3  694.47   273.9  691.56   332.6   689.1
   410.8  679.93   430.4  676.46     450  671.95   467.2   671.6   488.8  672.13
   498.4  673.96   508.1   676.9   517.8  680.81   527.4  686.11   546.8  699.81
   585.4  728.95   595.1  735.74   604.8   741.1   643.4  756.85   711.1   782.8
   730.5  791.23   759.5  806.51   836.8  849.86   894.8  885.21   914.2  896.19
#Mann= 3 , 0 , 0
       0     .06       0   430.4    .045       0   508.1     .08       0
Bank Sta=430.4,508.1
XS Rating Curve= 0 ,0
Exp/Cntr=0.3,0.1

Type RM Length L Ch R = 1 ,3845.1  ,419.9,400,387.2
XS GIS Cut Line= 3
     1906013.816      667349.885     1906261.736      667733.205
     1906559.815      668106.261
#Sta/Elev= 30
       0  769.92      68  778.66    87.4  779.75   106.8  779.24     136  776.95
   165.1  772.55   184.6  766.32   213.7  754.33   242.8  740.25     272  724.48
   291.4  716.12   369.1  686.76   398.2  681.59   417.6  674.81   427.4  672.33
   446.8   671.5     476   671.5   495.5  673.72     554   690.9   583.2  697.03
   622.2  703.64   631.9  705.83   641.7  709.45   700.1  738.27   748.9  765.18
   787.8  781.38   817.1  791.24   836.6   798.8     895  826.05     934  845.71
#Mann= 3 , 0 , 0
       0     .08       0   417.6    .045       0   495.5     .07       0
Bank Sta=417.6,495.5
XS Rating Curve= 0 ,0
Exp/Cntr=0.3,0.1

Type RM Length L Ch R = 1 ,3445.1  ,401.9,400,393.3
XS GIS Cut Line= 3
     1905602.124      667998.163     1906051.646      668049.552
      1906496.72      668198.866
#Sta/Elev= 30
       0  946.31    78.7  904.45    98.4  891.44   167.2  843.56   236.1  801.75
   265.6  782.86   295.1   762.7   363.9  713.88   403.3  680.96   413.1  674.18
   422.9  670.56   442.6   669.6     472  670.02   491.6  674.39   511.1  679.27
   540.5  684.35     560  687.19   599.2  690.97   628.5   697.8     648  704.06
   667.6   713.5     697  730.11   755.6  759.97   775.2  766.93   824.1  779.56
   843.7  786.54   853.4     791     873  801.76   892.6  813.94   921.9  833.71
#Mann= 3 , 0 , 0
       0      .1       0   413.1    .045       0   491.6     .07       0
Bank Sta=413.1,491.6
XS Rating Curve= 0 ,0
Exp/Cntr=0.3,0.1

Type RM Length L Ch R = 1 ,3045.1  ,400.7,400,399.3
XS GIS Cut Line= 3
     1905568.983      668434.703     1906023.777      668448.382
     1906478.571      668462.061
#Sta/Elev= 30
       0   909.6    38.7  885.61   145.2  823.48   193.6  785.52     213  773.17
   280.7  739.94   329.2  719.82   377.6  691.67   387.2  687.49   406.6  680.88
   416.3  674.99     426  670.19   435.6  668.72   445.3  668.68   474.4  669.62
     484  671.36   493.7  674.76   513.1   680.2   532.4  682.84   561.5  684.75
   571.2  686.38   580.8  689.21   590.5   693.3     668   731.6   735.7  762.36
   803.5  783.33   813.2  787.14   832.6  797.51   861.6  817.66     910  842.92
#Mann= 3 , 0 , 0
       0      .1       0   416.3    .045       0   493.7     .08       0
Bank Sta=416.3,493.7
XS Rating Curve= 0 ,0
Exp/Cntr=0.3,0.1

Type RM Length L Ch R = 1 ,2645.1  ,398.1,400,401.9
XS GIS Cut Line= 3
      1905559.09      668848.237      1906014.09      668848.237
      1906469.09      668848.237
#Sta/Elev= 30
       0  898.95    58.1  864.95    77.4  855.32   125.8  833.46   145.2   823.5
   193.6  790.73   261.4  753.01   329.2  718.06   367.9  694.73   377.6  690.08
   406.6  679.46   416.3  674.59     426  670.45   435.6  668.78   445.3  668.51
   493.7  669.74   503.4  671.59   513.1  675.58   522.8  679.16   542.1   684.1
   590.5  708.23   638.9  723.46   648.6  727.25   706.7  760.26   735.8  779.06
   745.4  784.33   784.2  802.66   822.9  827.38     881  856.86     910  878.14
#Mann= 3 , 0 , 0
       0      .1       0   416.3    .045       0   513.1     .08       0
Bank Sta=416.3,513.1
XS Rating Curve= 0 ,0
Exp/Cntr=0.3,0.1

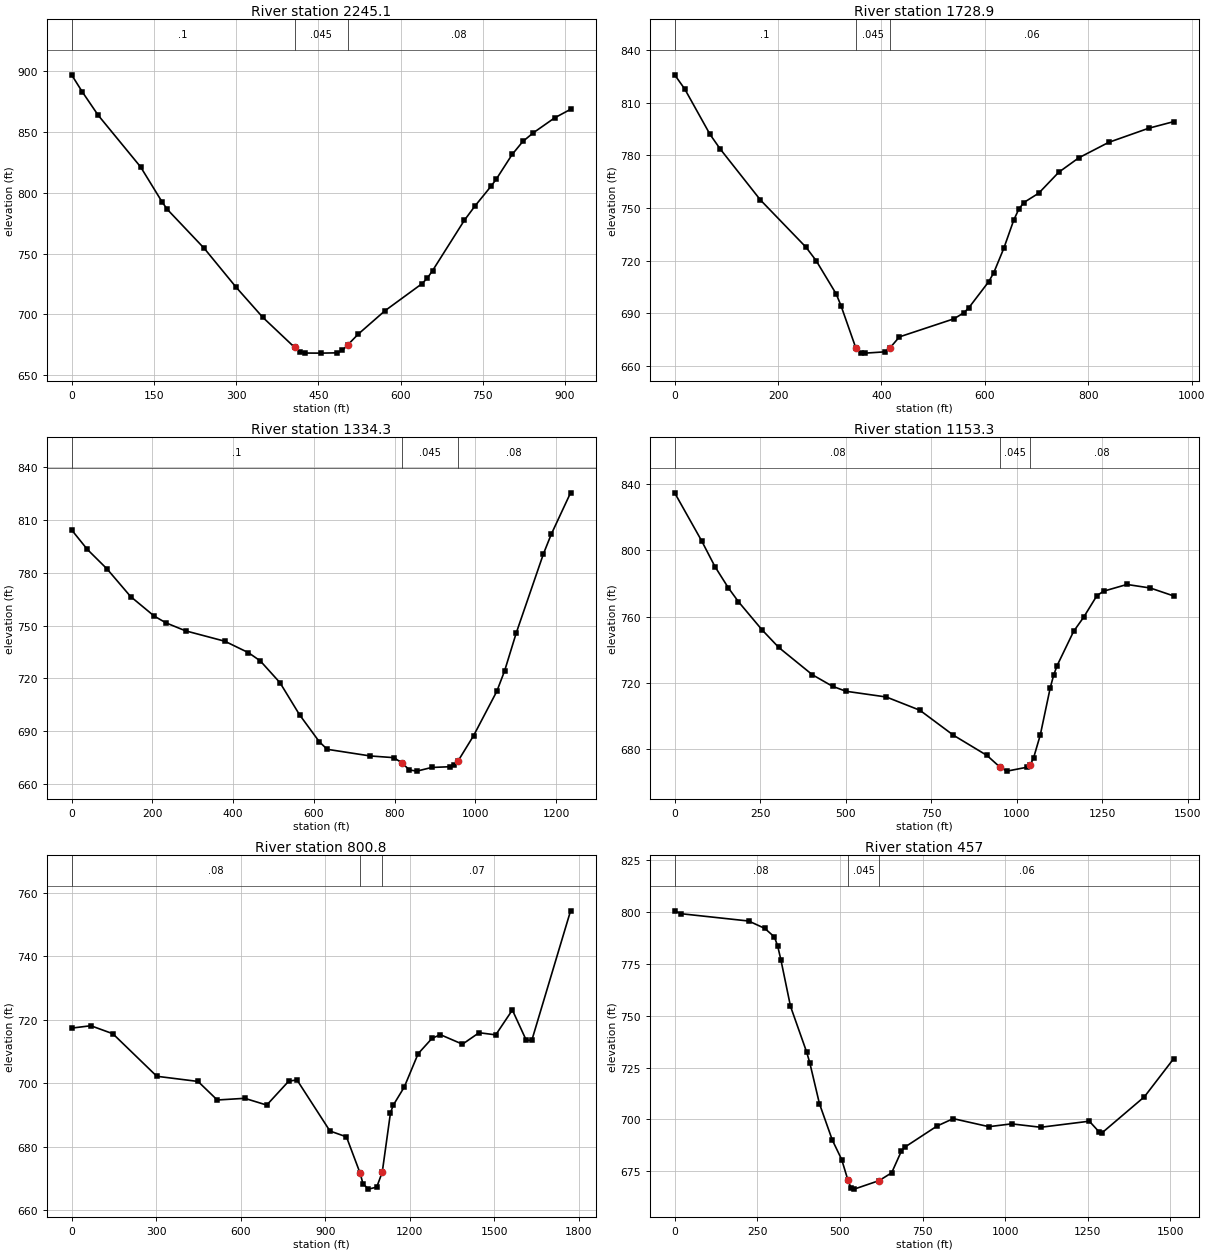
Type RM Length L Ch R = 1 ,2245.1  ,515.6,516.2,516.9
XS GIS Cut Line= 3
     1905556.022      669208.729     1906009.322       669248.03
     1906462.621      669287.332
#Sta/Elev= 30
       0  897.22    19.4  883.25    48.4  863.99   125.8  821.45   164.6  792.92
   174.3  786.58     242  754.35   300.1  722.38   348.5  697.73   406.6  672.97
   416.3  669.41     426  668.27     455   668.2     484  668.44   493.7   670.4
   503.4  674.89   522.8  683.86   571.2  702.97   638.9  725.29   648.6  729.83
   658.3  736.08   716.4  777.58   735.7  789.29   764.8  805.45   774.5  811.36
   803.5  831.71   822.9  842.37   842.2  849.55     881  861.82     910  868.84
#Mann= 3 , 0 , 0
       0      .1       0   406.6    .045       0   503.4     .08       0
Bank Sta=406.6,503.4
XS Rating Curve= 0 ,0
Exp/Cntr=0.3,0.1

Type RM Length L Ch R = 1 ,1728.9  ,392.4,394.6,396.6
XS GIS Cut Line= 4
     1905656.438      669538.687     1905883.868      669753.097
     1906042.722      669771.326     1906527.097       669861.17
#Sta/Elev= 30
       0  825.85    19.5  817.78    68.4  791.92    87.9  783.68     166  754.52
     254  727.66   273.5  720.07   312.6  700.96     322  694.13   350.2  670.44
   359.6  667.49     369   667.3   406.6  668.03     416  670.12   434.8  676.56
   540.1  686.84   559.4  690.28   569.1  693.19   607.7  708.09   617.4  713.22
   636.7  727.04     656  743.18   665.6  749.26   675.3  753.08   704.3  758.44
   742.9  770.34   781.6  778.55   839.5  787.37   916.8  795.41   965.1  799.17
#Mann= 3 , 0 , 0
       0      .1       0   350.2    .045       0     416     .06       0
Bank Sta=350.2,416
XS Rating Curve= 0 ,0
Exp/Cntr=0.3,0.1

Type RM Length L Ch R = 1 ,1334.3  ,180.7,181,181.3
XS GIS Cut Line= 4
     1905414.684      669467.941      1905889.25      670145.458
     1905997.323      670167.594     1906294.198      670192.333
#Sta/Elev= 30
       0  804.44    38.9  793.35    87.6  782.27     146  766.56   204.4  755.45
   233.6  751.58   282.2  747.04   379.5  741.12   437.9  734.61   467.1  729.96
   515.8  717.59   564.4   699.3   613.1  684.04   632.6  679.69   739.6  675.89
     798  674.93   817.5  671.99   836.4  667.95   854.8  667.27   891.5  669.35
   937.5  669.78   947.1  670.49   956.7  672.99   995.2   687.4  1052.8  712.66
    1072  724.23  1100.9  745.84  1168.1  790.75  1187.4  801.87  1235.4  825.52
#Mann= 3 , 0 , 0
       0      .1       0   817.5    .045       0   956.7     .08       0
Bank Sta=817.5,956.7
XS Rating Curve= 0 ,0
Exp/Cntr=0.3,0.1

Type RM Length L Ch R = 1 ,1153.3  ,353.3,352.5,351.8
XS GIS Cut Line= 4
      1905018.59      669974.885     1905885.778      670319.503
     1906009.042      670347.281     1906404.875      670402.837
#Sta/Elev= 30
       0  834.79    78.6  805.94   117.9  790.26   157.2   777.4   186.6  769.07
   255.4  752.14   304.5  741.47   402.7  725.01   461.7  718.04     501  715.04
   618.8  711.59     717   703.6   815.3  688.51   913.5  676.29   952.6  669.03
     972  666.84  1030.4   669.2  1040.1  670.68  1049.8  674.92  1069.3  688.65
  1098.5  717.21  1108.2  724.58    1118  730.31  1166.8  751.18    1196  759.68
    1235  772.77  1254.5  775.43  1322.7  779.49    1391  777.35  1459.2  772.58
#Mann= 3 , 0 , 0
       0     .08       0   952.6    .045       0  1040.1     .08       0
Bank Sta=952.6,1040.1
XS Rating Curve= 0 ,0
Exp/Cntr=0.3,0.1

Type RM Length L Ch R = 1 ,800.8   ,345.1,343.8,342.4
XS GIS Cut Line= 4
     1904761.646      670561.257     1905694.806      670633.739
      1905924.84      670678.444     1906519.893      670602.923
#Sta/Elev= 30
       0  717.39    68.2  718.14   146.2  715.62   302.2   702.2   448.5  700.57
   516.7  694.72   614.2  695.25   692.2  693.12   770.2  700.66   799.5  701.05
   916.5  684.94     975   683.1  1023.8  671.56  1033.6  668.32  1053.1  666.61
  1082.4  667.25    1102  671.94  1131.2  690.68    1141  693.07  1180.1   698.8
  1229.3  709.32  1278.5  714.15    1308  715.33  1386.6  712.32  1445.6  715.94
  1504.6  715.26  1563.6   723.1  1612.8  713.58  1632.5  713.51  1770.1  754.38
#Mann= 3 , 0 , 0
       0     .08       0  1023.8    .045       0    1102     .07       0
Bank Sta=1023.8,1102
XS Rating Curve= 0 ,0
Exp/Cntr=0.3,0.1

Type RM Length L Ch R = 1 ,457     ,275.2,275.9,276.6
XS GIS Cut Line= 4
     1905096.281      670993.548     1905571.542      670952.316
     1905749.493      670976.187     1906589.337      670826.448
#Sta/Elev= 30
       0  800.45    19.5  799.06   223.9  795.54   272.6  792.01   301.8  787.87
   311.5  783.63   321.3  776.99   350.5  754.48   399.2  732.53   408.9  727.27
   438.1  707.58     477  690.08   505.4  680.69   524.3  670.76   533.7  667.01
   543.2  666.44   618.8  670.55   656.6   674.3     686  684.74   695.8  686.59
   793.9  696.82   842.9  700.38   950.8  696.51  1019.4  697.87  1107.6  696.23
  1254.7  699.15  1284.2  694.01    1294  693.66  1421.4  710.92  1509.7  729.22
#Mann= 3 , 0 , 0
       0     .08       0   524.3    .045       0   618.8     .06       0
Bank Sta=524.3,618.8
XS Rating Curve= 0 ,0
Exp/Cntr=0.3,0.1

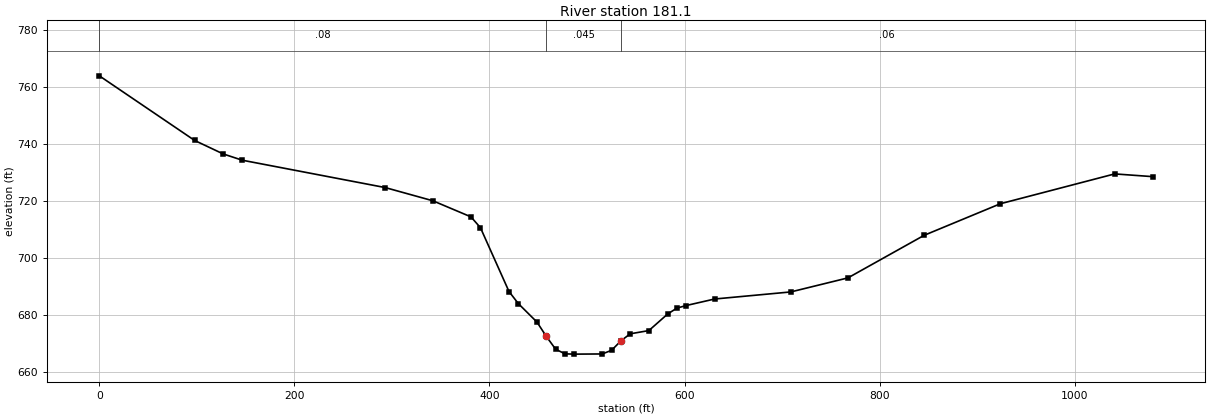
Type RM Length L Ch R = 1 ,181.1   ,179.7,181.1,182.6
XS GIS Cut Line= 4
     1905135.344      671123.757      1905543.33      671223.583
     1905732.132      671253.965     1906200.882      671247.455
#Sta/Elev= 30
       0   763.8    97.7  741.16     127  736.43   146.5  734.24     293  724.66
   341.9  720.03     381  714.39   390.7  710.61     420  688.24   429.6  683.99
   448.7  677.52   458.3  672.48   467.8  668.03   477.4   666.4     487   666.3
   515.6  666.36   525.2  667.65   534.8  670.96   544.3  673.42   563.4  674.55
   582.6  680.34   592.1  682.42   601.7  683.33   630.8  685.61   708.9  688.09
   767.5  693.01   845.6  707.92   923.8  718.99    1041  729.44    1080  728.48
#Mann= 3 , 0 , 0
       0     .08       0   458.3    .045       0   534.8     .06       0
Bank Sta=458.3,534.8
XS Rating Curve= 0 ,0
Exp/Cntr=0.3,0.1

Chan Stop Cuts=-1
Use User Specified Reach Order=0
Composite Channel Slope=5